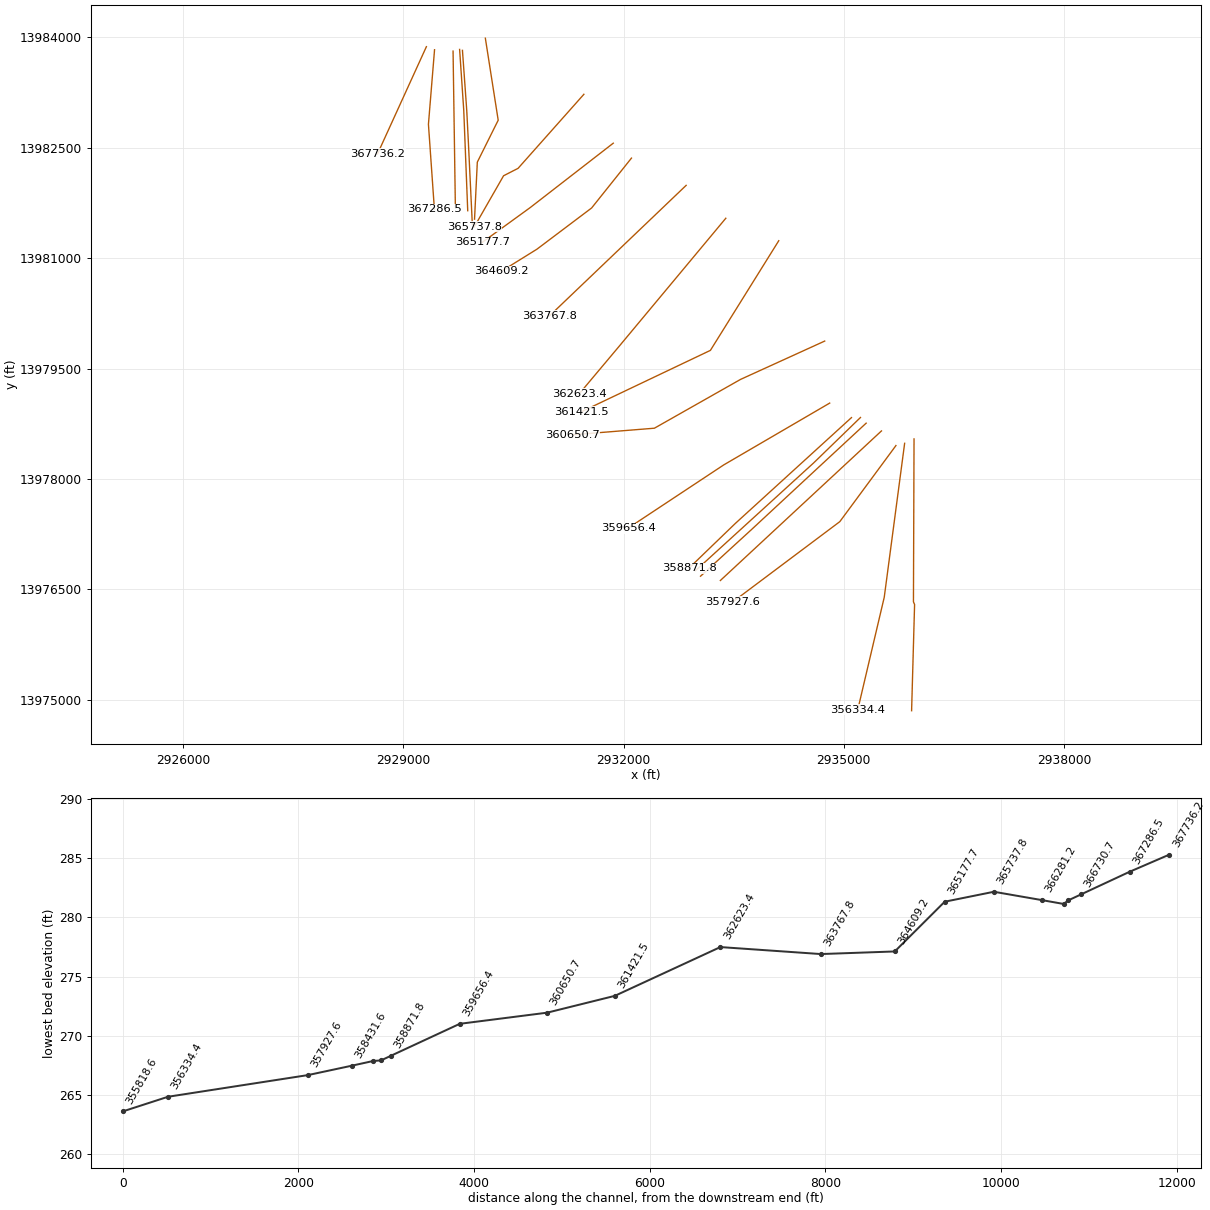
HEC-RAS study J100-00-00.prj: J100-00-00

--- J100-00-00.g01 (geometry) --- (continued)

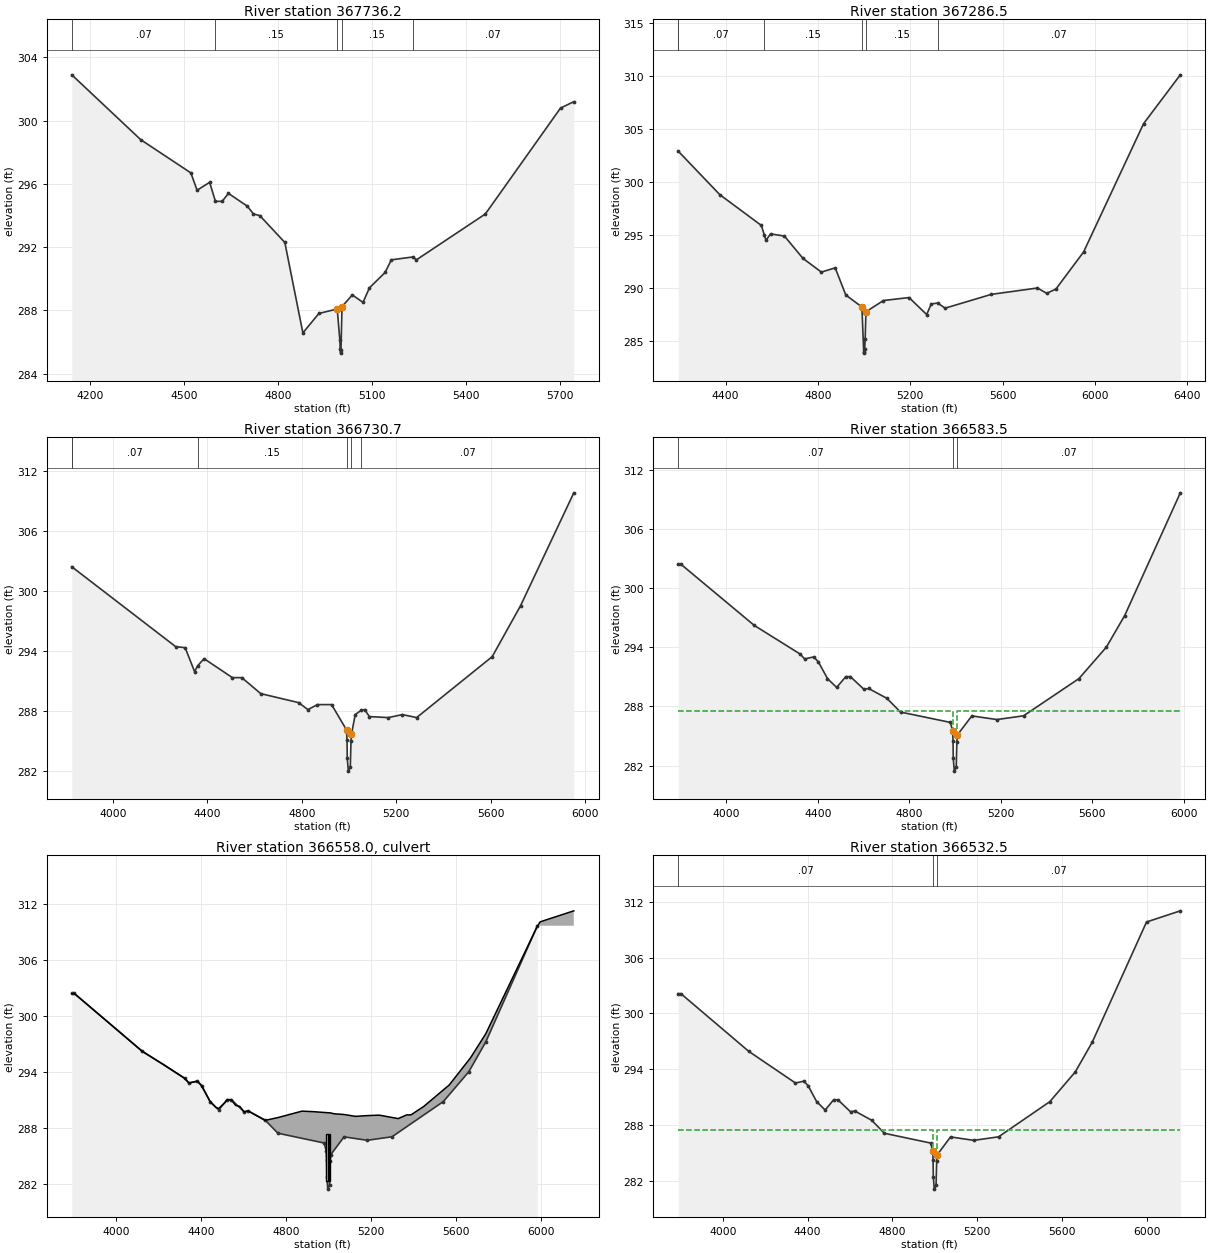
Type RM Length L Ch R = 1 ,367736.2,304.67,449.7,567.45
BEGIN DESCRIPTION:
Limits of Detailed Study
END DESCRIPTION:
XS GIS Cut Line= 2
    2929312.4799   13983874.8142    2928646.3256   13982417.6019
#Sta/Elev= 30
  4142.2   302.9  4362.2   298.8  4522.2   296.7  4542.2   295.6  4582.2   296.1
  4600.7   294.9  4622.2   294.9  4642.2   295.4  4702.2   294.6  4722.2   294.1
  4742.2     294  4822.2   292.3  4879.8  286.58    4931  287.81  4989.4  288.09
  4997.9   286.1  4998.9  285.57  5000.2   285.3  5001.4  285.51  5004.7  288.24
  5037.5  288.98  5071.7  288.51  5092.3  289.43  5142.2   290.4  5162.2   291.2
  5230.3  291.38  5242.2   291.2  5462.2   294.1  5702.2   300.8  5744.5   301.2
#Mann= 5 ,-1 , 0
  4142.2     .07       0  4600.7     .15       0  4989.4     .06       0
  5004.7     .15       0  5230.3     .07       0
Bank Sta=4989.4,5004.7
XS Rating Curve= 0
Exp/Cntr=.3,.1

Type RM Length L Ch R = 1 ,367286.5,332.89,555.8,419.42
BEGIN DESCRIPTION:
Cross Section XS300
END DESCRIPTION:
XS GIS Cut Line= 3
    2929423.5056   13983833.1796    2929340.2363     13982820.07
    2929421.5619   13981663.8586
#Sta/Elev= 30
  4194.6   302.9  4374.6   298.8  4554.6   295.9  4567.5     295  4574.6   294.5
  4594.6   295.1  4654.6   294.9  4734.6   292.8  4814.6   291.5  4874.6   291.9
  4920.6  289.34  4990.4  288.21  4998.2  283.94  5000.3  283.86  5002.4  284.21
  5004.4  285.15  5007.9  287.76  5083.7  288.82  5194.6   289.1  5271.1   287.5
  5291.1   288.5  5318.9  288.58  5351.1   288.1  5551.1   289.4  5751.1     290
  5791.1   289.5  5831.1   289.9  5951.1   293.4  6211.1   305.5  6370.2   310.1
#Mann= 6 , 1 , 0
  4194.6      .2       0  4194.6     .07       0  4567.5     .15       0
  4990.4     .06       0  5007.9     .15       0  5318.9     .07       0
Bank Sta=4990.4,5007.9
XS Rating Curve= 0
Exp/Cntr=.3,.1

Type RM Length L Ch R = 1 ,366730.7,87.8,147.2,117.88
BEGIN DESCRIPTION:
Cross Section XS299
END DESCRIPTION:
XS GIS Cut Line= 2
    2929675.8687   13983814.5676    2929707.3543   13981689.2893
#Sta/Elev= 30
  3826.3   302.4  4266.3   294.4  4306.3   294.3  4346.3   291.9  4359.2  292.48
  4386.3   293.2  4506.3   291.3  4546.3   291.3  4626.3   289.7  4786.3   288.8
  4826.3   288.1  4866.3   288.6  4926.3   288.6  4989.7  286.06  4991.7  285.02
  4992.6  283.28  4997.2  281.94  5005.6  282.37  5008.4  284.92  5010.4  285.61
  5026.3   287.6    5051  288.02  5066.3   288.1  5086.3   287.4  5166.3   287.3
  5226.3   287.6  5286.3   287.3  5606.3   293.4  5726.3   298.5  5951.8   309.8
#Mann= 6 , 1 , 0
  3826.3      .2       0  3826.3     .07       0  4359.2     .15       0
  4989.7     .06       0  5010.4     .15       0    5051     .07       0
Bank Sta=4989.7,5010.4
XS Rating Curve= 0
Exp/Cntr=.5,.3

Type RM Length L Ch R = 1 ,366583.5,51,51,51
BEGIN DESCRIPTION:
Upstream Section of FM 1736
END DESCRIPTION:
XS GIS Cut Line= 4
      2929765.08   13983837.2709    2929821.6691   13983006.8863
    2929836.6308   13982629.5208    2929875.6484   13981645.4084
#Sta/Elev= 30
  3790.4  302.43  3802.8  302.43  4122.8  296.23  4322.8  293.33  4342.8  292.83
  4382.8  293.03  4402.8  292.53  4442.8  290.83  4482.8  289.93  4522.8  291.03
  4542.8  291.03  4602.8  289.73  4622.1  289.83  4702.1  288.83  4762.1  287.43
  4979.9  286.38  4989.7  285.55  4991.7  284.51  4992.6  282.77  4997.2  281.43
  5005.6  281.86  5008.4  284.41  5010.4   285.1  5073.9  287.04  5183.4  286.67
  5300.2  287.05  5542.1  290.83  5662.1  294.03  5742.1  297.23  5985.3   309.7
#Mann= 3 ,-1 , 0
  3790.4     .07       0  4989.7     .06       0  5010.4     .07       0
#XS Ineff= 2 , 0
       0  4990.2   287.5  5009.8       0   287.5
Permanent Ineff=
       F       F
Bank Sta=4989.7,5010.4
XS Rating Curve= 0
Exp/Cntr=.5,.3

Type RM Length L Ch R = 2 ,366558.0,,,
BEGIN DESCRIPTION:
FM 1736
Structure ID: J100-00-00-23
END DESCRIPTION:
Node Name=FM 1736
Bridge Culvert--1,0,-1,-1, 0
Deck Dist Width WeirC Skew NumUp NumDn MinLoCord MaxHiCord MaxSubmerge Is_Ogee
10,31,3,0, 65, 65, , , .95, 0, 1,1,,
  3790.4  3802.8  4122.8  4210.4  4222.8  4322.8  4342.8  4382.8  4390.4  4402.8
  4442.8  4470.4  4482.8  4510.4  4522.8  4542.8  4562.8  4582.8  4602.6  4602.8
  4622.1  4662.6  4702.1  4762.1  4802.1  4816.1  4875.6  4875.9  4923.5  4926.7
  4978.4  4979.9  4989.7  4991.7  4992.6  4997.2  5005.6  5008.4  5010.4  5010.9
  5022.3  5031.2  5073.9    5074  5128.1  5128.2    5182  5183.4  5239.7  5239.8
  5300.2  5302.1  5329.4  5369.4  5389.4  5449.4  5542.1  5569.4  5662.1  5669.4
  5742.1  5982.1  5997.7  6029.4    6157
   302.4  302.41  296.21  294.98  294.81  293.31  292.81  293.01  292.82  292.51
  290.81  290.19  290.09  290.67  291.01  291.01  290.41  290.31  289.72  289.71
  289.81   289.3  288.81  289.11  289.35  289.44   289.8   289.8  289.75  289.75
  289.66  289.66  289.64  289.64  289.64  289.63  289.62  289.61  289.61  289.61
  289.54  289.51  289.44  289.44  289.24  289.24  289.32  289.32  289.37  289.37
  289.12  289.11     289   289.4   289.4   290.3  292.08   292.6  295.29   295.5
  298.11  309.51  310.11  310.35   311.3
                                                                                
                                                                                
                                                                                
                                                                                
                                                                                
                                                                                
                                        
  3790.4  3802.8  4122.8  4210.4  4222.8  4322.8  4342.8  4382.8  4390.4  4402.8
  4442.8  4470.4  4482.8  4510.4  4522.8  4542.8  4562.8  4582.8  4602.6  4602.8
  4622.1  4662.6  4702.1  4762.1  4802.1  4816.1  4875.6  4875.9  4923.5  4926.7
  4978.4  4979.9  4989.7  4991.7  4992.6  4997.2  5005.6  5008.4  5010.4  5010.9
  5022.3  5031.2  5073.9    5074  5128.1  5128.2    5182  5183.4  5239.7  5239.8
  5300.2  5302.1  5329.4  5369.4  5389.4  5449.4  5542.1  5569.4  5662.1  5669.4
  5742.1  5982.1  5997.7  6029.4    6157
   302.4  302.41  296.21  294.98  294.81  293.31  292.81  293.01  292.82  292.51
  290.81  290.19  290.09  290.67  291.01  291.01  290.41  290.31  289.72  289.71
  289.81   289.3  288.81  289.11  289.35  289.44   289.8   289.8  289.75  289.75
  289.66  289.66  289.64  289.64  289.64  289.63  289.62  289.61  289.61  289.61
  289.54  289.51  289.44  289.44  289.24  289.24  289.32  289.32  289.37  289.37
  289.12  289.11     289   289.4   289.4   290.3  292.08   292.6  295.29   295.5
  298.11  309.51  310.11  310.35   311.3
                                                                                
                                                                                
                                                                                
                                                                                
                                                                                
                                                                                
                                        
BR Coef= 1 , 1 , 0 ,1.25, 0 ,,,.8,-1,2,0,
WSPro=,,,, 1 ,,,, 0 ,,,, 0 ,,,,-1 ,-1 ,-1 , 0 , 0 , 0 , 0 , 0
Culvert=2,5,6,31,.015,.4,1,8,1,282.35,4993.2,282,4993.2,Culvert #1  , 0 ,10
Culvert Bottom n=.015
Culvert=2,5,6,31,.015,.4,1,8,1,282.35,5000,282,5000,Culvert #2  , 0 ,10
Culvert Bottom n=.015
Culvert=2,5,6,31,.015,.4,1,8,1,282.35,5006.8,282,5006.8,Culvert #3  , 0 ,10
Culvert Bottom n=.015
BC Design=,, 0 ,, 0 ,,,,,,
BC HTab HWMax=309.7

Type RM Length L Ch R = 1 ,366532.5,251.3,251.3,251.3
BEGIN DESCRIPTION:
Downstream Section of FM 1736
END DESCRIPTION:
XS GIS Cut Line= 4
    2929803.8232   13983824.3693    2929861.9504   13983014.2205
    2929882.5944   13982616.4351    2929938.2425    13981461.738
#Sta/Elev= 30
  3790.4  302.13  3802.8  302.13  4122.8  295.93  4342.8  292.53  4382.8  292.73
  4402.8  292.23  4442.8  290.53  4482.8  289.63  4522.8  290.73  4542.8  290.73
  4602.8  289.43  4622.1  289.53  4702.1  288.53  4762.1  287.13  4979.9  286.08
  4989.7  285.25  4991.7  284.21  4992.6  282.47  4997.2  281.13  5005.6  281.56
  5008.4  284.11  5010.4   284.8  5073.9  286.74  5183.4  286.37  5300.2  286.75
  5542.1  290.53  5662.1  293.73  5742.1  296.93  5997.7  309.83    6157  311.03
#Mann= 3 ,-1 , 0
  3790.4     .07       0  4989.7     .06       0  5010.4     .07       0
#XS Ineff= 2 , 0
       0  4990.2   287.5  5009.8       0   287.5
Permanent Ineff=
       F       F
Bank Sta=4989.7,5010.4
XS Rating Curve= 0
Exp/Cntr=.5,.3

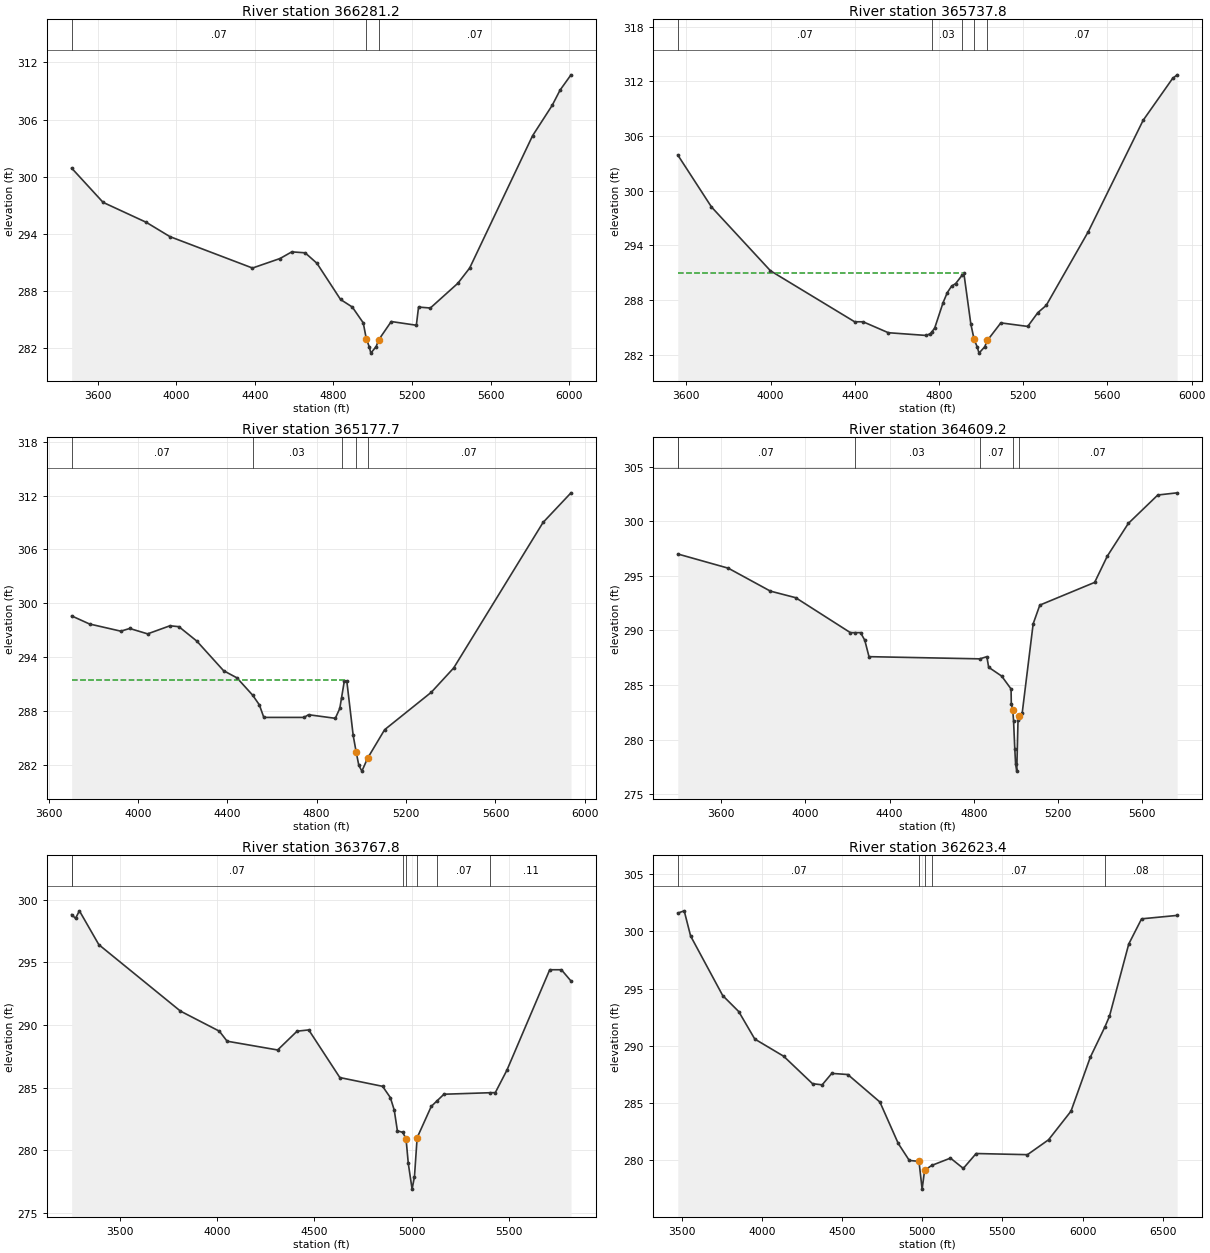
Type RM Length L Ch R = 1 ,366281.2,694.7,543.4,391.76
BEGIN DESCRIPTION:
Cross Section XS298
END DESCRIPTION:
XS GIS Cut Line= 4
    2930115.8123   13983989.7478    2930290.8939   13982875.5829
    2930006.3572   13982305.8224    2929968.4689   13981531.2167
#Sta/Elev= 27
  3468.1   300.9  3628.1   297.3  3848.1   295.2  3968.1   293.7  4388.1   290.4
  4528.1   291.4  4588.1   292.1  4655.9     292  4715.9   290.9  4835.9   287.1
  4895.9   286.3  4951.5  284.64  4966.9  282.98  4982.7  282.08  4990.1  281.46
  5017.3  282.15  5029.8  282.85  5093.9  284.78  5221.6  284.39  5232.8   286.3
  5292.8   286.2  5432.8   288.8  5492.8   290.4  5812.8   304.3  5912.8   307.5
  5952.8   309.1  6008.3   310.7
#Mann= 3 ,-1 , 0
  3468.1     .07       0  4966.9     .06       0  5029.8     .07       0
Bank Sta=4966.9,5029.8
XS Rating Curve= 0
Exp/Cntr=.3,.1

Type RM Length L Ch R = 1 ,365737.8,597.9,560.1,532.46
BEGIN DESCRIPTION:
Ineffective flow at left pond
Cross Section XS297
END DESCRIPTION:
XS GIS Cut Line= 4
    2931458.7429   13983227.7716    2930562.0526   13982221.6261
    2930364.1914   13982120.5906    2929964.7559   13981425.3096
#Sta/Elev= 30
  3559.6   303.9  3719.6   298.2  3999.6   291.2  4399.6   285.6  4439.6   285.6
  4559.6   284.4  4739.6   284.1  4759.6   284.3  4766.7  284.51  4779.6   284.9
  4819.6   287.7  4839.6   288.8  4859.6   289.5  4879.6   289.8  4909.6   290.7
  4918.1  290.96  4951.5  285.34  4966.9  283.68  4982.7  282.78  4990.1  282.16
  5017.3  282.85  5029.8  283.55  5093.9  285.48  5221.6  285.09  5269.5   286.6
  5309.5   287.4  5509.5   295.5  5769.5   307.7  5909.5   312.3  5931.3   312.7
#Mann= 5 ,-1 , 0
  3559.6     .07       0  4766.7     .03       0  4909.6     .07       0
  4966.9     .06       0  5029.8     .07       0
#XS Ineff= 2 , 0
       0    4918     291               0
Permanent Ineff=
       F       F
Bank Sta=4966.9,5029.8
XS Rating Curve= 0
Exp/Cntr=.3,.1

Type RM Length L Ch R = 1 ,365177.7,521.7,568.5,511.91
BEGIN DESCRIPTION:
Ineffective flow at left pond
 Cross Section XS296
END DESCRIPTION:
XS GIS Cut Line= 3
     2931859.132   13982563.3231    2930728.0576   13981688.9957
    2930075.7816   13981217.1364
#Sta/Elev= 30
  3703.4   298.6  3783.4   297.7  3923.4   296.9  3963.4   297.2  4043.4   296.6
  4143.4   297.5  4183.4   297.4  4263.4   295.8  4383.4   292.5  4443.4   291.7
  4513.3  289.78  4543.4   288.7  4563.4   287.3  4743.4   287.3  4763.4   287.6
  4883.4   287.2  4903.4   288.3  4911.1  289.46  4923.4   291.3  4934.8  291.35
  4963.4  285.29  4976.5  283.48  4988.6  281.96  5002.3  281.32  5027.9  282.76
    5104  285.93    5313   290.1    5413   292.8    5813     309  5938.1   312.3
#Mann= 5 ,-1 , 0
  3703.4     .07       0  4513.3     .03       0  4911.1     .07       0
  4976.5     .06       0  5027.9     .07       0
#XS Ineff= 2 , 0
       0    4930   291.5               0
Permanent Ineff=
       F       F
Bank Sta=4976.5,5027.9
XS Rating Curve= 0
Exp/Cntr=.3,.1

Type RM Length L Ch R = 1 ,364609.2,841.4,841.4,841.4
BEGIN DESCRIPTION:
Cross Section XS295
END DESCRIPTION:
XS GIS Cut Line= 4
    2932107.0542   13982360.5499    2931563.9883   13981682.7699
    2930818.8512   13981122.8647    2930332.5285   13980821.6073
#Sta/Elev= 30
  3394.1     297  3634.1   295.7  3834.1   293.6  3954.1     293  4214.1   289.8
  4234.5   289.8  4262.6   289.8  4282.6   289.1  4302.6   287.6  4829.4   287.4
  4862.6   287.6  4871.1  286.63    4933  285.82  4977.6  284.64  4978.7  283.29
  4985.5  282.74  4989.4  281.74  4995.2  279.18  4999.2  277.76  5004.6  277.12
  5010.6  281.76  5015.1  282.18  5030.3  282.41  5082.6  290.61  5114.2  292.32
  5374.7   294.4  5434.7   296.8  5534.7   299.8  5674.7   302.4  5766.7   302.6
#Mann= 6 , 1 , 0
  3394.1      .2       0  3394.1     .07       0  4234.5     .03       0
  4829.4     .07       0  4985.5     .06       0  5015.1     .07       0
Bank Sta=4985.5,5015.1
XS Rating Curve= 0
Exp/Cntr=.3,.1

Type RM Length L Ch R = 1 ,363767.8,871.39,1144.4,928.59
BEGIN DESCRIPTION:
Cross Section XS294
END DESCRIPTION:
XS GIS Cut Line= 2
    2932852.1912   13981990.0863    2930991.7437   13980217.9051
#Sta/Elev= 30
  3251.2   298.8  3271.2   298.5  3291.2   299.1  3391.2   296.4  3811.2   291.1
  4011.2   289.5  4051.2   288.7  4311.2     288  4411.2   289.5  4471.2   289.6
  4631.2   285.8  4851.2   285.1  4891.2   284.2  4911.2   283.2  4927.3  281.55
  4954.7  281.43  4971.8  280.92  4983.4  278.95    5003   276.9  5015.1  277.88
  5028.9     281  5101.6   283.5  5129.8  283.92  5166.8  284.47  5403.2  284.59
  5431.2   284.6  5491.2   286.4  5711.2   294.4  5771.2   294.4  5820.6   293.5
#Mann= 7 , 1 , 0
  3251.2      .2       0  3251.2     .07       0  4954.7     .13       0
  4971.8     .06       0  5028.9     .13       0  5129.8     .07       0
  5403.2     .11       0
Bank Sta=4971.8,5028.9
XS Rating Curve= 0
Exp/Cntr=.3,.1

Type RM Length L Ch R = 1 ,362623.4,939.52,1201.9,849.76
BEGIN DESCRIPTION:
Cross Section XS293
END DESCRIPTION:
XS GIS Cut Line= 3
    2933392.6746   13981543.2744    2931949.3404   13979815.4369
    2931394.2118   13979156.2218
#Sta/Elev= 30
  3476.7   301.6  3516.7   301.8  3556.7   299.6  3756.7   294.4  3856.7     293
  3956.7   290.6  4136.7   289.1  4316.7   286.7  4376.7   286.6  4436.7   287.6
  4536.7   287.5  4736.7   285.1  4851.1  281.48  4919.8     280  4980.5  279.91
    5000  277.49  5015.5  279.14  5059.8  279.56  5176.7   280.2  5256.7   279.3
  5336.7   280.6  5656.7   280.5  5788.1   281.8  5928.1   284.3  6048.1     289
  6140.4  291.69  6168.1   292.6  6288.1   298.9  6368.1   301.1  6589.9   301.4
#Mann= 5 ,-1 , 0
  3476.7     .07       0  4980.5     .06       0  5015.5     .07       0
  5059.8     .07       0  6140.4     .08       0
Bank Sta=4980.5,5015.5
XS Rating Curve= 0
Exp/Cntr=.3,.1

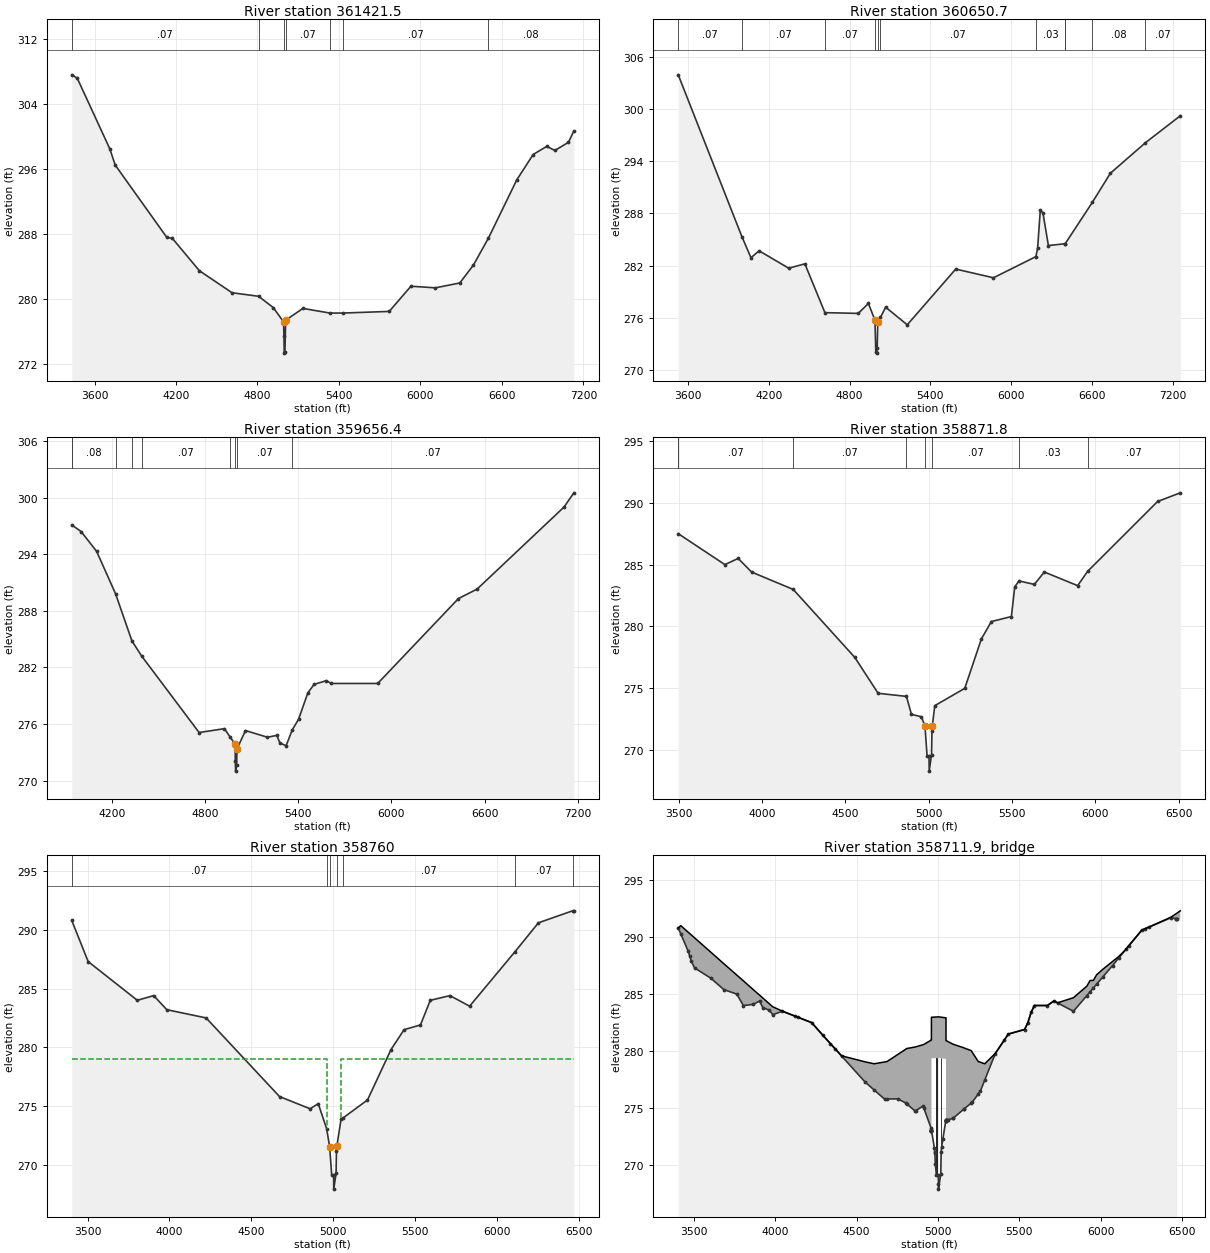
Type RM Length L Ch R = 1 ,361421.5,814.44,770.8,604.35
BEGIN DESCRIPTION:
Cross Section XS292
END DESCRIPTION:
XS GIS Cut Line= 3
    2934114.3416   13981237.9537    2933182.6616   13979747.8343
    2931430.3267   13978916.3961
#Sta/Elev= 30
  3432.6   307.6  3472.6   307.2  3712.6   298.5  3752.6   296.5  4132.6   287.6
  4172.6   287.5  4372.6   283.5  4612.6   280.8  4808.2  280.36  4916.5  278.97
    4992  277.22    4995   275.5  4996.9  273.37    5002  273.49  5007.7  277.41
    5134  278.87  5333.4   278.3    5430   278.3    5770   278.5    5930   281.6
    6110   281.4    6290     282    6390   284.2  6501.1  287.53    6710   294.7
    6830   297.8    6930   298.8    6990   298.3    7090   299.3  7129.6   300.7
#Mann= 7 ,-1 , 0
  3432.6     .07       0  4808.2     .07       0    4992     .06       0
  5007.7     .07       0  5333.4     .07       0    5430     .07       0
  6501.1     .08       0
Bank Sta=4992,5007.7
XS Rating Curve= 0
Exp/Cntr=.3,.1

Type RM Length L Ch R = 1 ,360650.7,878.05,994.3,912.75
BEGIN DESCRIPTION:
Cross Section XS291
END DESCRIPTION:
XS GIS Cut Line= 4
    2934740.2927   13979874.1287    2933593.1184   13979353.1643
    2932419.6329   13978690.1186    2931304.0323   13978600.6601
#Sta/Elev= 30
  3528.6   303.9  4001.2  285.32  4068.6   282.9  4128.6   283.7  4348.6   281.7
  4468.6   282.2  4617.4   276.6  4864.9  276.51  4940.2  277.66  4988.8  275.73
  4995.2  272.09  5000.9  271.95  5005.4  272.58  5009.9  275.48  5029.2  276.05
  5068.6  277.22  5228.5   275.2  5588.5   281.6  5868.5   280.6  6183.5  283.03
  6196.4     284  6216.4   288.4  6236.4     288  6276.4   284.3  6401.1  284.51
  6401.5  284.52  6602.2  289.25  6736.4   292.6    6997  296.11  7255.6   299.2
#Mann= 11 ,-1 , 0
  3528.6     .07       0  4001.2     .07       0  4617.4     .07       0
  4988.8     .06       0  5009.9     .07       0  5029.2     .07       0
  6183.5     .03       0  6401.1     .03       0  6401.5     .07       0
  6602.2     .08       0    6997     .07       0
Bank Sta=4988.8,5009.9
XS Rating Curve= 0
Exp/Cntr=.3,.1

Type RM Length L Ch R = 1 ,359656.4,620.73,784.6,761.03
BEGIN DESCRIPTION:
Cross Section XS290
END DESCRIPTION:
XS GIS Cut Line= 3
    2934808.2523   13979031.3178    2933364.9181   13978191.6859
    2932060.3661   13977331.2367
#Sta/Elev= 30
  3942.4   297.1  4002.4   296.4  4102.4   294.3  4224.9  289.78  4329.6  284.81
  4392.2  283.21  4762.4   275.1  4925.2  275.51  4963.1   274.6  4994.2  273.85
  4995.4   272.1  4997.4  271.01  5003.5  271.69  5006.7  273.38  5060.9  275.31
  5202.4   274.6  5262.4   274.8  5282.4     274  5322.4   273.7  5361.9  275.38
  5402.4   276.5  5462.4   279.3  5502.4   280.2  5582.4   280.6  5612.2   280.3
  5912.2   280.3  6432.2   289.3  6552.2   290.3  7112.2     299    7175   300.5
#Mann= 9 , 1 , 0
  3942.4      .2       0  3942.4     .08       0  4224.9     .15       0
  4329.6     .07       0  4392.2     .07       0  4963.1     .07       0
  4994.2     .06       0  5006.7     .07       0  5361.9     .07       0
Bank Sta=4994.2,5006.7
XS Rating Curve= 0
Exp/Cntr=.3,.1

Type RM Length L Ch R = 1 ,358871.8,111.8,111.8,111.8
BEGIN DESCRIPTION:
Cross Section XS289
END DESCRIPTION:
XS GIS Cut Line= 3
    2935105.1466   13978834.4061    2933523.1332   13977396.7589
    2932891.5309   13976789.2177
#Sta/Elev= 30
  3496.3   287.5  3776.3     285  3856.3   285.5  3936.3   284.4    4187  282.99
  4556.3   277.5  4696.3   274.6  4866.2  274.35  4896.3   272.9  4956.3   272.7
  4977.7  271.93  4990.1  269.55  5001.8  269.52  5002.9  268.31    5017  269.65
  5019.4  271.57  5021.6  271.96  5036.3   273.6  5216.3     275  5316.3     279
  5376.3   280.4  5496.3   280.8  5516.3   283.2  5541.9  283.68    5634   283.4
    5694   284.4    5894   283.3  5953.6  284.45    6374   290.1  6510.3   290.8
#Mann= 8 , 1 , 0
  3496.3      .2       0  3496.3     .07       0    4187     .07       0
  4866.2     .07       0  4977.7     .06       0  5021.6     .07       0
  5541.9     .03       0  5953.6     .07       0
Bank Sta=4977.7,5021.6
XS Rating Curve= 0
Exp/Cntr=.5,.3

Type RM Length L Ch R = 1 ,358760  ,90,90,90
BEGIN DESCRIPTION:
Upstream Section of FM 1488
END DESCRIPTION:
XS GIS Cut Line= 3
    2935227.7922   13978835.8378    2934589.3944   13978218.2573
    2932979.5216   13976754.1058
#Sta/Elev= 30
  3403.9   290.8  3503.9   287.3  3803.9     284  3903.9   284.4  3983.9   283.2
  4223.9   282.5  4672.1   275.8  4859.2  274.76  4908.1   275.2  4959.3  273.07
  4977.7  271.54  4990.1  269.16  5001.8  269.13  5002.9  267.92    5017  269.26
  5019.4  271.18  5021.6  271.57    5048  273.93  5059.4  273.98  5208.7  275.51
  5352.1   279.8  5432.1   281.5  5532.1   281.9  5592.1     284  5712.1   284.4
  5832.1   283.5  6109.7  288.15  6252.1   290.6  6460.2  291.62  6468.2   291.6
#Mann= 7 ,-1 , 0
  3403.9     .07       0  4959.3     .06       0  4977.7     .06       0
  5021.6     .06       0  5059.4     .07       0  6109.7     .07       0
  6460.2     .07       0
#XS Ineff= 2 , 0
       0  4959.6     279  5049.5       0     279
Permanent Ineff=
       F       F
Bank Sta=4977.7,5021.6
XS Rating Curve= 0
Exp/Cntr=.5,.3

Type RM Length L Ch R = 3 ,358711.9,,,
BEGIN DESCRIPTION:
FM 1488
Structure ID: J100-00-00-22
Circular piers, twin-cylinder piers without diaphragm
END DESCRIPTION:
Node Name=FM 1488
Bridge Culvert--1,0,-1,-1, 0
Deck Dist Width WeirC Skew NumUp NumDn MinLoCord MaxHiCord MaxSubmerge Is_Ogee
30,49,3,0, 99, 99, , , .95, 0, 1,1,,
  3403.9  3419.4  3463.9  3474.6  3483.9  3503.9  3603.9  3683.9  3763.9  3803.9
  3863.9  3903.9  3923.9  3963.9  3983.9  4043.9  4119.4  4139.4  4223.9  4292.1
  4339.4  4367.1  4407.1  4552.1  4607.1  4672.1  4687.1  4752.3  4802.1  4808.3
  4859.2  4861.8  4908.1    4912  4956.7  4959.3 4959.37 4959.48 4959.59 4959.71
  4959.8  4959.9  4977.7  4979.8  4980.7  4983.9  4990.1  5001.8  5002.5  5002.9
    5017  5019.4  5021.6  5029.4    5048 5048.96 5049.07 5049.18 5049.29  5049.4
  5049.5  5059.4  5091.6  5093.5  5156.7  5161.3  5204.4  5208.7  5247.1  5259.6
  5287.1  5352.1  5407.1  5432.1  5532.1  5552.1  5572.1  5592.1  5672.1  5712.1
  5734.5  5832.1  5914.5  5934.5  5954.5  5974.5  6014.5  6072.1  6109.7  6154.5
  6174.5  6252.1  6274.5  6294.5  6432.1  6460.2  6464.5  6468.2  6488.7
   290.8     291  290.44  290.31  290.19  289.94  288.68  287.67  286.67  286.17
  285.41  284.91  284.66  284.15   283.9  283.51  283.09  282.98  282.51  281.41
  280.66  280.23   279.6  279.07   278.9  279.06   279.1  279.71  280.18  280.24
  280.37  280.38  280.57  280.59  280.96  280.98  280.98  282.98  282.98  282.98
  282.98  282.98  282.99  282.99  282.99     283     283  283.01  283.01  283.01
  282.99  282.98  282.98  282.96  282.93  282.93  282.93  280.93  280.93  280.93
  280.93  280.86  280.62  280.61  280.31  280.28  280.05  279.95   279.1  279.04
   278.9  279.81  280.98  281.51  281.91  282.51  283.41  284.01  284.01  284.41
  284.24  284.69   285.7   286.2   286.2   286.7   287.2  287.86  288.29  288.93
   289.3  290.61  290.75  290.87  291.75  292.02  292.06   292.1   292.3
                                                                                
                                                                                
                                                                                
                                                                                
  279.38  279.38  279.39  279.39  279.39   279.4   279.4  279.41  279.41  279.41
  279.39  279.38  279.38  279.36  279.33  279.33  279.33  279.33  279.33
                                                                                
                                                                                
                                                                                
                                                                        
  3403.9  3419.4  3463.9  3474.6  3483.9  3503.9  3603.9  3683.9  3763.9  3803.9
  3863.9  3903.9  3923.9  3963.9  3983.9  4043.9  4119.4  4139.4  4223.9  4292.1
  4339.4  4367.1  4407.1  4552.1  4607.1  4672.1  4687.1  4752.3  4802.1  4808.3
  4859.2  4861.8  4908.1    4912  4956.7  4959.3 4959.37 4959.48 4959.59 4959.71
  4959.8  4959.9  4977.7  4979.8  4980.7  4983.9  4990.1  5001.8  5002.5  5002.9
    5017  5019.4  5021.6  5029.4    5048 5048.96 5049.07 5049.18 5049.29  5049.4
  5049.5  5059.4  5091.6  5093.5  5156.7  5161.3  5204.4  5208.7  5247.1  5259.6
  5287.1  5352.1  5407.1  5432.1  5532.1  5552.1  5572.1  5592.1  5672.1  5712.1
  5734.5  5832.1  5914.5  5934.5  5954.5  5974.5  6014.5  6072.1  6109.7  6154.5
  6174.5  6252.1  6274.5  6294.5  6432.1  6460.2  6464.5  6468.2  6488.7
   290.8     291  290.44  290.31  290.19  289.94  288.68  287.67  286.67  286.17
  285.41  284.91  284.66  284.15   283.9  283.51  283.09  282.98  282.51  281.41
  280.66  280.23   279.6  279.07   278.9  279.06   279.1  279.71  280.18  280.24
  280.37  280.38  280.57  280.59  280.96  280.98  280.98  282.98  282.98  282.98
  282.98  282.98  282.99  282.99  282.99     283     283  283.01  283.01  283.01
  282.99  282.98  282.98  282.96  282.93  282.93  282.93  280.93  280.93  280.93
  280.93  280.86  280.62  280.61  280.31  280.28  280.05  279.95   279.1  279.04
   278.9  279.81  280.98  281.51  281.91  282.51  283.41  284.01  284.01  284.41
  284.24  284.69   285.7   286.2   286.2   286.7   287.2  287.86  288.29  288.93
   289.3  290.61  290.75  290.87  291.75  292.02  292.06   292.1   292.3
                                                                                
                                                                                
                                                                                
                                                                                
  279.38  279.38  279.39  279.39  279.39   279.4   279.4  279.41  279.41  279.41
  279.39  279.38  279.38  279.36  279.33  279.33  279.33  279.33  279.33
                                                                                
                                                                                
                                                                                
                                                                        
Pier Skew, UpSta & Num, DnSta & Num=  ,4990.1, 2 ,4990.1, 2 , 0 , 0 , 0 ,,
     1.2     1.2
  268.16   280.4
     1.2     1.2
  268.12  280.36
Pier Skew, UpSta & Num, DnSta & Num=  ,5019.8, 2 ,5019.8, 2 , 0 , 0 , 0 ,,
     1.2     1.2
  270.02  280.38
     1.2     1.2
  269.98  280.34
Abutment Skew #Up #Dn= , 2 , 2
  4959.6  4979.8
  279.38   271.2
  4959.6  4979.8
  279.34  271.16
Abutment Skew #Up #Dn= , 2 , 2
  5029.4 5049.49
  272.27  279.33
  5029.4 5049.49
  272.23  279.29
BR Coef= 1 , 1 , 1 ,1.05, 0 ,,,.8,0,1.2,0,
WSPro=,,,, 1 ,,,, 0 ,,,, 0 ,,,,-1 ,-1 ,-1 , 0 , 0 , 0 , 0 , 0
BR U #Sta/Elev= 98
  3403.9   290.8  3419.4  290.28  3463.9   288.8  3474.6  288.32  3483.9   287.9
  3503.9   287.3  3603.9   286.4  3683.9   285.4  3763.9     285  3803.9     284
  3863.9   284.1  3903.9   284.4  3923.9   283.8  3963.9   283.6  3983.9   283.2
  4043.9   283.5  4119.4  283.08  4139.4  282.97  4223.9   282.5  4292.1   281.4
  4339.4  280.65  4367.1  280.22  4407.1  279.59  4552.1   277.3  4607.1  276.61
  4672.1   275.8  4687.1  275.81  4752.3  275.83  4802.1  275.46  4808.3  275.38
  4859.2  274.76  4861.8  274.78  4908.1   275.2    4912  275.05  4956.7  273.29
  4959.3  273.07 4959.37  273.07 4959.48  273.06 4959.59  273.05 4959.71  273.04
  4959.8  273.03  4959.9  273.02  4977.7  271.54  4979.8   271.2  4980.7  271.05
  4983.9  270.08  4990.1  269.16  5001.8  269.13  5002.5  268.36  5002.9  267.92
    5017  269.26  5019.4  271.18  5021.6  271.57  5029.4  272.27    5048  273.93
 5048.96  273.93 5049.07  273.93 5049.18  273.94 5049.29  273.94  5049.4  273.94
  5049.5  273.94  5059.4  273.98  5091.6  274.12  5093.5  274.14  5156.7   274.9
  5161.3  274.96  5204.4  275.46  5208.7  275.51  5247.1  276.24  5259.6  276.48
  5287.1  277.47  5352.1   279.8  5407.1  280.97  5432.1   281.5  5532.1   281.9
  5552.1   282.5  5572.1   283.4  5592.1     284  5672.1     284  5712.1   284.4
  5734.5  284.23  5832.1   283.5  5914.5  284.87  5934.5  285.21  5954.5  285.54
  5974.5  285.87  6014.5  286.54  6072.1   287.5  6109.7  288.15  6154.5  288.92
  6174.5  289.26  6252.1   290.6  6274.5  290.74  6294.5  290.86  6432.1   291.7
  6460.2  291.62  6464.5  291.61  6468.2   291.6
BR U #Mann= 7
  3403.9     .07  4959.3     .06  4977.7    .055  5021.6     .06  5059.4     .07
  6109.7     .07  6460.2     .07
BR D #Sta/Elev= 99
  3403.9  290.75  3419.4  290.23  3463.9  288.75  3474.6  288.27  3483.9  287.85
  3503.9  287.25  3603.9  286.35  3683.9  285.35  3763.9  284.95  3803.9  283.95
  3863.9  284.05  3903.9  284.35  3923.9  283.75  3963.9  283.55  3983.9  283.15
  4043.9  283.45  4119.4  283.03  4139.4  282.92  4223.9  282.45  4292.1  281.35
  4339.4   280.6  4367.1  280.17  4407.1  279.54  4552.1  277.25  4607.1  276.56
  4672.1  275.75  4687.1  275.76  4752.3  275.78  4802.1  275.41  4808.3  275.33
  4859.2  274.71  4861.8  274.73  4908.1  275.15    4912     275  4956.7  273.24
  4959.3  273.02 4959.37  273.02 4959.48  273.01 4959.59     273 4959.71  272.99
  4959.8  272.98  4959.9  272.97  4977.7  271.49  4979.8  271.15  4980.7     271
  4983.9  270.03  4990.1  269.11  5001.8  269.08  5002.5  268.31  5002.9  267.87
    5017  269.21  5019.4  271.13  5021.6  271.52  5029.4  272.22    5048  273.88
 5048.96  273.88 5049.07  273.88 5049.18  273.89 5049.29  273.89  5049.4  273.89
  5049.5  273.89  5059.4  273.93  5091.6  274.07  5093.5  274.09  5156.7  274.85
  5161.3  274.91  5204.4  275.41  5208.7  275.46  5247.1  276.19  5259.6  276.43
  5287.1  277.42  5352.1  279.75  5407.1  280.92  5432.1  281.45  5532.1  281.85
  5552.1  282.45  5572.1  283.35  5592.1  283.95  5672.1  283.95  5712.1  284.35
  5734.5  284.18  5832.1  283.45  5914.5  284.82  5934.5  285.16  5954.5  285.49
  5974.5  285.82  6014.5  286.49  6072.1  287.45  6109.7   288.1  6154.5  288.87
  6174.5  289.21  6252.1  290.55  6274.5  290.69  6294.5  290.81  6432.1  291.65
  6460.2  291.57  6464.5  291.56  6468.2  291.55  6473.2     292
BR D #Mann= 7
  3403.9     .07  4959.3     .06  4977.7    .055  5021.6     .06  5059.4     .07
  6109.7     .07  6460.2     .07
BC Design=,, 0 ,, 0 ,,,,,,
BC HTab HWMax=291.7

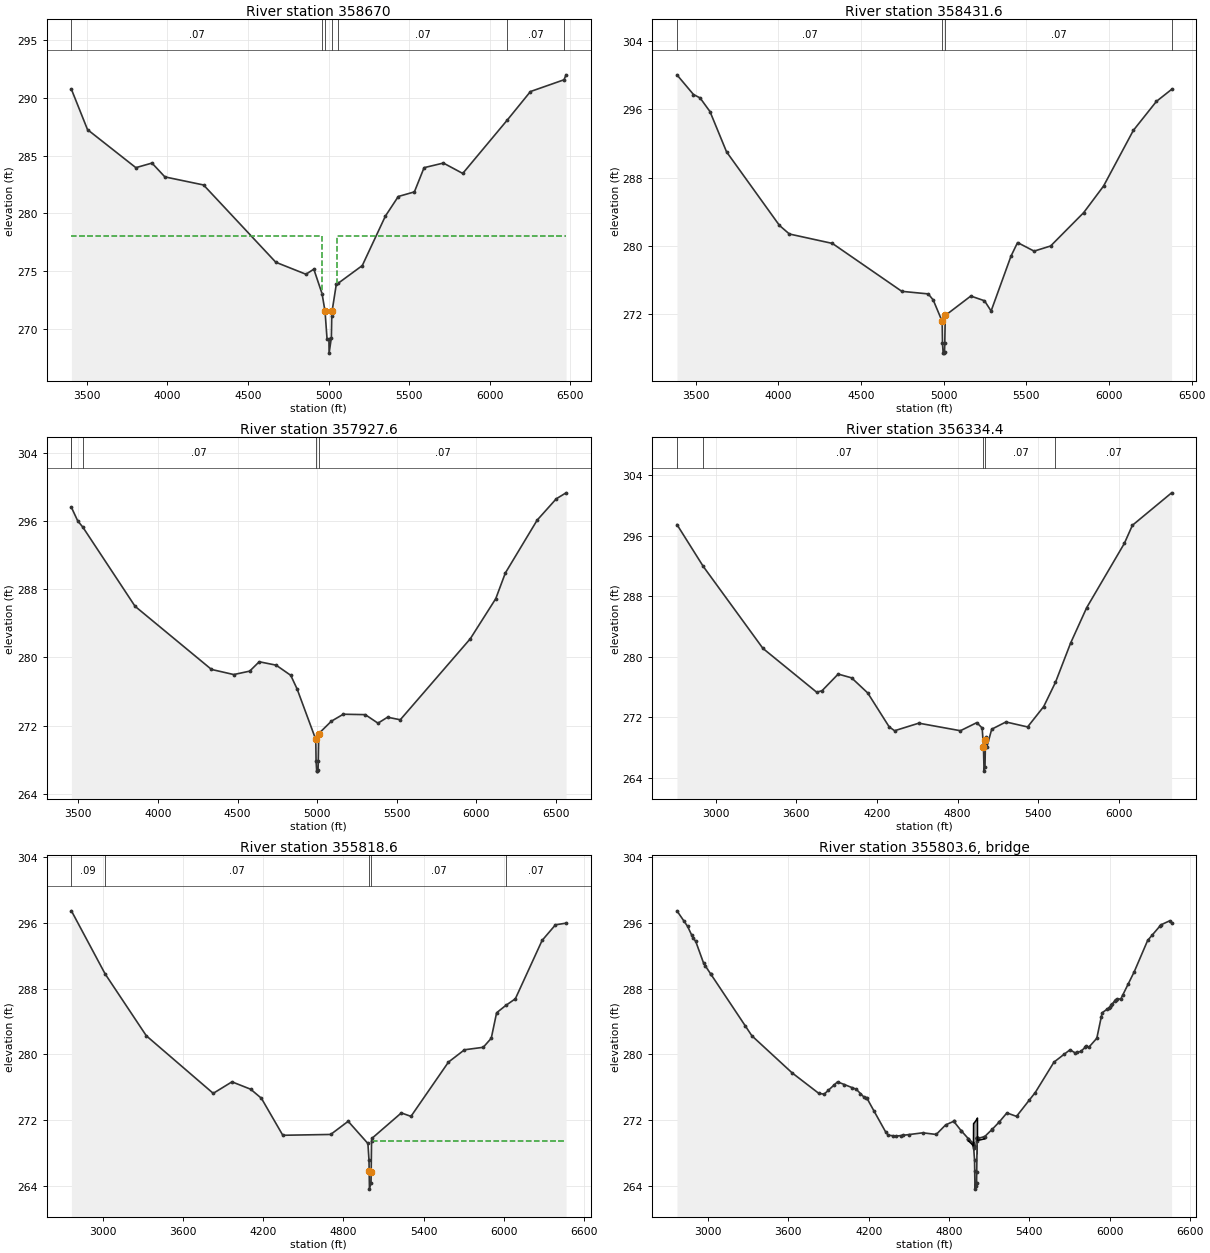
Type RM Length L Ch R = 1 ,358670  ,238.4,238.4,238.4
BEGIN DESCRIPTION:
Downstream Section of FM 1488
END DESCRIPTION:
XS GIS Cut Line= 4
    2935305.2614   13978758.6953    2934604.2481    13978110.539
    2933747.7529   13977317.3442    2933048.1197   13976678.8626
#Sta/Elev= 30
  3403.9  290.75  3503.9  287.25  3803.9  283.95  3903.9  284.35  3983.9  283.15
  4223.9  282.45  4672.1  275.75  4859.2  274.71  4908.1  275.15  4959.3  273.02
  4977.7  271.49  4990.1  269.11  5001.8  269.08  5002.9  267.87    5017  269.21
  5019.4  271.13  5021.6  271.52    5048  273.88  5059.4  273.93  5208.7  275.46
  5352.1  279.75  5432.1  281.45  5532.1  281.85  5592.1  283.95  5712.1  284.35
  5832.1  283.45  6109.7   288.1  6252.1  290.55  6460.2  291.57  6473.2     292
#Mann= 7 ,-1 , 0
  3403.9     .07       0  4959.3     .06       0  4977.7     .06       0
  5021.6     .06       0  5059.4     .07       0  6109.7     .07       0
  6460.2     .07       0
#XS Ineff= 2 , 0
       0  4959.6     278  5049.5       0     278
Permanent Ineff=
       F       F
Bank Sta=4977.7,5021.6
XS Rating Curve= 0
Exp/Cntr=.5,.3

Type RM Length L Ch R = 1 ,358431.6,518.42,504,460.44
BEGIN DESCRIPTION:
Cross Section XS288
END DESCRIPTION:
XS GIS Cut Line= 2
    2935513.8459   13978653.2828    2933318.6144   13976620.7904
#Sta/Elev= 30
  3387.1     300  3487.1   297.7  3527.1   297.3  3587.1   295.7  3687.1     291
  4007.1   282.4  4067.1   281.4  4327.1   280.3  4747.1   274.7  4907.1   274.4
    4937  273.69  4991.2  271.19  4993.1  268.64  4996.9  267.52    5001  267.48
  5005.5  267.67  5006.9  268.64    5010  271.88  5164.2  274.15  5247.1   273.6
  5287.1   272.4  5407.1   278.8  5447.1   280.4  5547.1   279.4  5647.1     280
  5847.1   283.9  5967.1     287  6147.1   293.5  6287.1   296.9  6378.8   298.3
#Mann= 4 ,-1 , 0
  3387.1     .07       0  4991.2     .06       0    5010     .07       0
  6378.8      .2       0
Bank Sta=4991.2,5010
XS Rating Curve= 0
Exp/Cntr=.3,.1

Type RM Length L Ch R = 1 ,357927.6,789.07,1593.2,1500.82
BEGIN DESCRIPTION:
Cross Section XS287
END DESCRIPTION:
XS GIS Cut Line= 3
    2935711.1355   13978454.4745    2934946.2273   13977420.4319
    2933487.2357   13976329.7294
#Sta/Elev= 30
  3455.9   297.6  3495.9     296  3527.3  295.29  3855.9     286  4335.9   278.6
  4475.9     278  4575.9   278.4  4635.9   279.5  4742.1   279.1  4833.9  277.91
  4873.9  276.31  4991.2  270.39  4993.1  267.84  4996.9  266.72    5001  266.68
  5005.5  266.87  5006.9  267.84    5010  271.08    5089  272.53  5164.2  273.35
  5302.1   273.3  5382.1   272.3  5442.1     273  5522.1   272.7  5962.1   282.2
  6122.1   286.9  6182.1   289.9  6382.1   296.1  6502.1   298.6  6563.7   299.3
#Mann= 5 , 1 , 0
  3455.9      .2       0  3455.9     .09       0  3527.3     .07       0
  4991.2     .06       0    5010     .07       0
Bank Sta=4991.2,5010
XS Rating Curve= 0
Exp/Cntr=.3,.1

Type RM Length L Ch R = 1 ,356334.4,267.14,515.8,421.58
BEGIN DESCRIPTION:
Cross Section XS286
END DESCRIPTION:
XS GIS Cut Line= 3
     2935829.582   13978484.8902    2935551.7796   13976393.4718
     2935190.573   13974863.6553
#Sta/Elev= 30
  2711.3   297.5  2906.6  291.97  3351.3   281.1  3751.3   275.3  3791.3   275.5
  3911.3   277.7  4011.3   277.2  4131.3   275.2  4291.3   270.7  4331.3   270.2
  4511.3   271.2  4821.1   270.2  4942.9  271.27    4983  270.56  4992.8  268.01
    4997  264.85    5004  265.43  5007.6  268.94  5012.2  269.35    5017     268
  5053.9   270.4  5159.8  271.36  5321.1   270.7  5441.1   273.4  5528.6  276.61
  5641.1   281.8  5761.1   286.5  6041.1     295  6101.1   297.4    6393   301.7
#Mann= 5 ,-1 , 0
  2711.3     .09       0  2906.6     .07       0  4992.8     .06       0
  5007.6     .07       0  5528.6     .07       0
Bank Sta=4992.8,5007.6
XS Rating Curve= 0
Exp/Cntr=.5,.3

Type RM Length L Ch R = 1 ,355818.6,30,30,30
BEGIN DESCRIPTION:
Upstream Section of Wood Bridge Access DS FM 1488
END DESCRIPTION:
XS GIS Cut Line= 4
    2935957.7305   13978544.5051    2935949.6386   13976330.8976
    2935965.1238   13976294.5076    2935924.4865   13974850.9233
#Sta/Elev= 30
  2767.1  297.46  3019.1  289.79  3327.1  282.26  3827.1  275.26  3967.1  276.66
  4107.1  275.76  4187.1  274.66  4347.1  270.16  4704.9  270.26  4835.5  271.86
  4983.1  269.16  4991.3  267.11  4992.5  265.78  4994.6  263.61  5006.4   264.4
  5007.5  265.73  5010.3  269.44  5012.1  269.77  5232.8  272.88  5304.9  272.46
  5584.9  279.06  5704.9  280.56  5844.9  280.86  5904.9  281.96  5944.9  285.06
  6013.3  285.95  6084.9  286.76  6284.9  293.86  6384.9  295.76    6464  295.96
#Mann= 5 ,-1 , 0
  2767.1     .09       0  3019.1     .07       0  4992.5     .06       0
  5007.5     .07       0  6013.3     .07       0
#XS Ineff= 2 , 0
       0  4984.1   268.9  5010.3       0   269.5
Permanent Ineff=
       F       F
Bank Sta=4992.5,5007.5
XS Rating Curve= 0
Exp/Cntr=.5,.3

Type RM Length L Ch R = 3 ,355803.6,,,
BEGIN DESCRIPTION:
WOOD BRIDGE ACCESS DS FM1488
Structure ID: J100-00-00-21
Circular piers, twin-cylinder piers without diaphragm
END DESCRIPTION:
Node Name=1st DS FM 1488
Bridge Culvert--1,0,-1,-1, 0
Deck Dist Width WeirC Skew NumUp NumDn MinLoCord MaxHiCord MaxSubmerge Is_Ogee
10,10,2.6,0, 24, 24, , , .95, 0, 1,1,,
  4945.7  4945.8  4983.1  4983.2  4983.9 4984.01  4984.1  4984.2    4985  4991.3
  4992.5  4994.6  4998.8  5001.7  5006.4  5007.5  5010.3  5012.1  5012.9 5012.99
  5013.1  5013.2  5013.3  5065.5
  269.46  269.47  268.91  268.88  271.57  271.57  271.57  271.58  271.59  271.72
  271.74  271.79  271.87  271.95  272.07   272.1  272.17  272.22  272.24  272.24
  272.25  272.25  269.52  269.72
  269.46  269.47   268.9  268.87  268.65  268.61  268.58  268.58  268.59  268.72
  268.74  268.79  268.87  268.95  269.07   269.1  269.18  269.51  269.51  269.51
  269.51  269.51  269.51  269.72
  4945.7  4945.8  4983.1  4983.2  4983.9 4984.01  4984.1  4984.2    4985  4991.3
  4992.5  4994.6  4998.8  5001.7  5006.4  5007.5  5010.3  5012.1  5012.9 5012.99
  5013.1  5013.2  5013.3  5065.5
  269.46  269.47  268.91  268.88  271.57  271.57  271.57  271.58  271.59  271.72
  271.74  271.79  271.87  271.95  272.07   272.1  272.17  272.22  272.24  272.24
  272.25  272.25  269.52  269.72
  269.46  269.47   268.9  268.87  268.65  268.61  268.58  268.58  268.59  268.72
  268.74  268.79  268.87  268.95  269.07   269.1  269.18  269.51  269.51  269.51
  269.51  269.51  269.51  269.72
Pier Skew, UpSta & Num, DnSta & Num=  ,4986, 2 ,4986, 2 , 0 , 0 , 0 ,,
       1       1
  266.95  269.62
       1       1
  266.95  269.62
Pier Skew, UpSta & Num, DnSta & Num=  ,5009.1, 2 ,5009.1, 2 , 0 , 0 , 0 ,,
       1       1
  265.93  270.16
       1       1
  265.93  270.16
BR Coef= 1 , 1 , 1 ,1.05, 0 ,,,.8,0,1.2,0,
WSPro=,,,, 1 ,,,, 0 ,,,, 0 ,,,,-1 ,-1 ,-1 , 0 , 0 , 0 , 0 , 0
BR U #Sta/Elev= 103
  2767.1  297.46  2818.5  296.24  2847.1  295.56  2878.5  294.46  2887.1  294.16
  2907.1  293.76  2967.1  291.06  2978.5  290.78  3018.5   289.8  3019.1  289.79
  3278.5  283.45  3327.1  282.26  3627.1  277.76  3827.1  275.26  3867.1  275.16
  3898.5  275.63  3938.5  276.23  3967.1  276.66  4018.5  276.33  4078.5  275.94
  4107.1  275.76  4138.5  275.24  4167.1  274.76  4178.5   274.7  4187.1  274.66
  4238.5  273.15  4327.1  270.56  4347.1  270.16  4378.5  270.11  4407.1  270.06
  4438.5  270.12  4458.5  270.16  4498.5  270.24  4604.9  270.46  4704.9  270.26
    4775  271.42  4835.5  271.86  4836.7  271.84  4890.5  270.73  4891.3  270.72
  4945.7  269.73  4945.8  269.73  4983.1  269.16  4983.2  269.13  4983.9  268.91
 4984.01  268.87  4984.1  268.84  4984.2  268.81    4985  268.56  4991.3  267.11
  4992.5  265.78  4994.6  263.61  4998.8  264.02  5001.7   264.3  5006.4   264.4
  5007.5  265.73  5010.3  269.44  5012.1  269.77  5012.9  269.77 5012.99  269.77
  5013.1  269.77  5013.2  269.77  5013.3  269.77  5065.5  269.99  5066.4  269.99
  5120.7  270.85  5122.2  270.87    5176  271.78  5177.1   271.8  5232.8  272.88
  5304.9  272.46  5398.9  274.41  5444.9  275.36  5584.9  279.06  5658.9  279.99
  5704.9  280.56  5744.9  280.16  5758.9  280.23  5784.9  280.36  5818.9  280.87
  5824.9  280.96  5844.9  280.86  5904.9  281.96  5938.9   284.6  5944.9  285.06
  5978.9  285.46  5998.9  285.69  6004.9  285.76  6013.3  285.95  6018.9  286.08
  6038.9  286.52  6044.9  286.66  6058.9   286.7  6084.9  286.76  6098.9  287.22
  6138.9  288.54  6184.9  290.06  6284.9  293.86  6318.9  294.51  6378.9  295.65
  6384.9  295.76  6451.2  296.26    6464  295.96
BR U #Mann= 5
  2767.1     .09  3019.1     .07  4992.5    .055  5007.5     .07  6013.3     .07
BR D #Sta/Elev= 103
  2767.1  297.19  2818.5  295.97  2847.1  295.29  2878.5  294.19  2887.1  293.89
  2907.1  293.49  2967.1  290.79  2978.5  290.51  3018.5  289.53  3019.1  289.52
  3278.5  283.18  3327.1  281.99  3627.1  277.49  3827.1  274.99  3867.1  274.89
  3898.5  275.36  3938.5  275.96  3967.1  276.39  4018.5  276.06  4078.5  275.67
  4107.1  275.49  4138.5  274.97  4167.1  274.49  4178.5  274.43  4187.1  274.39
  4238.5  272.88  4327.1  270.29  4347.1  269.89  4378.5  269.84  4407.1  269.79
  4438.5  269.85  4458.5  269.89  4498.5  269.97  4604.9  270.19  4704.9  269.99
    4775  271.15  4835.5  271.59  4836.7  271.57  4890.5  270.46  4891.3  270.45
  4945.7  269.46  4945.8  269.46  4983.1  268.89  4983.2  268.86  4983.9  268.64
 4984.01   268.6  4984.1  268.57  4984.2  268.54    4985  268.29  4991.3  266.84
  4992.5  265.51  4994.6  263.34  4998.8  263.75  5001.7  264.03  5006.4  264.13
  5007.5  265.46  5010.3  269.17  5012.1   269.5  5012.9   269.5 5012.99   269.5
  5013.1   269.5  5013.2   269.5  5013.3   269.5  5065.5  269.72  5066.4  269.72
  5120.7  270.58  5122.2   270.6    5176  271.51  5177.1  271.53  5232.8  272.61
  5304.9  272.19  5398.9  274.14  5444.9  275.09  5584.9  278.79  5658.9  279.72
  5704.9  280.29  5744.9  279.89  5758.9  279.96  5784.9  280.09  5818.9   280.6
  5824.9  280.69  5844.9  280.59  5904.9  281.69  5938.9  284.33  5944.9  284.79
  5978.9  285.19  5998.9  285.42  6004.9  285.49  6013.3  285.68  6018.9  285.81
  6038.9  286.25  6044.9  286.39  6058.9  286.43  6084.9  286.49  6098.9  286.95
  6138.9  288.27  6184.9  289.79  6284.9  293.59  6318.9  294.24  6378.9  295.38
  6384.9  295.49  6451.2  295.99    6464  295.69
BR D #Mann= 5
  2767.1     .09  3019.1     .07  4992.5    .055  5007.5     .07  6013.3     .07
BC Design=,, 0 ,, 0 ,,,,,,
BC HTab HWMax=297.46