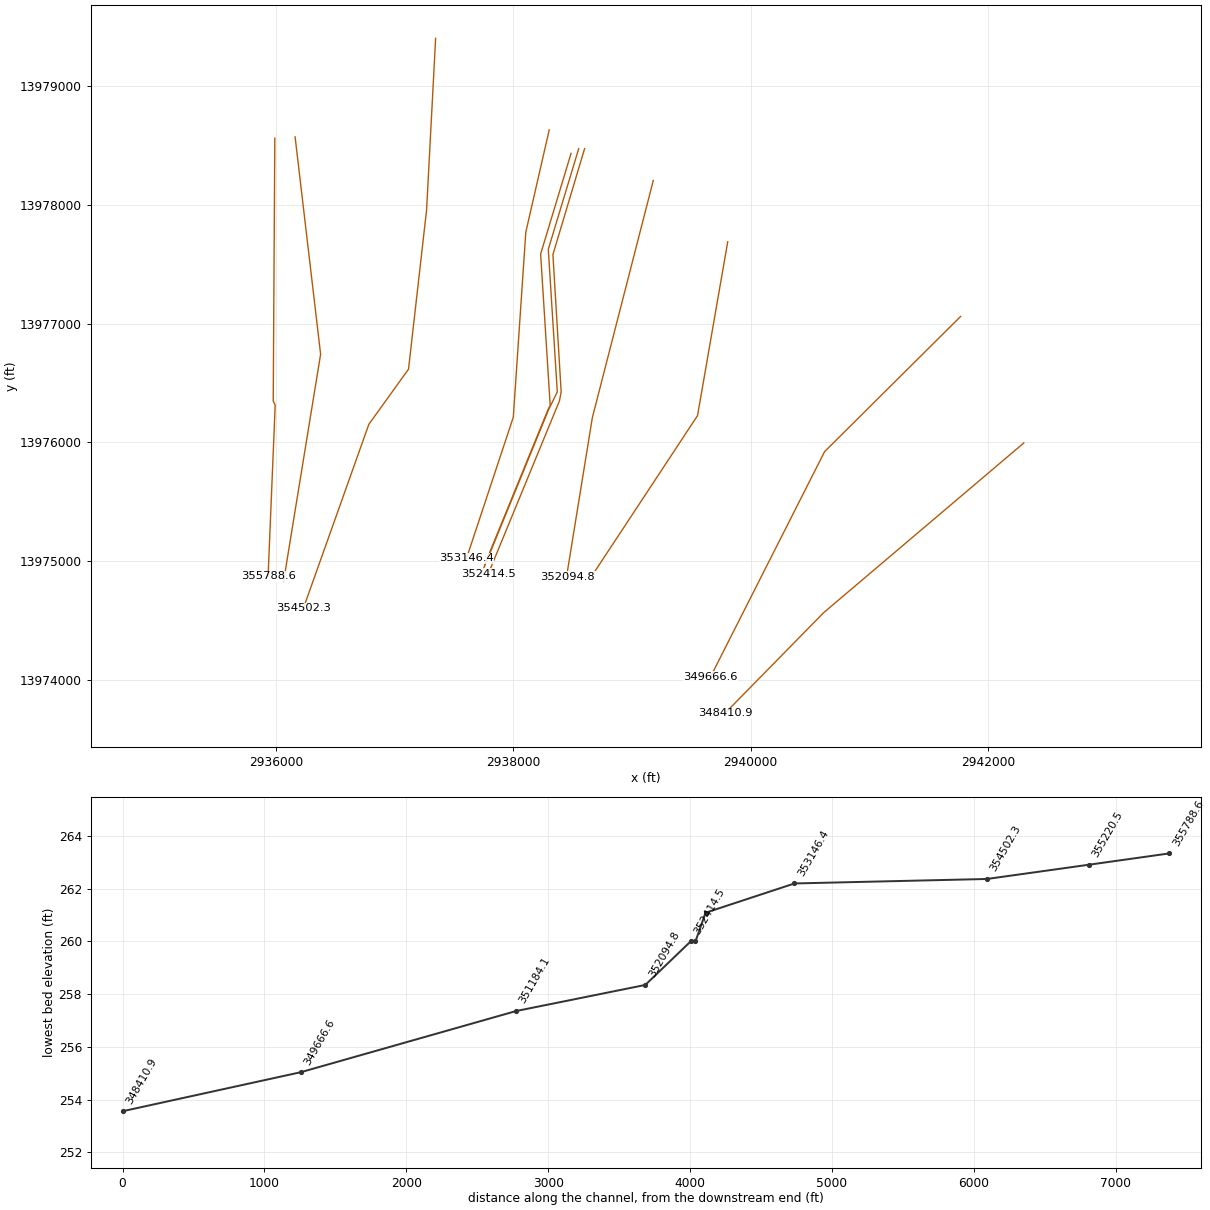
HEC-RAS study J100-00-00.prj: J100-00-00

--- J100-00-00.g01 (geometry) --- (continued)

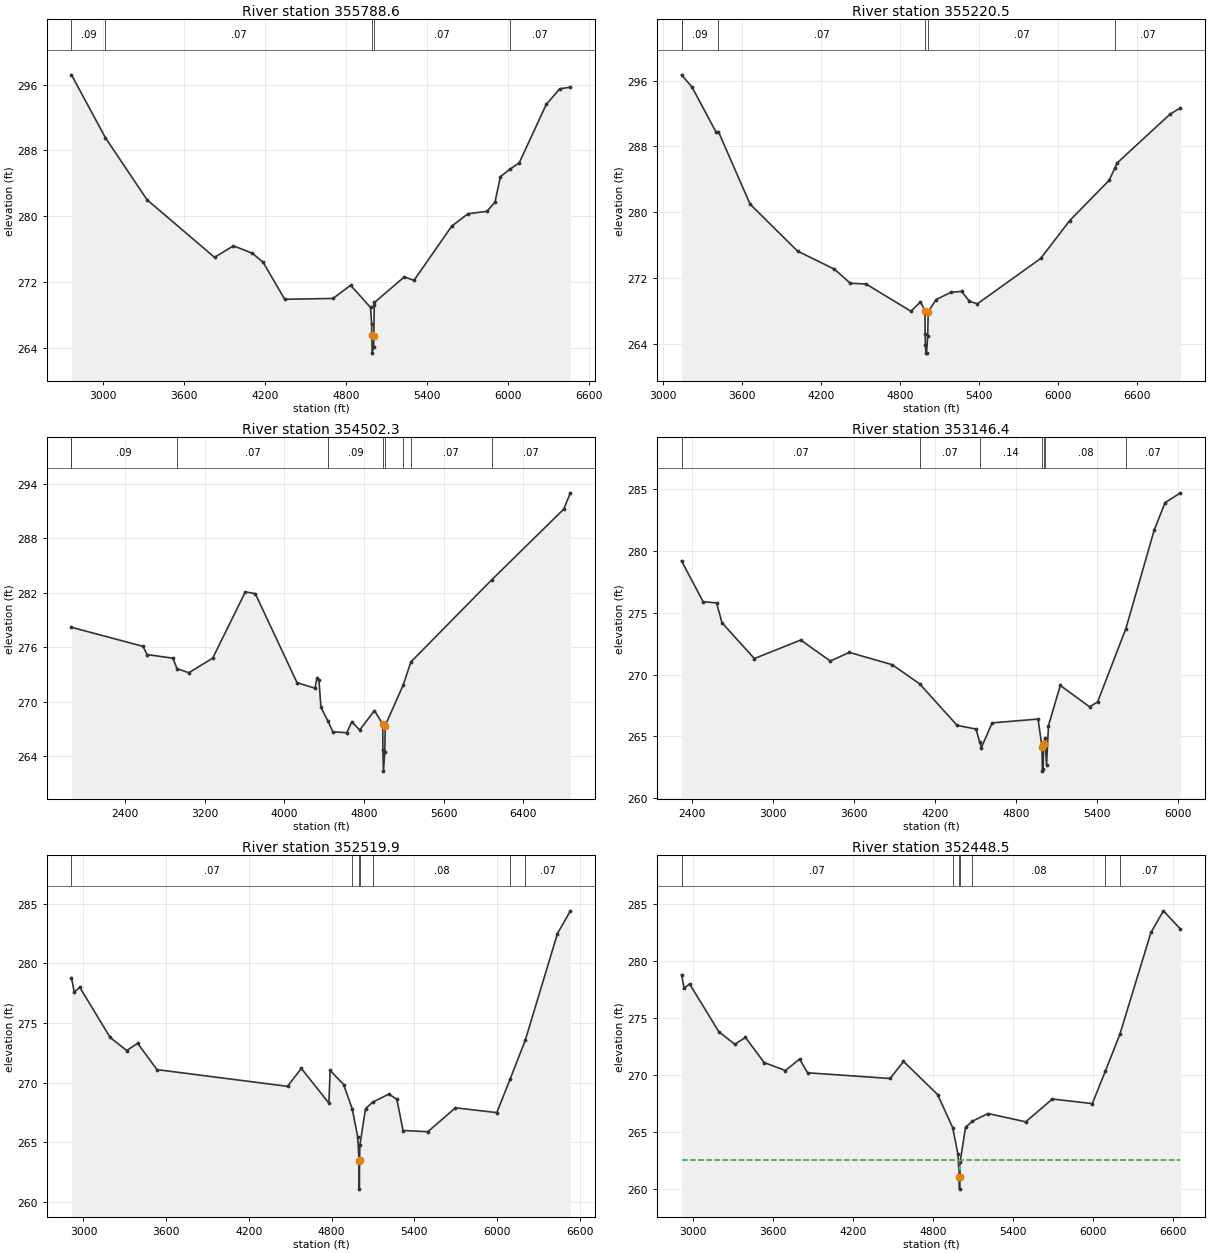
Type RM Length L Ch R = 1 ,355788.6,568.1,568.1,568.1
BEGIN DESCRIPTION:
Downstream Section of Wood Bridge Access DS FM 1488
END DESCRIPTION:
XS GIS Cut Line= 4
    2935990.5525   13978562.1549     2935977.139    13976346.337
     2935993.774   13976313.0671    2935933.8448   13974870.5604
#Sta/Elev= 30
  2767.1  297.19  3019.1  289.52  3327.1  281.99  3827.1  274.99  3967.1  276.39
  4107.1  275.49  4187.1  274.39  4347.1  269.89  4704.9  269.99  4835.5  271.59
  4983.1  268.89  4991.3  266.84  4992.5  265.51  4994.6  263.34  5006.4  264.13
  5007.5  265.46  5010.3  269.17  5012.1   269.5  5232.8  272.61  5304.9  272.19
  5584.9  278.79  5704.9  280.29  5844.9  280.59  5904.9  281.69  5944.9  284.79
  6013.3  285.68  6084.9  286.49  6284.9  293.59  6384.9  295.49    6464  295.69
#Mann= 5 ,-1 , 0
  2767.1     .09       0  3019.1     .07       0  4992.5     .06       0
  5007.5     .07       0  6013.3     .07       0
#XS Ineff= 2 , 0
       0  4984.1   267.9  5010.3       0   268.5
Permanent Ineff=
       F       F
Bank Sta=4992.5,5007.5
XS Rating Curve= 0
Exp/Cntr=.5,.3

Type RM Length L Ch R = 1 ,355220.5,835.64,718.2,535.65
BEGIN DESCRIPTION:
Cross Section XS285.5
END DESCRIPTION:
XS GIS Cut Line= 3
    2936161.3781   13978573.3368    2936376.4904   13976741.4126
    2936064.2306   13974826.2192
#Sta/Elev= 30
  3142.2   296.7  3222.2   295.2  3402.2   289.8  3422.2   289.8  3662.2     281
  4022.2   275.3  4302.2   273.1  4422.2   271.4  4542.2   271.3  4882.2     268
    4955  269.13  4989.1  268.07  4990.4  265.22  4992.4  263.93  4996.2  262.91
  5000.6  262.96  5009.7     265  5013.5  267.92  5072.7   269.4  5186.7   270.3
  5266.7   270.4  5326.7   269.2  5386.7   268.9  5866.7   274.4  6086.7     279
  6386.7   283.9  6429.7   285.4  6446.7     286  6846.7   291.9  6927.2   292.7
#Mann= 6 , 1 , 0
  3142.2      .2       0  3142.2     .09       0  3422.2     .07       0
  4989.1     .06       0  5013.5     .07       0  6429.7     .07       0
Bank Sta=4989.1,5013.5
XS Rating Curve= 0
Exp/Cntr=.3,.1

Type RM Length L Ch R = 1 ,354502.3,911.19,1355.9,1130.68
BEGIN DESCRIPTION:
Cross Section XS285
END DESCRIPTION:
XS GIS Cut Line= 5
     2937345.704   13979403.3507    2937269.4854   13977956.8072
    2937117.1745   13976615.0207    2936783.3679   13976151.7326
    2936230.8298   13974599.3638
#Sta/Elev= 30
  1858.7   278.2  2578.7   276.1  2618.7   275.2  2878.7   274.8  2919.6  273.65
  3038.7   273.2  3278.7   274.8  3607.3   282.1  3707.3   281.9  4127.3   272.1
  4307.3   271.5  4327.3   272.6  4347.3   272.4  4367.3   269.4  4438.6  267.86
  4487.3   266.7  4627.3   266.6  4677.7   267.8  4757.7   266.9    4906  269.04
  4989.1  267.53  4990.4  264.68  4996.2  262.37  5009.7  264.46  5013.5  267.38
  5195.5  271.87  5272.2  274.39  6084.4  283.42  6808.7   291.2  6876.4     293
#Mann= 9 , 1 , 0
  1858.7      .2       0  1858.7     .09       0  2919.6     .07       0
  4438.6     .09       0  4989.1     .06       0  5013.5     .09       0
  5195.5     .08       0  5272.2     .07       0  6084.4     .07       0
Bank Sta=4989.1,5013.5
XS Rating Curve= 0
Exp/Cntr=.3,.1

Type RM Length L Ch R = 1 ,353146.4,243.38,626.5,264.21
BEGIN DESCRIPTION:
Cross Section XS284
END DESCRIPTION:
XS GIS Cut Line= 4
    2938302.8923   13978631.6596    2938105.5486   13977769.9252
    2938000.2986   13976210.9096    2937605.6111    13975020.269
#Sta/Elev= 30
  2320.6   279.2  2480.6   275.9  2580.6   275.8  2620.6   274.2  2860.6   271.3
  3204.6   272.8  3424.6   271.1  3564.6   271.8  3884.6   270.8  4087.4  269.25
  4364.6   265.9  4504.6   265.6  4532.6  264.55  4544.6   264.1  4624.6   266.1
  4965.4  266.41  4993.9  264.19  4997.8   262.2  5002.5  262.34  5007.3  264.37
  5016.6  264.84  5028.2  262.73  5042.6  265.88  5130.1  269.13  5347.2   267.4
  5407.2   267.8  5616.9  273.73  5827.2   281.7  5907.2   283.9  6021.6   284.7
#Mann= 7 ,-1 , 0
  2320.6     .07       0  4087.4     .07       0  4532.6     .14       0
  4993.9     .06       0  5007.3     .14       0  5016.6     .08       0
  5616.9     .07       0
Bank Sta=4993.9,5007.3
XS Rating Curve= 0
Exp/Cntr=.3,.1

Type RM Length L Ch R = 1 ,352519.9,71.4,71.4,71.4
BEGIN DESCRIPTION:
Upstream of ACCESS CONC. BRDG 2ND DS FM 1488
END DESCRIPTION:
XS GIS Cut Line= 5
    2938487.0798   13978434.3159     2938230.533   13977585.7377
    2938311.0131   13976310.4367    2938293.6349   13976276.0723
    2937758.5452   13974966.4464
#Sta/Elev= 30
  2913.2   278.8  2933.2   277.6  2973.2     278  3193.2   273.8  3313.2   272.7
  3393.2   273.3  3533.2   271.1  4479.7   269.7  4579.7   271.2  4779.7   268.3
    4789  271.03  4886.5  269.85  4949.2  267.81  4988.8  265.47  4998.4  263.47
  5000.4  261.09  5002.1   263.5  5004.8   264.8  5045.5  267.83  5096.6  268.37
  5214.5  269.05    5273  268.61  5317.5     266  5497.5   265.9  5697.5   267.9
  5997.5   267.5  6095.1  270.34  6203.8  273.56  6437.5   282.5  6531.3   284.4
#Mann= 7 ,-1 , 0
  2913.2     .07       0  4949.2     .14       0  4998.4     .06       0
  5002.1     .14       0  5096.6     .08       0  6095.1     .15       0
  6203.8     .07       0
Bank Sta=4998.4,5002.1
XS Rating Curve= 0
Exp/Cntr=.5,.3

Type RM Length L Ch R = 1 ,352448.5,34,34,34
BEGIN DESCRIPTION:
Upstream Section of Access Conc Bridge-2nd DS FM 1488
END DESCRIPTION:
XS GIS Cut Line= 5
    2938551.1101   13978472.5036     2938295.142   13977625.8399
     2938370.974   13976424.1955    2938296.2561   13976271.3976
    2937732.9208   13974893.9282
#Sta/Elev= 30
  2913.2   278.8  2933.2   277.6  2973.2     278  3193.2   273.8  3313.2   272.7
  3393.2   273.3  3533.2   271.1  3693.2   270.4  3799.7   271.4  3859.7   270.2
  4479.7   269.7  4579.7   271.2  4835.9  268.29  4949.2  265.39  4988.8  263.05
  4998.4  261.05  5000.4     260  5002.1  261.08  5004.8  262.38  5045.5  265.41
  5096.6  265.95  5214.5  266.63  5497.5   265.9  5697.5   267.9  5997.5   267.5
  6095.1  270.34  6203.8  273.56  6437.5   282.5  6531.3   284.4  6659.3   282.8
#Mann= 7 ,-1 , 0
  2913.2     .07       0  4949.2     .14       0  4998.4     .06       0
  5002.1     .14       0  5096.6     .08       0  6095.1     .15       0
  6203.8     .07       0
#XS Ineff= 2 , 0
       0    4998  262.55    5002       0  262.55
Permanent Ineff=
       F       F
Bank Sta=4998.4,5002.1
XS Rating Curve= 0
Exp/Cntr=.5,.3

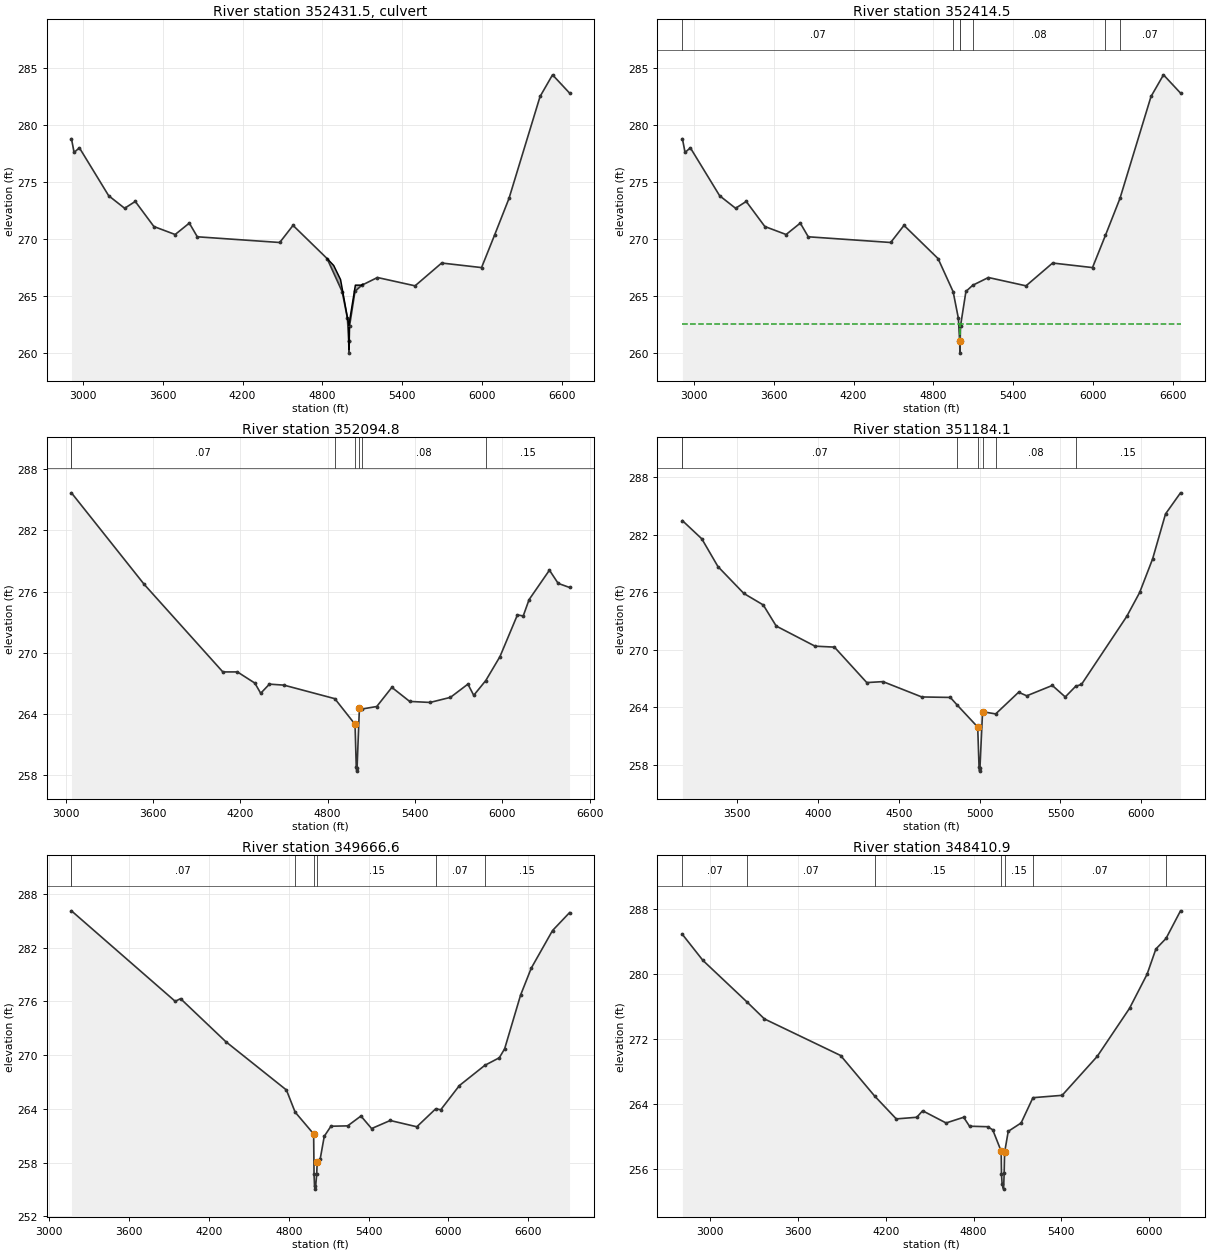
Type RM Length L Ch R = 2 ,352431.5,,,
BEGIN DESCRIPTION:
ACCESS CONC. BRDG 2ND DS FM 1488
Structure ID: J100-00-00-20
END DESCRIPTION:
Node Name=2nd DS FM 1488
Bridge Culvert--1,0,-1,-1, 0
Deck Dist Width WeirC Skew NumUp NumDn MinLoCord MaxHiCord MaxSubmerge Is_Ogee
10,14,3,0, 18, 18, , , .95, 0, 1,1,,
  4835.9  4885.7  4886.5    4937  4937.5  4949.2  4988.8  4997.9  4998.4  4999.6
  5000.4  5001.9  5002.1  5004.8  5045.5  5048.5  5096.6  5105.8
  268.29  267.68  267.66  266.45  266.42  265.67  263.12  262.54  262.51  262.43
  262.49   262.6  262.61  262.81  265.74  265.96  265.96  266.05
                                                                                
                                                                
  4835.9  4885.7  4886.5    4937  4937.5  4949.2  4988.8  4997.9  4998.4  4999.6
  5000.4  5001.9  5002.1  5004.8  5045.5  5048.5  5096.6  5105.8
  268.29  267.68  267.66  266.45  266.42  265.67  263.12  262.54  262.51  262.43
  262.49   262.6  262.61  262.81  265.74  265.96  265.96  266.05
                                                                                
                                                                
BR Coef= 1 , 1 , 0 ,1.25, 0 ,,,.8,-1,2,0,
WSPro=,,,, 1 ,,,, 0 ,,,, 0 ,,,,-1 ,-1 ,-1 , 0 , 0 , 0 , 0 , 0
Culvert=1,2,,14,.015,.4,1,1,3,260.3,5000.3,260.21,5000.3,Culvert #1  , 0 ,10
Culvert Bottom n=.015
BC Design=,, 0 ,, 0 ,,,,,,
BC HTab HWMax=284.4

Type RM Length L Ch R = 1 ,352414.5,319.7,319.7,319.7
BEGIN DESCRIPTION:
Downstream Section of Access Conc Bridge-2nd DS FM 1488
END DESCRIPTION:
XS GIS Cut Line= 6
    2938600.9644   13978473.3334    2938334.0829   13977581.3875
    2938392.5347   13976607.1908    2938403.5149   13976424.1874
    2938389.0927   13976347.8513    2937788.5332   13974888.8291
#Sta/Elev= 30
  2913.2   278.8  2933.2   277.6  2973.2     278  3193.2   273.8  3313.2   272.7
  3393.2   273.3  3533.2   271.1  3693.2   270.4  3799.7   271.4  3859.7   270.2
  4479.7   269.7  4579.7   271.2  4835.9  268.29  4949.2  265.39  4988.8  263.05
  4998.4  261.05  5000.4     260  5002.1  261.08  5004.8  262.38  5045.5  265.41
  5096.6  265.95  5214.5  266.63  5497.5   265.9  5697.5   267.9  5997.5   267.5
  6095.1  270.34  6203.8  273.56  6437.5   282.5  6531.3   284.4  6659.3   282.8
#Mann= 7 ,-1 , 0
  2913.2     .07       0  4949.2     .14       0  4998.4     .06       0
  5002.1     .14       0  5096.6     .08       0  6095.1     .15       0
  6203.8     .07       0
#XS Ineff= 2 , 0
       0    4998  262.55    5002       0  262.55
Permanent Ineff=
       F       F
Bank Sta=4998.4,5002.1
XS Rating Curve= 0
Exp/Cntr=.5,.3

Type RM Length L Ch R = 1 ,352094.8,856.47,910.7,617.04
BEGIN DESCRIPTION:
Cross Section XS283.5
END DESCRIPTION:
XS GIS Cut Line= 4
    2939179.8895   13978205.5641    2938666.3956   13976207.1014
    2938451.2833   13974881.7321    2938458.2224   13974867.8539
#Sta/Elev= 30
  3040.1   285.7  3540.1   276.7  4080.1   268.1  4180.1   268.1  4300.1     267
  4340.1     266  4400.1   266.9  4500.1   266.8  4849.3  265.47  4988.2  262.95
  4996.5  258.78  4999.6  258.35    5002  258.64  5018.2  264.55  5033.6  264.45
  5137.3   264.7  5241.1  266.58  5363.5   265.2  5503.5   265.1  5643.5   265.6
  5763.5   266.9  5803.5   265.8  5886.1  267.25  5983.5   269.6  6103.5   273.7
  6143.5   273.6  6183.5   275.2  6323.5   278.1  6383.5   276.8  6461.7   276.4
#Mann= 7 , 1 , 0
  3040.1      .2       0  3040.1     .07       0  4849.3     .14       0
  4988.2     .06       0  5018.2     .14       0  5033.6     .08       0
  5886.1     .15       0
Bank Sta=4988.2,5018.2
XS Rating Curve= 0
Exp/Cntr=.3,.1

Type RM Length L Ch R = 1 ,351184.1,1179.61,1517.5,1186.28
BEGIN DESCRIPTION:
Cross Section XS283
END DESCRIPTION:
XS GIS Cut Line= 3
     2939807.301   13977689.4556    2939552.7361   13976224.0659
    2938676.3169   13974894.3092
#Sta/Elev= 30
  3162.3   283.5  3282.3   281.6  3382.3   278.7  3542.3   275.9  3662.3   274.7
  3742.3   272.5  3982.3   270.4  4102.3   270.3  4302.3   266.6  4402.3   266.7
  4642.3   265.1    4819  265.05  4858.9   264.3  4988.2  261.96  4996.5  257.79
  4999.6  257.36    5002  257.65  5018.2  263.56  5099.4  263.33  5241.1  265.59
  5291.5  265.22  5449.6   266.3  5529.6   265.1  5594.3  266.22  5629.6   266.4
  5909.6   273.5  5989.6     276  6069.6   279.5  6149.6   284.2  6242.2   286.4
#Mann= 7 , 1 , 0
  3162.3      .2       0  3162.3     .07       0  4858.9     .14       0
  4988.2     .06       0  5018.2     .14       0  5099.4     .08       0
  5594.3     .15       0
Bank Sta=4988.2,5018.2
XS Rating Curve= 0
Exp/Cntr=.3,.1

Type RM Length L Ch R = 1 ,349666.6,1199.65,1255.7,647.48
BEGIN DESCRIPTION:
Cross Section XS282
END DESCRIPTION:
XS GIS Cut Line= 3
    2941769.5642   13977059.4877    2940623.2252   13975920.2733
    2939661.8887   13974021.8357
#Sta/Elev= 30
  3166.5   286.1  3946.5     276  3986.5   276.3  4326.5   271.5  4782.6   266.1
  4847.6  263.64    4987   261.2    4990  256.72  4993.7  255.36  5000.3  255.04
  5009.9   256.7  5013.6  258.02  5035.9  258.37  5066.9  260.94    5117  262.06
  5242.6   262.1  5342.6   263.2  5422.6   261.8  5562.6   262.7  5762.6     262
  5904.2     264  5942.6   263.9  6082.6   266.6  6274.1  268.86  6382.6   269.7
  6422.6   270.7  6542.6   276.7  6622.6   279.7  6782.6   283.9  6910.6   285.9
#Mann= 7 , 1 , 0
  3166.5      .2       0  3166.5     .07       0  4847.6     .15       0
    4987     .06       0  5013.6     .15       0  5904.2     .07       0
  6274.1     .15       0
Bank Sta=4987,5013.6
XS Rating Curve= 0
Exp/Cntr=.3,.1

Type RM Length L Ch R = 1 ,348410.9,924.2,924.2,924.2
BEGIN DESCRIPTION:
Cross Section XS281
END DESCRIPTION:
XS GIS Cut Line= 3
    2942302.3923   13975993.8315    2940615.1468   13974563.0924
    2939783.0656   13973714.8543
#Sta/Elev= 30
  2812.6   284.9  2952.6   281.7  3252.1  276.61  3372.6   274.5  3892.6     270
  4125.1  265.01  4272.6   262.2  4412.6   262.4  4452.6   263.2  4612.6   261.7
  4732.6   262.4  4772.6   261.3  4895.9  261.24    4931  260.86  4988.7  258.23
  4990.8  255.45  4995.4  254.14  5005.1  253.56  5009.1  255.51  5012.2  258.08
  5036.9  260.67  5124.8   261.7  5205.6  264.81  5404.8   265.1  5644.8   269.9
  5864.8   275.8  5984.8     280  6044.8   283.1  6114.4  284.41    6213   287.8
#Mann= 7 ,-1 , 0
  2812.6     .07       0  3252.1     .07       0  4125.1     .15       0
  4988.7     .06       0  5012.2     .15       0  5205.6     .07       0
  6114.4     .15       0
Bank Sta=4988.7,5012.2
XS Rating Curve= 0
Exp/Cntr=.3,.1