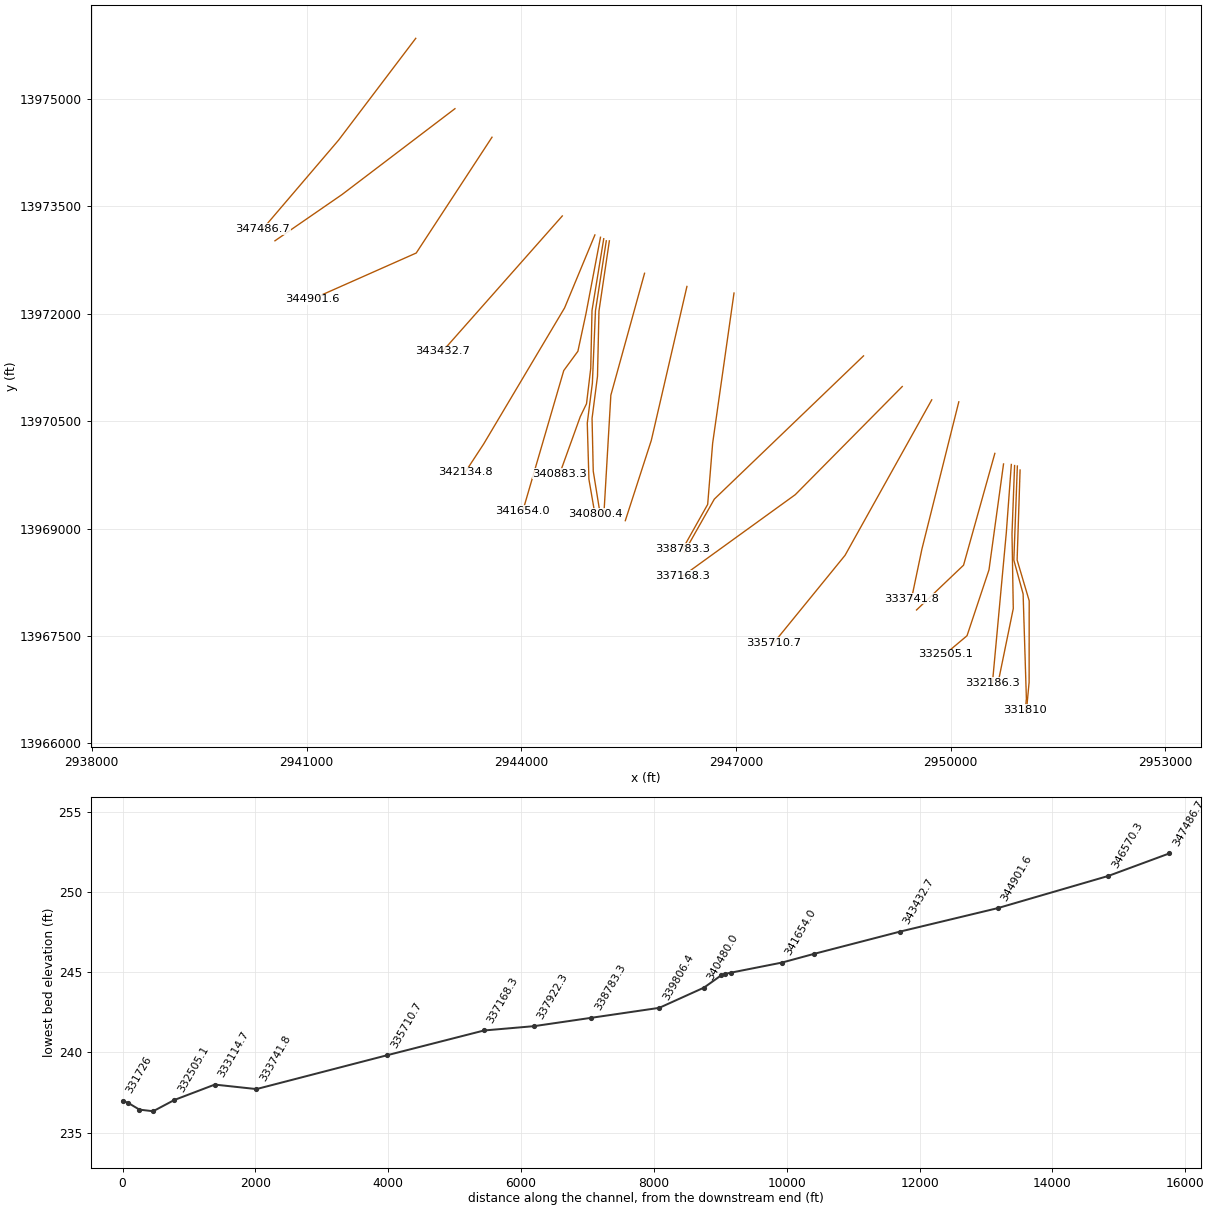
HEC-RAS study J100-00-00.prj: J100-00-00

--- J100-00-00.g01 (geometry) --- (continued)

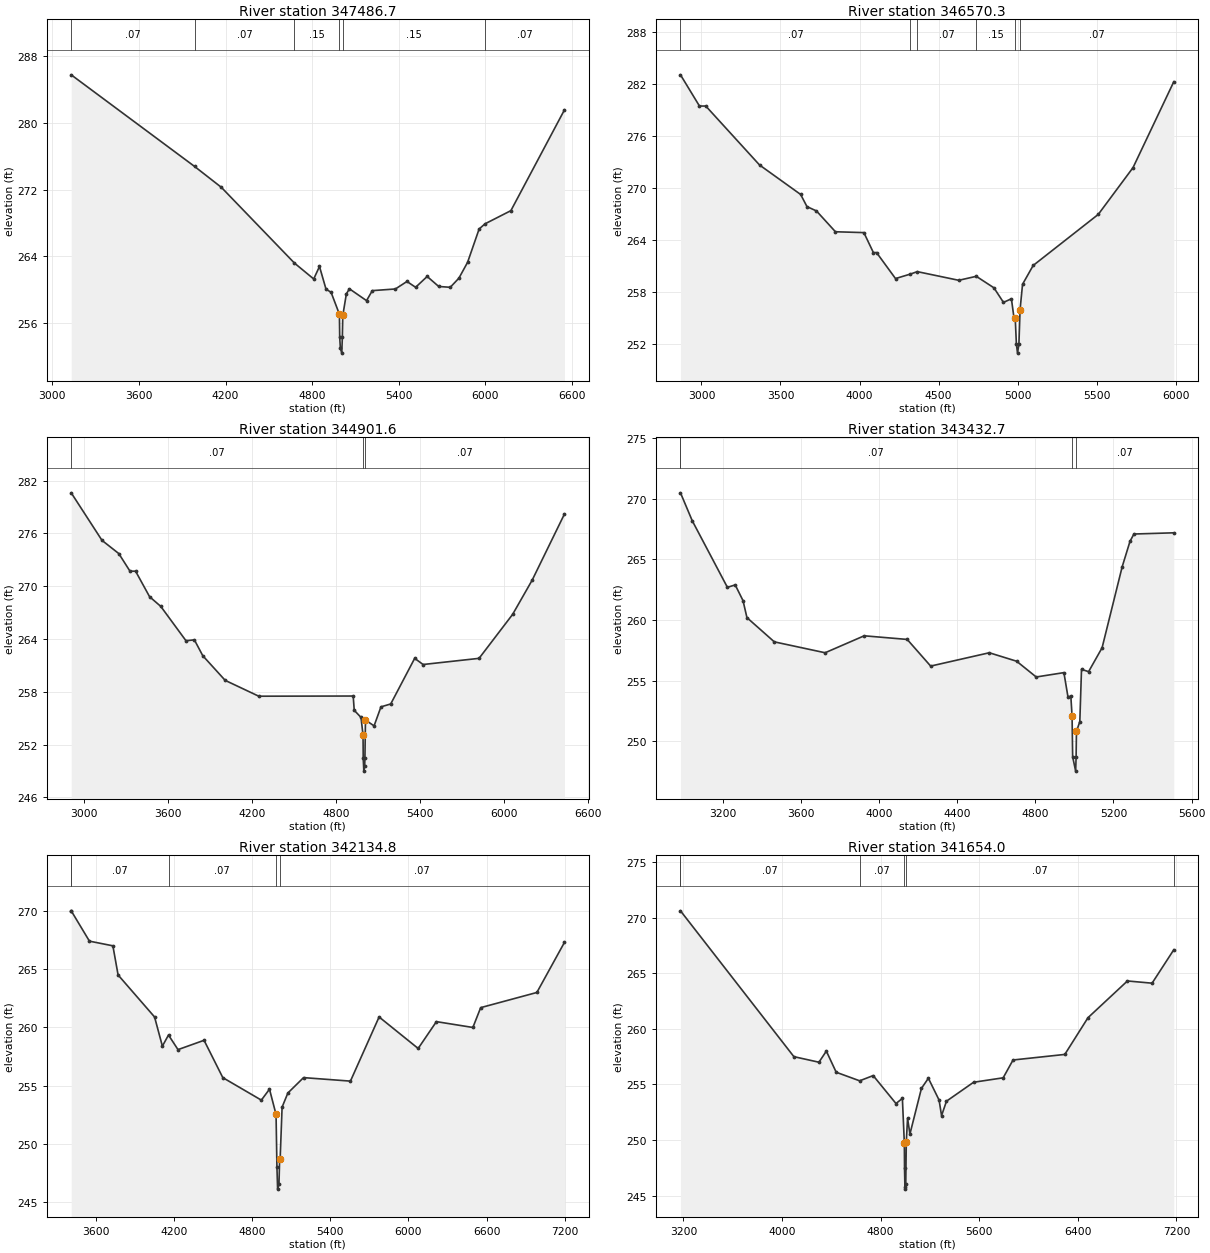
Type RM Length L Ch R = 1 ,347486.7,916.4,916.4,916.4
BEGIN DESCRIPTION:
Cross Section XS280
END DESCRIPTION:
XS GIS Cut Line= 3
    2942526.0486   13975849.1127    2941447.2279   13974425.7586
     2940388.158   13973184.9721
#Sta/Elev= 30
  3130.7   285.8  3985.7   274.8  4170.7   272.3    4677  263.21  4810.7   261.3
  4850.7   262.8  4895.9  260.08    4931   259.7  4988.7  257.07  4990.8  254.29
  4995.4  252.98  5005.1   252.4  5009.1  254.35  5012.2  256.92  5036.9  259.51
    5058  260.12  5176.7   258.7  5216.7   259.9  5376.7   260.1  5456.7     261
  5516.7   260.3  5596.7   261.6  5676.7   260.4  5756.7   260.3  5816.7   261.4
  5876.7   263.3  5956.7   267.3  5997.7  267.92  6176.7   269.5    6548   281.6
#Mann= 6 ,-1 , 0
  3130.7     .07       0  3985.7     .07       0    4677     .15       0
  4988.7     .06       0  5012.2     .15       0  5997.7     .07       0
Bank Sta=4988.7,5012.2
XS Rating Curve= 0
Exp/Cntr=.3,.1

Type RM Length L Ch R = 1 ,346570.3,1192.45,1668.7,1202.04
BEGIN DESCRIPTION:
Cross Section XS279
END DESCRIPTION:
XS GIS Cut Line= 3
    2943073.8323    13974866.079    2941495.6987   13973666.3836
    2940559.1892    13973020.519
#Sta/Elev= 30
  2867.5   283.1  2987.5   279.5  3027.5   279.5  3367.5   272.7  3627.5   269.3
  3667.5   267.9  3727.5   267.4  3847.5     265  4027.5   264.9  4087.5   262.6
  4107.5   262.6  4227.5   259.6  4321.9  260.12  4365.4   260.4  4627.5   259.4
  4738.4  259.86  4850.2  258.53  4910.3  256.85  4960.5  257.27  4977.6  254.98
  4984.8  255.01    4992  252.06  4999.2     251    5008  252.03  5015.4  256.03
    5031  258.94  5098.1  261.11  5509.9     267  5729.9   272.4  5987.5   282.3
#Mann= 6 ,-1 , 0
  2867.5     .07       0  4321.9     .15       0  4365.4     .07       0
  4738.4     .15       0  4984.8     .06       0  5015.4     .07       0
Bank Sta=4984.8,5015.4
XS Rating Curve= 0
Exp/Cntr=.3,.1

Type RM Length L Ch R = 1 ,344901.6,1244.2,1468.9,1397.67
BEGIN DESCRIPTION:
Cross Section XS278
END DESCRIPTION:
XS GIS Cut Line= 3
    2943591.7048   13974467.7065    2942532.6267   13972849.4877
    2941078.8611   13972204.8315
#Sta/Elev= 30
  2907.6   280.6  3127.6   275.2  3247.6   273.7  3327.6   271.7  3367.6   271.7
  3467.6   268.8  3547.6   267.7  3727.6   263.8  3787.6   263.9  3847.6   262.1
  4007.6   259.3  4247.6   257.5  4922.4  257.52  4929.7   255.9  4978.1  255.09
  4992.7  253.07  4993.9  250.46  4998.3  248.99  5004.5  249.62  5006.1  250.47
    5010  254.79  5071.5  254.13  5120.7  256.29  5190.5  256.62  5361.6   261.8
  5421.6   261.1  5821.6   261.8  6061.6   266.8  6201.6   270.7  6431.9   278.2
#Mann= 3 ,-1 , 0
  2907.6     .07       0  4992.7     .06       0    5010     .07       0
Bank Sta=4992.7,5010
XS Rating Curve= 0
Exp/Cntr=.3,.1

Type RM Length L Ch R = 1 ,343432.7,990.34,1297.9,1124.55
BEGIN DESCRIPTION:
Cross Section XS277
END DESCRIPTION:
XS GIS Cut Line= 2
    2944573.5911   13973367.4807    2942901.3503   13971477.1215
#Sta/Elev= 30
  2984.6   270.5  3044.6   268.2  3224.6   262.7  3264.6   262.9  3304.6   261.6
  3324.6   260.2  3464.6   258.2  3724.6   257.3  3924.6   258.7  4144.6   258.4
  4264.6   256.2  4564.6   257.3  4704.6   256.6  4804.6   255.3  4946.4  255.66
  4966.9  253.68  4981.9   253.7  4988.2  252.06  4991.1  248.72  5006.5  247.53
  5008.8  248.72  5010.6  250.81  5027.8  251.62  5036.4  255.93  5072.7  255.74
  5141.7  257.71  5244.6   264.4  5284.6   266.5  5304.6   267.1  5508.5   267.2
#Mann= 4 , 1 , 0
  2984.6      .2       0  2984.6     .07       0  4988.2     .06       0
  5010.6     .07       0
Bank Sta=4988.2,5010.6
XS Rating Curve= 0
Exp/Cntr=.3,.1

Type RM Length L Ch R = 1 ,342134.8,369.71,480.8,541.95
BEGIN DESCRIPTION:
Cross Section XS276
END DESCRIPTION:
XS GIS Cut Line= 4
    2945029.2369   13973102.4791    2944605.9049   13972083.0059
    2943475.5819   13970182.3354    2943217.0719   13969787.3986
#Sta/Elev= 30
  3411.1     270  3411.2     270  3551.1   267.4  3731.1     267  3771.1   264.5
  4051.1   260.9  4111.1   258.4  4158.1  259.35  4231.1   258.1  4431.1   258.9
    4575   255.7    4871  253.77  4933.5  254.71  4983.9  252.54  4990.6  248.04
  4995.9  246.14  5006.3  246.57  5011.4  248.75  5015.5  248.78  5030.3  253.17
  5074.6  254.38    5195   255.7    5555   255.4    5775   260.9    6075   258.2
    6215   260.5    6495     260    6555   261.7  6986.3     263  7198.4   267.3
#Mann= 5 , 1 , 0
  3411.1      .2       0  3411.2     .07       0  4158.1     .07       0
  4983.9     .06       0  5011.4     .07       0
Bank Sta=4983.9,5011.4
XS Rating Curve= 0
Exp/Cntr=.3,.1

Type RM Length L Ch R = 1 ,341654.0,159.68,770.7,572.51
BEGIN DESCRIPTION:
Cross Section XS275
END DESCRIPTION:
XS GIS Cut Line= 6
    2945107.3386   13973069.7268    2944905.1784   13972005.3933
    2944791.7094   13971477.1215    2944594.0405    13971207.257
    2944238.9574   13969989.8293    2944021.5828   13969244.8215
#Sta/Elev= 30
    3176   270.6    4096   257.5  4299.4     257  4359.4     258  4439.4   256.1
  4629.6  255.33  4739.4   255.8  4924.5  253.29  4976.4  253.75  4992.3  249.74
  4993.8  247.51    4997  245.77  5000.1   245.6  5003.9  246.08  5008.1  249.84
  5018.4  251.97  5037.6  250.55    5131  254.65  5187.3  255.56  5274.2   253.6
  5294.2   252.2  5334.2   253.5  5554.2   255.2  5794.2   255.6  5874.2   257.2
  6294.2   257.7  6482.4     261  6802.4   264.3  7002.4   264.1  7178.4   267.1
#Mann= 6 , 1 , 0
    3176      .2       0    3176     .07       0  4629.6     .07       0
  4992.3     .06       0  5008.1     .07       0  7178.4      .2       0
Bank Sta=4992.3,5008.1
XS Rating Curve= 0
Exp/Cntr=.3,.1

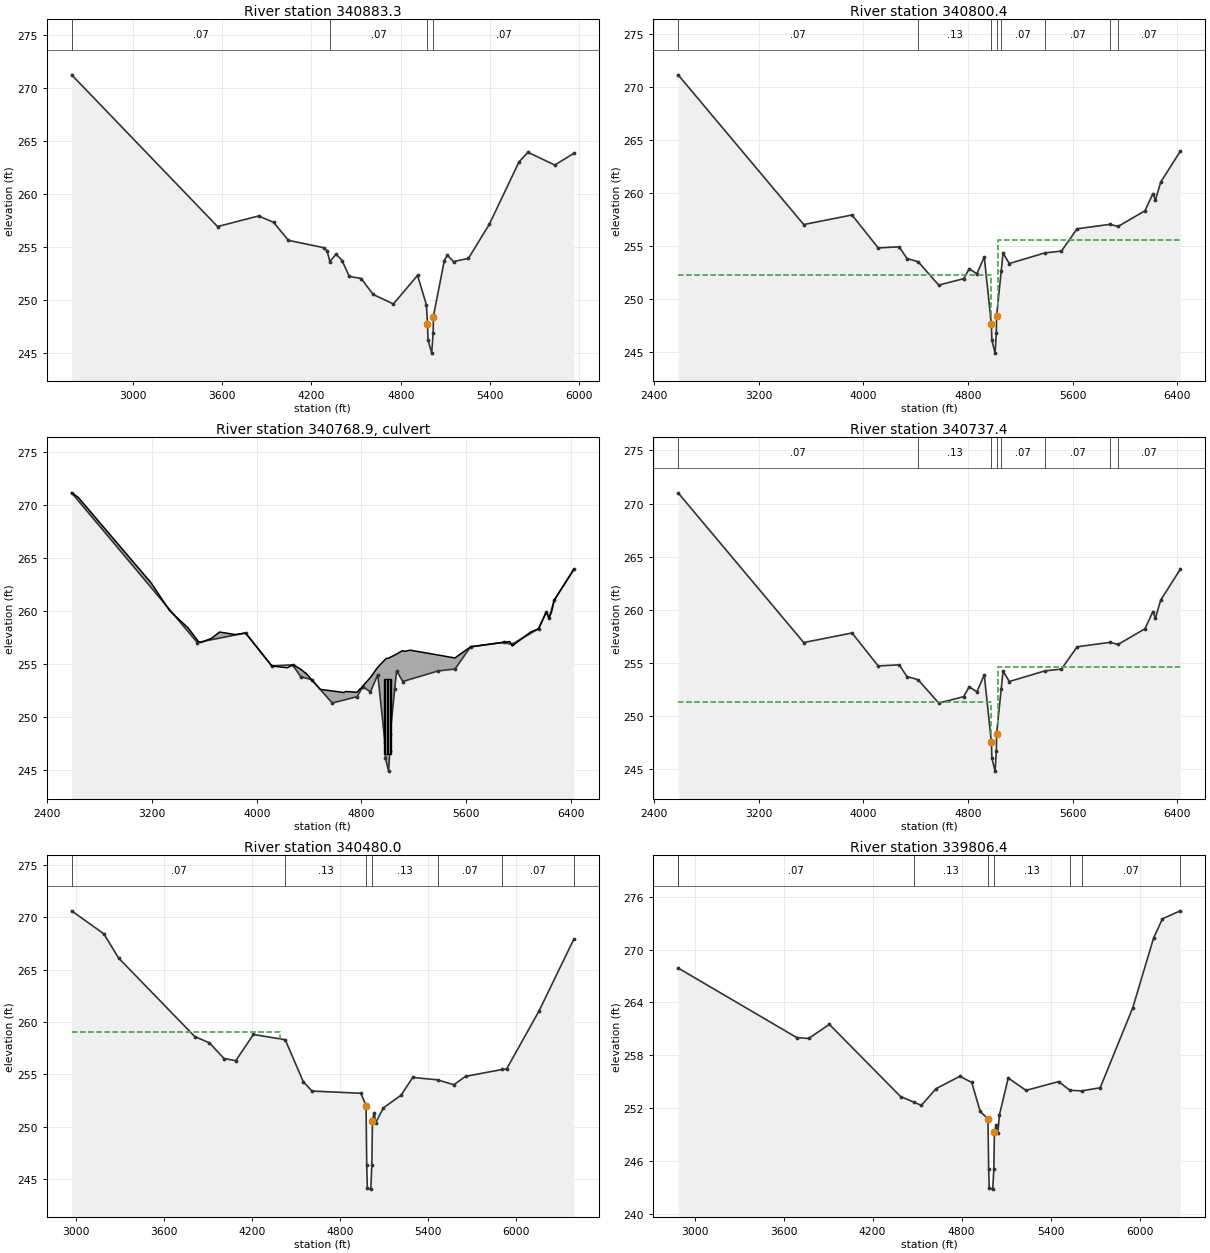
Type RM Length L Ch R = 1 ,340883.3,50.48,82.9,182.78
BEGIN DESCRIPTION:
Cross Section XS274.5
END DESCRIPTION:
XS GIS Cut Line= 6
    2945152.6879   13973049.5715    2944988.9264   13972046.8473
    2944971.0567   13971238.2928    2944912.2356   13970743.9891
    2944824.5199    13970562.366    2944536.9447    13969764.516
#Sta/Elev= 30
  2589.8   271.2  3569.8   256.9  3845.8   257.9  3945.8   257.3  4045.8   255.6
  4285.8   254.9  4305.8   254.6    4324   253.6  4365.8   254.3  4405.8   253.7
  4454.6   252.2  4534.6     252  4614.6   250.5  4750.9   249.6  4912.9   252.3
  4972.9   249.5  4979.7  247.67  4983.8  246.18    5008  244.97  5017.8  246.91
  5019.2  248.42  5092.9   253.7  5112.9   254.2  5154.6   253.6  5254.6   253.9
  5394.6   257.1  5594.6     263  5654.6   263.9  5834.6   262.7  5962.7   263.8
#Mann= 4 ,-1 , 0
  2589.8     .07       0    4324     .07       0  4979.7     .06       0
  5019.2     .07       0
Bank Sta=4979.7,5019.2
XS Rating Curve= 0
Exp/Cntr=.5,.3

Type RM Length L Ch R = 1 ,340800.4,63,63,63
BEGIN DESCRIPTION:
Upstream Section of Mayer/Field Store
END DESCRIPTION:
XS GIS Cut Line= 6
    2945188.3988   13973020.3556    2945037.2343   13972042.8255
     2944993.957   13971031.4325    2944922.7525   13970473.1479
    2944945.5116   13969689.8074    2945028.6805   13969207.1445
#Sta/Elev= 30
  2585.6  271.11  3545.6  257.01  3914.7  257.91  4114.7  254.81  4274.7  254.91
  4334.7  253.81  4419.9  253.51  4577.2  251.31  4767.1  251.91  4810.5  252.84
  4868.9  252.37  4925.3  253.97  4979.7   247.6  4983.8  246.11  5007.9   244.9
  5017.8  246.84  5019.2  248.35  5055.1  252.67  5068.9  254.33  5116.6  253.34
  5388.4  254.34    5515  254.51    5635  256.61  5886.4  257.03  5947.9  256.83
  6153.7  258.31  6213.7  259.91  6233.7  259.31  6273.7  261.01  6423.5  263.91
#Mann= 8 ,-1 , 0
  2585.6     .07       0  4419.9     .13       0  4979.7     .06       0
  5019.2     .13       0  5055.1     .07       0  5388.4     .07       0
  5886.4     .07       0  5947.9     .07       0
#XS Ineff= 2 , 0
       0    4973   252.3    5027       0   255.6
Permanent Ineff=
       F       F
Bank Sta=4979.7,5019.2
XS Rating Curve= 0
Exp/Cntr=.5,.3

Type RM Length L Ch R = 2 ,340768.9,,,
BEGIN DESCRIPTION:
MAYER/FIELD STORE
Structure ID: J100-00-00-19
END DESCRIPTION:
Node Name=Mayer/Field Stor
Bridge Culvert--1,0,-1,-1, 0
Deck Dist Width WeirC Skew NumUp NumDn MinLoCord MaxHiCord MaxSubmerge Is_Ogee
10,43,2.6,0, 79, 79, , , .95, 0, 1,1,,
  2585.6  2634.9  3194.9  3334.9  3365.6  3405.6  3425.6  3474.9  3545.6  3554.9
  3574.7  3574.9  3576.1  3636.1  3654.7  3716.1  3836.1  3914.7  3936.1  4114.7
  4116.1  4234.7  4274.7  4294.7  4334.7  4336.1  4376.1  4377.2  4419.9  4476.1
  4487.2  4577.2  4667.2  4678.8  4767.1  4787.1  4798.8  4810.5  4810.7  4868.7
  4868.9  4925.3  4925.4  4979.7  4982.1  4983.8  4989.4  5003.3  5007.9    5008
  5015.5  5017.8  5019.2  5055.1  5064.6  5068.9    5115  5116.6  5130.8  5171.3
 5173.01  5388.4    5475    5515    5635  5681.9  5886.4  5907.3  5933.7  5947.9
  5953.7  6093.7  6153.7  6213.7  6233.7  6253.7  6273.7  6410.8  6423.5
   271.1   270.7   262.6     260  259.65  259.19  258.96   258.4  257.25   257.1
     257     257  257.02  257.32  257.41     258  257.76  257.91  257.58  254.82
   254.8  254.64  254.91  254.81   254.5   254.5   254.1  254.11  253.51  252.73
   252.6  252.45   252.3   252.4  252.33  252.61  252.73   252.9  252.91  253.72
  253.72  254.69  254.69  255.39  255.42  255.44  255.51  255.53  255.54  255.54
  255.59   255.6  255.61  255.84   255.9  255.93  256.25  256.24  256.18  256.29
  256.29  255.83  255.64  255.56  256.61  256.69  257.03  257.07   257.1  256.82
   256.7     258   258.3   259.9   259.3   259.9     261  263.65   263.9
                                                                                
                                                                                
                                                                                
                                                                                
                                                                                
                                                                                
                                                                                
                                                                        
  2585.6  2634.9  3194.9  3334.9  3365.6  3405.6  3425.6  3474.9  3545.6  3554.9
  3574.7  3574.9  3576.1  3636.1  3654.7  3716.1  3836.1  3914.7  3936.1  4114.7
  4116.1  4234.7  4274.7  4294.7  4334.7  4336.1  4376.1  4377.2  4419.9  4476.1
  4487.2  4577.2  4667.2  4678.8  4767.1  4787.1  4798.8  4810.5  4810.7  4868.7
  4868.9  4925.3  4925.4  4979.7  4982.1  4983.8  4989.4  5003.3  5007.9    5008
  5015.5  5017.8  5019.2  5055.1  5064.6  5068.9    5115  5116.6  5130.8  5171.3
 5173.01  5388.4    5475    5515    5635  5681.9  5886.4  5907.3  5933.7  5947.9
  5953.7  6093.7  6153.7  6213.7  6233.7  6253.7  6273.7  6410.8  6423.5
   271.1   270.7   262.6     260  259.65  259.19  258.96   258.4  257.25   257.1
     257     257  257.02  257.32  257.41     258  257.76  257.91  257.58  254.82
   254.8  254.64  254.91  254.81   254.5   254.5   254.1  254.11  253.51  252.73
   252.6  252.45   252.3   252.4  252.33  252.61  252.73   252.9  252.91  253.72
  253.72  254.69  254.69  255.39  255.42  255.44  255.51  255.53  255.54  255.54
  255.59   255.6  255.61  255.84   255.9  255.93  256.25  256.24  256.18  256.29
  256.29  255.83  255.64  255.56  256.61  256.69  257.03  257.07   257.1  256.82
   256.7     258   258.3   259.9   259.3   259.9     261  263.65   263.9
                                                                                
                                                                                
                                                                                
                                                                                
                                                                                
                                                                                
                                                                                
                                                                        
BR Coef= 1 , 1 , 0 ,1.25, 0 ,,,.8,-1,2,0,
WSPro=,,,, 1 ,,,, 0 ,,,, 0 ,,,,-1 ,-1 ,-1 , 0 , 0 , 0 , 0 , 0
Culvert=2,7,10,43,.015,.4,1,8,1,246.55,4978,246.51,4978,Culvert #1  , 0 ,10
Culvert Bottom n=.015
Culvert=2,7,10,43,.015,.4,1,8,1,246.55,4989,246.51,4989,Culvert #2  , 0 ,10
Culvert Bottom n=.015
Culvert=2,7,10,43,.015,.4,1,8,1,246.55,5000,246.51,5000,Culvert #3  , 0 ,10
Culvert Bottom n=.015
Culvert=2,7,10,43,.015,.4,1,8,1,246.55,5011,246.51,5011,Culvert #4  , 0 ,10
Culvert Bottom n=.015
Culvert=2,7,10,43,.015,.4,1,8,1,246.55,5022,246.51,5022,Culvert #5  , 0 ,10
Culvert Bottom n=.015
BC Design=,, 0 ,, 0 ,,,,,,
BC HTab HWMax=271.11

Type RM Length L Ch R = 1 ,340737.4,257.4,257.4,257.4
BEGIN DESCRIPTION:
Downstream Section of Mayer/Field Store
END DESCRIPTION:
XS GIS Cut Line= 6
    2945231.3933   13973019.4273    2945086.0875   13972038.9418
    2945065.6172   13971128.0721    2944989.4713   13970538.6398
    2945006.1496   13969802.4948    2945102.4606   13969205.6625
#Sta/Elev= 30
  2585.6  271.01  3545.6  256.91  3914.7  257.81  4114.7  254.71  4274.7  254.81
  4334.7  253.71  4419.9  253.41  4577.2  251.21  4767.1  251.81  4810.5  252.74
  4868.9  252.27  4925.3  253.87  4979.7   247.5  4983.8  246.01  5007.9   244.8
  5017.8  246.74  5019.2  248.25  5055.1  252.57  5068.9  254.23  5116.6  253.24
  5388.4  254.24    5515  254.41    5635  256.51  5886.4  256.93  5947.9  256.73
  6153.7  258.21  6213.7  259.81  6233.7  259.21  6273.7  260.91  6423.5  263.81
#Mann= 8 ,-1 , 0
  2585.6     .07       0  4419.9     .13       0  4979.7     .06       0
  5019.2     .13       0  5055.1     .07       0  5388.4     .07       0
  5886.4     .07       0  5947.9     .07       0
#XS Ineff= 2 , 0
       0    4973   251.3    5027       0   254.6
Permanent Ineff=
       F       F
Bank Sta=4979.7,5019.2
XS Rating Curve= 0
Exp/Cntr=.5,.3

Type RM Length L Ch R = 1 ,340480.0,678.88,673.6,555.66
BEGIN DESCRIPTION:
Cross Section XS274
Ineffective at Sta 4389 based on floodplain confined upstream
END DESCRIPTION:
XS GIS Cut Line= 3
    2945723.0173   13972566.6284    2945252.1815   13970863.1587
      2945155.24   13969207.0749
#Sta/Elev= 30
  2969.3   270.6  3189.3   268.4  3289.3   266.1  3809.3   258.6  3909.3     258
  4009.3   256.5  4089.3   256.3  4209.3   258.8  4426.5   258.3  4549.3   254.3
  4609.3   253.4  4942.6  253.19    4978  252.01  4982.5  246.38  4986.6  244.14
  5010.1  244.04  5017.6  246.36  5021.5  250.57  5033.5  251.34  5043.8  250.39
  5096.6   251.8  5216.6     253  5296.6   254.7  5465.4  254.47  5576.6     254
  5656.6   254.8  5907.3  255.46  5936.6   255.5  6156.6     261  6395.6   267.9
#Mann= 7 ,-1 , 0
  2969.3     .07       0  4426.5     .13       0    4978     .06       0
  5021.5     .13       0  5465.4     .07       0  5907.3     .07       0
  6395.6      .2       0
#XS Ineff= 2 , 0
       0    4389     259               0
Permanent Ineff=
       F       F
Bank Sta=4978,5021.5
XS Rating Curve= 0
Exp/Cntr=.3,.1

Type RM Length L Ch R = 1 ,339806.4,781.95,1023.1,947.63
BEGIN DESCRIPTION:
Cross Section XS273
END DESCRIPTION:
XS GIS Cut Line= 3
    2946315.0486   13972382.4409    2945817.6736    13970233.039
     2945454.143   13969110.1334
#Sta/Elev= 30
  2888.5   267.9  3688.5     260  3768.5   259.9  3908.5   261.5  4388.5   253.3
  4476.7  252.67  4528.5   252.3  4628.5   254.2  4788.5   255.6  4868.5   254.9
  4925.3  251.62    4978  250.75  4982.5  245.12  4986.6  242.88  5010.1  242.78
  5017.6   245.1  5021.5  249.31  5033.5  250.08  5043.8  249.13  5055.5  251.24
  5114.7   255.4  5234.7     254  5454.7     255    5530  254.01  5610.9  253.94
  5734.7   254.3  5954.7   263.4  6094.7   271.3  6154.7   273.5    6275   274.4
#Mann= 8 , 1 , 0
  2888.5      .2       0  2888.5     .07       0  4476.7     .13       0
    4978     .08       0  5021.5     .13       0    5530     .07       0
  5610.9     .07       0    6275      .2       0
Bank Sta=4978,5021.5
XS Rating Curve= 0
Exp/Cntr=.3,.1

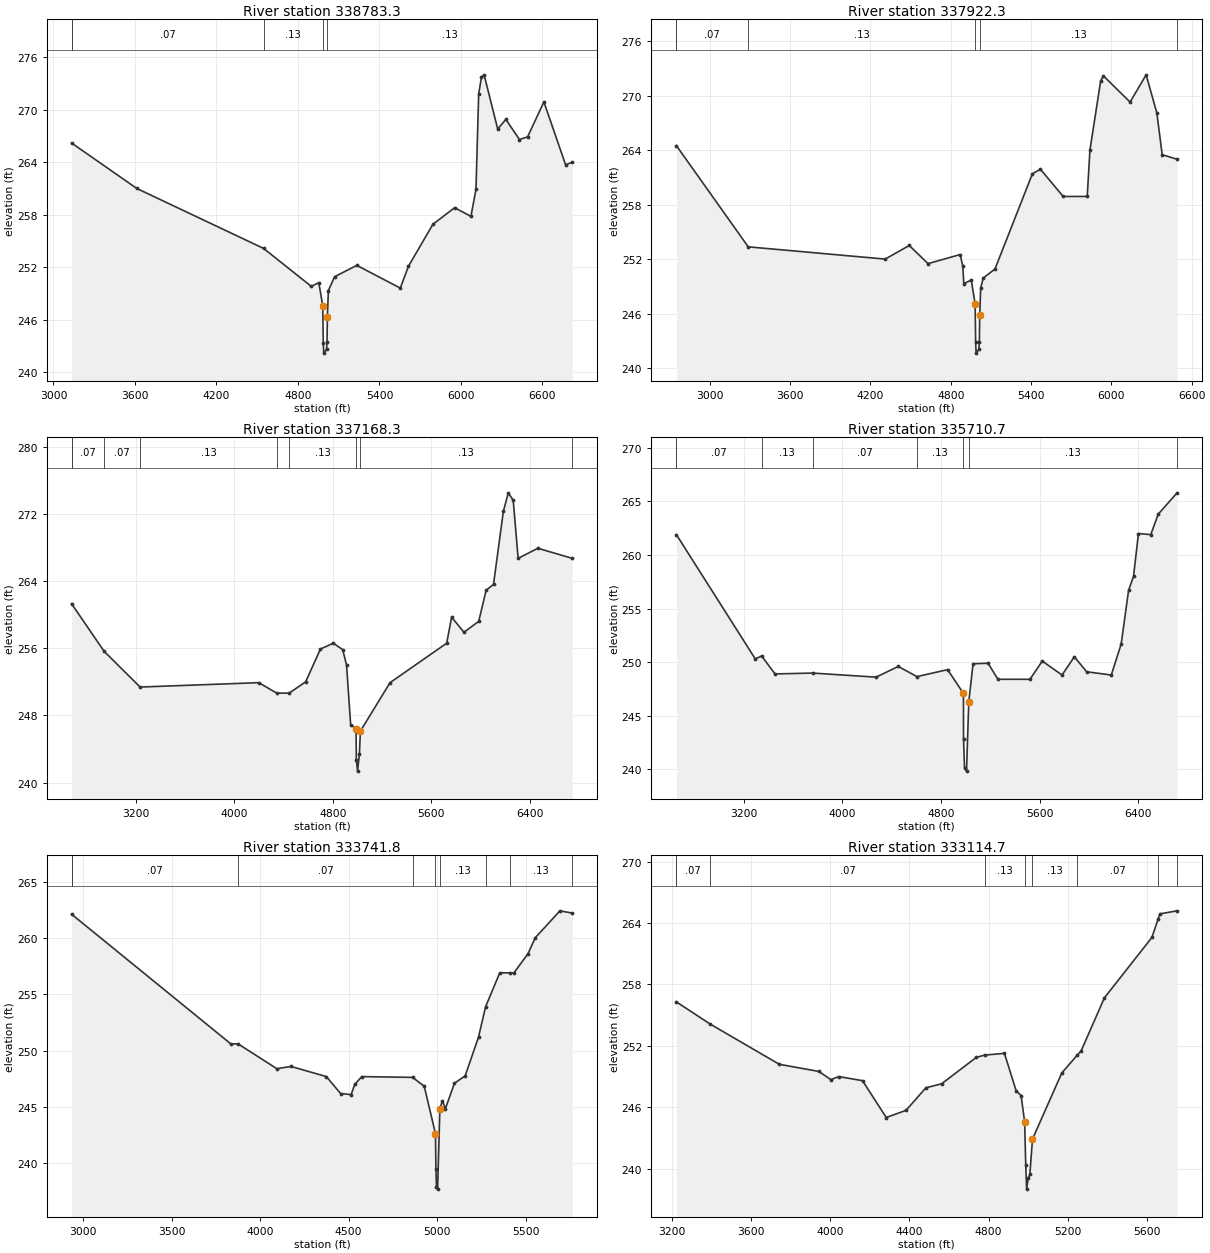
Type RM Length L Ch R = 1 ,338783.3,1140.91,861,290.13
BEGIN DESCRIPTION:
Cross Section XS272
END DESCRIPTION:
XS GIS Cut Line= 4
    2946972.8611   13972290.3471    2946674.3754    13970191.452
    2946604.9309   13969337.2853    2946257.7087   13968719.2298
#Sta/Elev= 30
  3133.4   266.2  3613.4     261  4546.8  254.14  4897.8   249.8  4953.3  250.22
  4982.5  247.57  4986.2  243.36  4989.8  242.16  5010.1  242.58  5013.8  243.38
  5016.6  246.33  5023.9  249.32  5069.6   250.9  5233.4   252.2  5553.4   249.6
  5613.4   252.1  5793.4   256.9  5953.4   258.8  6073.4   257.8  6110.4   260.9
  6130.4   271.8  6150.4   273.7  6170.4     274  6270.4   267.8  6330.4   268.9
  6430.4   266.6  6490.4   266.9  6610.4   270.9  6770.4   263.7  6819.3     264
#Mann= 5 , 1 , 0
  3133.4      .2       0  3133.4     .07       0  4546.8     .13       0
  4982.5     .08       0  5016.6     .13       0
Bank Sta=4982.5,5016.6
XS Rating Curve= 0
Exp/Cntr=.3,.1

Type RM Length L Ch R = 1 ,337922.3,725.85,754,674.69
BEGIN DESCRIPTION:
Cross Section XS271
END DESCRIPTION:
XS GIS Cut Line= 3
    2948782.4676   13971412.4939    2946697.9702   13969411.3764
     2946278.542   13968670.6187
#Sta/Elev= 30
  2750.4   264.5  3287.1  253.35  4310.4     252  4490.4   253.5  4630.4   251.5
  4870.4   252.5  4890.4   251.2  4897.8  249.28  4953.3   249.7  4982.5  247.05
  4986.2  242.84  4989.8  241.64  5010.1  242.06  5013.8  242.86  5016.6  245.81
  5023.9   248.8  5043.3  249.92  5130.4   250.9  5410.4   261.4  5470.4   261.9
    5640   258.9    5820   258.9    5840     264    5920   271.6    5940   272.2
    6140   269.3    6260   272.3    6340   268.1    6380   263.5  6491.2     263
#Mann= 6 , 1 , 0
  2750.4      .2       0  2750.4     .07       0  3287.1     .13       0
  4982.5     .08       0  5016.6     .13       0  6491.2      .2       0
Bank Sta=4982.5,5016.6
XS Rating Curve= 0
Exp/Cntr=.3,.1

Type RM Length L Ch R = 1 ,337168.3,820.33,1457.6,1382.01
BEGIN DESCRIPTION:
Cross Section XS270
END DESCRIPTION:
XS GIS Cut Line= 3
    2949323.7243   13970984.3356    2947829.2096    13969473.664
    2946257.7087   13968337.2853
#Sta/Elev= 30
  2679.4   261.3  2943.1  255.64  3235.8  251.38  4199.4   251.9  4345.4  250.65
  4446.4  250.66  4579.4     252  4699.4   255.9  4804.4   256.6  4880.3  255.83
  4911.6  253.99  4944.8  246.91  4988.5  246.39  4990.9  242.73  5000.7  241.37
  5015.8  243.38  5023.8  246.13  5264.4   251.9  5724.4   256.6  5764.4   259.7
  5864.4   257.9  5984.4   259.2  6044.4   262.9  6104.4   263.6  6184.4   272.3
  6224.4   274.5  6264.4   273.6  6304.4   266.7  6464.4   267.9  6743.7   266.7
#Mann= 9 , 1 , 0
  2679.4      .2       0  2679.4     .07       0  2943.1     .07       0
  3235.8     .13       0  4345.4     .07       0  4446.4     .13       0
  4988.5     .08       0  5023.8     .13       0  6743.7      .2       0
Bank Sta=4988.5,5023.8
XS Rating Curve= 0
Exp/Cntr=.3,.1

Type RM Length L Ch R = 1 ,335710.7,756.19,1968.9,1847.32
BEGIN DESCRIPTION:
Cross Section XS269
END DESCRIPTION:
XS GIS Cut Line= 3
    2949735.7256   13970798.5311     2948523.957   13968625.4259
    2947530.3066   13967405.5788
#Sta/Elev= 30
  2654.5   261.9  3294.5   250.3  3345.6  250.58  3454.5   248.9  3759.2  248.98
  4274.5   248.6  4454.5   249.6  4605.8  248.65  4854.5   249.3  4983.2  247.08
  4983.5  242.86  4991.8  240.12  5007.9  239.83  5026.4  246.31  5061.1  249.85
  5182.6   249.9  5262.6   248.4  5522.6   248.4  5622.6   250.1  5782.6   248.8
  5882.6   250.5  5982.6   249.1  6182.6   248.8  6262.6   251.7  6322.6   256.7
  6362.6     258  6402.6     262  6502.6   261.9  6562.6   263.8    6716   265.8
#Mann= 8 , 1 , 0
  2654.5      .2       0  2654.5     .07       0  3345.6     .13       0
  3759.2     .07       0  4605.8     .13       0  4983.2     .08       0
  5026.4     .13       0    6716      .2       0
Bank Sta=4983.2,5026.4
XS Rating Curve= 0
Exp/Cntr=.3,.1

Type RM Length L Ch R = 1 ,333741.8,651.64,627.1,423.01
BEGIN DESCRIPTION:
Cross Section XS268
END DESCRIPTION:
XS GIS Cut Line= 3
    2950113.6115    13970770.445    2949598.3919    13968714.289
    2949452.9796   13968019.5416
#Sta/Elev= 30
  2934.7   262.1  3834.7   250.6  3875.8   250.6  4094.7   248.4  4174.7   248.6
  4374.7   247.7  4454.7   246.2  4514.7   246.1  4534.7     247  4574.7   247.7
    4862  247.63  4927.7  246.84  4991.1  242.64  4993.8  239.47  4996.8  237.87
  5003.2  237.72    5016  244.79  5029.9  245.56  5047.2  244.85  5098.4  247.11
  5158.8  247.76  5234.4   251.2  5274.1  253.88  5354.4   256.9  5410.4   256.9
  5434.4   256.9  5514.4   258.6  5554.4     260  5694.4   262.4  5764.2   262.2
#Mann= 9 , 1 , 0
  2934.7      .2       0  2934.7     .07       0  3875.8     .07       0
    4862     .13       0  4991.1     .08       0    5016     .13       0
  5274.1     .07       0  5410.4     .13       0  5764.2      .2       0
Bank Sta=4991.1,5016
XS Rating Curve= 0
Exp/Cntr=.3,.1

Type RM Length L Ch R = 1 ,333114.7,290.97,609.6,687.04
BEGIN DESCRIPTION:
Cross Section XS267
END DESCRIPTION:
XS GIS Cut Line= 3
    2950617.0837   13970049.9589    2950180.0408   13968488.0921
    2949523.3337   13967862.4589
#Sta/Elev= 30
  3223.1   256.3  3393.8  254.13  3743.1   250.2  3943.1   249.5  4003.1   248.7
  4043.1     249  4163.1   248.6  4283.1     245  4383.1   245.7  4483.1   247.9
  4563.1   248.3  4738.1  250.88  4780.4   251.1    4880  251.27  4939.5  247.59
  4964.1  247.15  4982.1  244.56  4987.6  240.37  4992.1     238  4999.7  239.06
  5008.4  239.44  5021.7  242.89  5169.6  249.35  5246.5  251.07  5267.9  251.53
    5385   256.7    5625   262.6  5656.1  264.39    5665   264.9    5752   265.2
#Mann= 9 , 1 , 0
  3223.1      .2       0  3223.1     .07       0  3393.8     .07       0
  4780.4     .13       0  4982.1     .08       0  5021.7     .13       0
  5246.5     .07       0  5656.1     .13       0    5752      .2       0
Bank Sta=4982.1,5021.7
XS Rating Curve= 0
Exp/Cntr=.3,.1

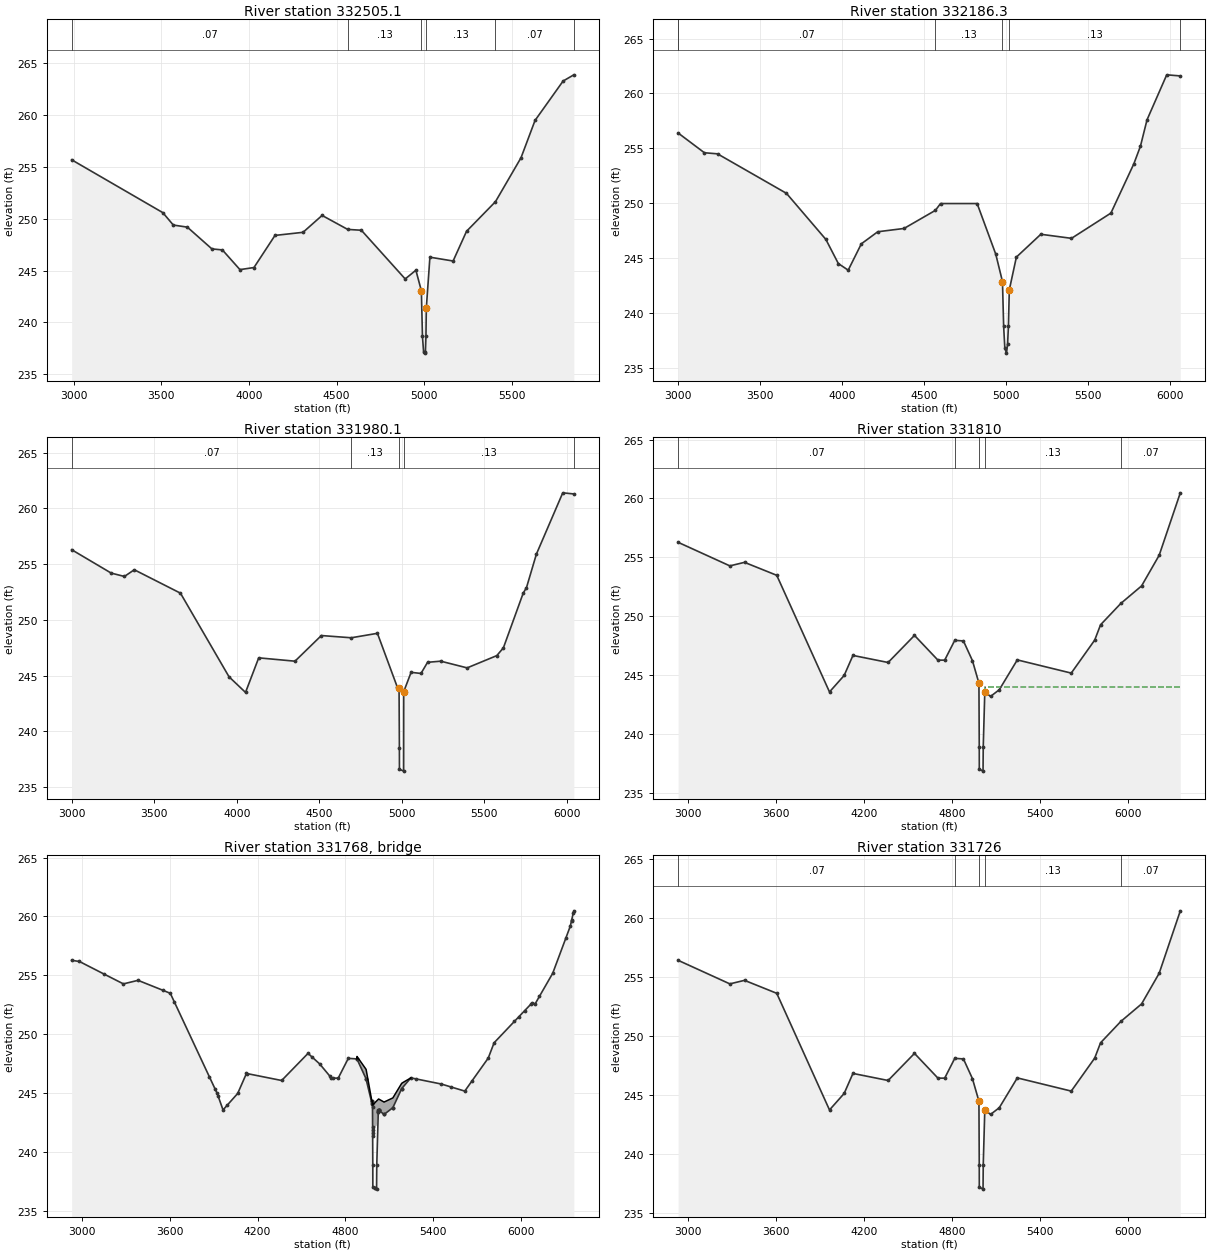
Type RM Length L Ch R = 1 ,332505.1,176.58,318.8,452.35
BEGIN DESCRIPTION:
Cross Section XS266
END DESCRIPTION:
XS GIS Cut Line= 4
    2950738.6115   13969902.3895     2950535.493   13968423.4645
    2950228.5116   13967502.5203    2949921.5302   13967244.0096
#Sta/Elev= 30
  2988.7   255.7  3508.7   250.6  3568.7   249.4  3648.7   249.2  3788.7   247.1
  3848.7     247  3948.7   245.1  4028.7   245.3  4148.7   248.4  4308.7   248.7
 4417.45  250.33  4563.5  248.98  4641.5   248.9  4891.5   244.2  4952.5  245.04
  4983.8  243.06    4990  238.65  4996.5  237.15  5001.9  237.04  5006.9  237.18
  5009.9  238.66    5012  241.38  5032.5   246.3  5164.8  245.93  5241.5   248.8
  5406.6  251.66  5552.3   255.9  5632.3   259.5  5792.3   263.3  5853.6   263.9
#Mann= 6 ,-1 , 0
  2988.7     .07       0  4563.5     .13       0  4983.8     .08       0
    5012     .13       0  5406.6     .07       0  5853.6      .2       0
Bank Sta=4983.8,5012
XS Rating Curve= 0
Exp/Cntr=.3,.1

Type RM Length L Ch R = 1 ,332186.3,90.84,206.2,137.45
BEGIN DESCRIPTION:
Cross Section XS265
END DESCRIPTION:
XS GIS Cut Line= 3
     2950847.584   13969895.3074    2950777.3418   13968941.9829
    2950583.9637   13966848.1652
#Sta/Elev= 30
  3002.8   256.4  3162.8   254.6  3242.8   254.5  3662.8   250.9  3902.8   246.7
  3978.7   244.5  4038.7   243.9  4118.7   246.3  4218.7   247.4  4378.7   247.7
  4569.8  249.35 4601.03  249.97    4824  249.97  4937.6  245.35  4978.3  242.86
  4985.5  238.77  4992.7  236.78  5002.8  236.34  5009.6   237.2  5014.6  238.83
  5019.9   242.1    5063  245.09  5211.9  247.17  5398.7   246.8  5638.7   249.1
  5778.7   253.6  5818.7   255.2  5858.7   257.6  5978.7   261.7  6061.4   261.6
#Mann= 6 , 1 , 0
  3002.8      .2       0  3002.8     .07       0  4569.8     .13       0
  4978.3     .08       0  5019.9     .13       0  6061.4      .2       0
Bank Sta=4978.3,5019.9
XS Rating Curve= 0
Exp/Cntr=.3,.1

Type RM Length L Ch R = 1 ,331980.1,112.93,170.1,171.68
BEGIN DESCRIPTION:
Cross Section XS264
END DESCRIPTION:
XS GIS Cut Line= 4
    2950893.0317   13969880.1582    2950856.8905   13968926.2394
    2950874.7882   13967882.2078    2950664.7483   13966856.2437
#Sta/Elev= 30
  2998.5   256.3  3238.5   254.2  3318.5   253.9  3378.5   254.5  3658.5   252.4
  3953.1   244.9  4053.1   243.5  4133.1   246.6  4353.1   246.3  4513.1   248.6
  4694.5   248.4  4853.1   248.8  4973.1     244  4984.4   243.9  4986.4  238.51
  4986.7  236.61  5012.2  236.44  5012.6  243.56  5057.3   245.3  5117.3   245.2
  5157.3   246.2  5237.3   246.3  5397.3   245.7  5577.3   246.8  5617.3   247.5
  5737.3   252.4  5757.3   252.9  5817.3   255.9  5977.3   261.4  6044.5   261.3
#Mann= 5 ,-1 , 0
  2998.5     .07       0  4694.5     .13       0  4984.4     .08       0
  5012.6     .13       0  6044.5      .2       0
Bank Sta=4984.4,5012.6
XS Rating Curve= 0
Exp/Cntr=.5,.3

Type RM Length L Ch R = 1 ,331810  ,84,84,84
BEGIN DESCRIPTION:
Upstream Section of Access Metal Bridge DS of Kickapoo
END DESCRIPTION:
XS GIS Cut Line= 5
     2950931.804   13969873.8429    2950882.5168   13968559.2416
    2951012.1041   13968086.6292    2951057.8408   13966623.0551
    2951043.5734   13966466.1132
#Sta/Elev= 30
  2931.3  256.28  3284.4  254.28  3384.4  254.58  3604.4  253.48  3964.4  243.58
  4064.4  244.98  4124.4  246.68  4364.4  246.08  4544.4  248.38  4704.4  246.28
  4750.5  246.28  4819.3  247.96  4878.4  247.91  4939.8  246.24  4984.2  244.32
  4986.4  238.93  4986.7  237.03  5012.2  236.86  5013.5   238.9  5024.2  243.59
  5063.5   243.2  5123.1  243.77    5246   246.3  5614.2  245.18  5774.2  247.98
  5814.2  249.28  5952.3  251.09  6094.2  252.58  6214.2  255.18  6358.4  260.48
#Mann= 5 ,-1 , 0
  2931.3     .07       0  4819.3     .13       0  4984.2     .08       0
  5024.2     .13       0  5952.3     .07       0
#XS Ineff= 2 , 0
       0  4984.3     244  5024.2       0     244
Permanent Ineff=
       F       F
Bank Sta=4984.2,5024.2
XS Rating Curve= 0
Exp/Cntr=.5,.3

Type RM Length L Ch R = 3 ,331768  ,,,
BEGIN DESCRIPTION:
ACCESS METAL BRIDGE US KICKAPOO
Structure ID: J100-00-00-18
No piers
END DESCRIPTION:
Node Name=Brdg DS Kickapoo
Bridge Culvert--1,0,-1,-1, 0
Deck Dist Width WeirC Skew NumUp NumDn MinLoCord MaxHiCord MaxSubmerge Is_Ogee
10,11.1,2.6,0, 34, 34, , , .95, 0, 1,1,,
  4878.4  4878.6  4939.8  4940.6  4979.8 4984.09  4984.2  4984.3 4984.41  4985.1
 4985.21  4985.3  4985.4  4986.4  4986.7  4998.4  5002.1  5012.2  5013.5 5023.69
  5023.8 5023.91  5024.2  5026.1 5026.19  5026.3  5026.4    5063  5063.5  5123.1
  5123.7  5184.1  5184.2    5246
  247.91  248.12  247.04  247.03  244.35  244.35  244.35   244.1  244.06  243.99
  243.99  243.99  243.99  244.01  244.01  244.16  244.21  244.34  244.35  244.48
  244.48  244.48  244.48  244.51  244.51  244.51  244.51  244.25  244.25   244.6
  244.61  245.85  245.85   246.3
                                          244.35  244.35  244.09  243.83  242.13
  241.87  241.89  241.89  241.91  241.91  242.06  242.11  242.24  242.25  242.39
  243.43  243.48
                                
  4878.4  4878.6  4939.8  4940.6  4979.8 4984.09  4984.2  4984.3 4984.41  4985.1
 4985.21  4985.3  4985.4  4986.4  4986.7  4998.4  5002.1  5012.2  5013.5 5023.69
  5023.8 5023.91  5024.2  5026.1 5026.19  5026.3  5026.4    5063  5063.5  5123.1
  5123.7  5184.1  5184.2    5246
  247.91  248.12  247.04  247.03  244.35  244.35  244.35   244.1  244.06  243.99
  243.99  243.99  243.99  244.01  244.01  244.16  244.21  244.34  244.35  244.48
  244.48  244.48  244.48  244.51  244.51  244.51  244.51  244.25  244.25   244.6
  244.61  245.85  245.85   246.3
                                          244.35  244.34  244.09  243.83  242.13
  241.87  241.89  241.89  241.91  241.91  242.06  242.11  242.24  242.25  242.39
  243.43  243.48
                                
BR Coef= 1 , 1 , 0 ,1.05, 0 ,,,.8,0,2,0,
WSPro=,,,, 1 ,,,, 0 ,,,, 0 ,,,,-1 ,-1 ,-1 , 0 , 0 , 0 , 0 , 0
BR U #Sta/Elev= 81
  2931.3  256.28  2984.4  256.18  3151.3  255.12  3284.4  254.28  3384.4  254.58
  3551.3  253.75  3604.4  253.48  3631.3  252.77  3871.3  246.39  3911.3  245.33
  3924.4  244.98  3931.3  244.74  3964.4  243.58  3991.3  243.96  4064.4  244.98
  4124.4  246.68  4131.3  246.66  4364.4  246.08  4544.4  248.38  4571.3  248.08
  4624.4  247.48  4691.3  246.48  4704.4  246.28  4713.1  246.28  4750.5  246.28
  4819.3  247.96  4878.4  247.91  4878.6   247.9  4939.8  246.24  4940.6   246.2
  4979.8  244.17 4984.09  244.32  4984.2  244.32  4984.3  244.07 4984.41  243.81
  4985.1  242.11 4985.21  241.85  4985.3  241.62  4985.4  241.38  4986.4  238.93
  4986.7  237.03  4998.4  236.96  5002.1  236.93  5012.2  236.86  5013.5   238.9
 5023.69  243.37  5023.8  243.41 5023.91  243.46  5024.2  243.59  5026.1  243.57
 5026.19  243.57  5026.3  243.57  5026.4  243.57    5063   243.2  5063.5   243.2
  5123.1  243.77  5123.7  243.78  5184.1   245.4  5184.2   245.4    5246   246.3
  5283.1  246.21  5454.2  245.78  5523.1  245.52  5614.2  245.18  5663.1  246.04
  5774.2  247.98  5814.2  249.28  5952.3  251.09  5983.1  251.49  6023.1  252.01
  6063.1  252.53  6074.2  252.68  6094.2  252.58  6123.1  253.21  6214.2  255.18
  6303.1  258.14  6334.2  259.18  6342.8  259.65  6342.9  259.66  6354.2  260.28
  6358.4  260.48
BR U #Mann= 5
  2931.3     .07  4819.3     .13  4984.2     .07  5024.2     .13  5952.3     .07
BR D #Sta/Elev= 81
  2931.3  256.41  2984.4  256.31  3151.3  255.25  3284.4  254.41  3384.4  254.71
  3551.3  253.88  3604.4  253.61  3631.3   252.9  3871.3  246.52  3911.3  245.46
  3924.4  245.11  3931.3  244.87  3964.4  243.71  3991.3  244.09  4064.4  245.11
  4124.4  246.81  4131.3  246.79  4364.4  246.21  4544.4  248.51  4571.3  248.21
  4624.4  247.61  4691.3  246.61  4704.4  246.41  4713.1  246.41  4750.5  246.41
  4819.3  248.09  4878.4  248.04  4878.6  248.03  4939.8  246.37  4940.6  246.33
  4979.8   244.3 4984.09  244.45  4984.2  244.45  4984.3   244.2 4984.41  243.94
  4985.1  242.24 4985.21  241.98  4985.3  241.75  4985.4  241.51  4986.4  239.06
  4986.7  237.16  4998.4  237.09  5002.1  237.06  5012.2  236.99  5013.5  239.03
 5023.69   243.5  5023.8  243.54 5023.91  243.59  5024.2  243.72  5026.1   243.7
 5026.19   243.7  5026.3   243.7  5026.4   243.7    5063  243.33  5063.5  243.33
  5123.1   243.9  5123.7  243.91  5184.1  245.53  5184.2  245.53    5246  246.43
  5283.1  246.34  5454.2  245.91  5523.1  245.65  5614.2  245.31  5663.1  246.17
  5774.2  248.11  5814.2  249.41  5952.3  251.22  5983.1  251.62  6023.1  252.14
  6063.1  252.66  6074.2  252.81  6094.2  252.71  6123.1  253.34  6214.2  255.31
  6303.1  258.27  6334.2  259.31  6342.8  259.78  6342.9  259.79  6354.2  260.41
  6358.4  260.61
BR D #Mann= 5
  2931.3     .07  4819.3     .13  4984.2     .07  5024.2     .13  5952.3     .07
BC Design=,, 0 ,, 0 ,,,,,,
BC HTab HWMax=260.48

Type RM Length L Ch R = 1 ,331726  ,145.9,145.9,145.9
BEGIN DESCRIPTION:
Downstream Section of Access Metal Bridge DS of Kickapoo
END DESCRIPTION:
XS GIS Cut Line= 5
    2950969.8367   13969817.6996    2950928.2969   13968561.1192
    2951097.0994   13967991.4104    2951095.9547   13966851.7385
    2951055.2584   13966417.6448
#Sta/Elev= 30
  2931.3  256.41  3284.4  254.41  3384.4  254.71  3604.4  253.61  3964.4  243.71
  4064.4  245.11  4124.4  246.81  4364.4  246.21  4544.4  248.51  4704.4  246.41
  4750.5  246.41  4819.3  248.09  4878.4  248.04  4939.8  246.37  4984.2  244.45
  4986.4  239.06  4986.7  237.16  5012.2  236.99  5013.5  239.03  5024.2  243.72
  5063.5  243.33  5123.1   243.9    5246  246.43  5614.2  245.31  5774.2  248.11
  5814.2  249.41  5952.3  251.22  6094.2  252.71  6214.2  255.31  6358.4  260.61
#Mann= 5 ,-1 , 0
  2931.3     .07       0  4819.3     .13       0  4984.2     .08       0
  5024.2     .13       0  5952.3     .07       0
#XS Ineff= 2 , 0
       0  4984.3  242.95  5024.2       0  242.95
Permanent Ineff=
       F       F
Bank Sta=4984.2,5024.2
XS Rating Curve= 0
Exp/Cntr=.5,.3