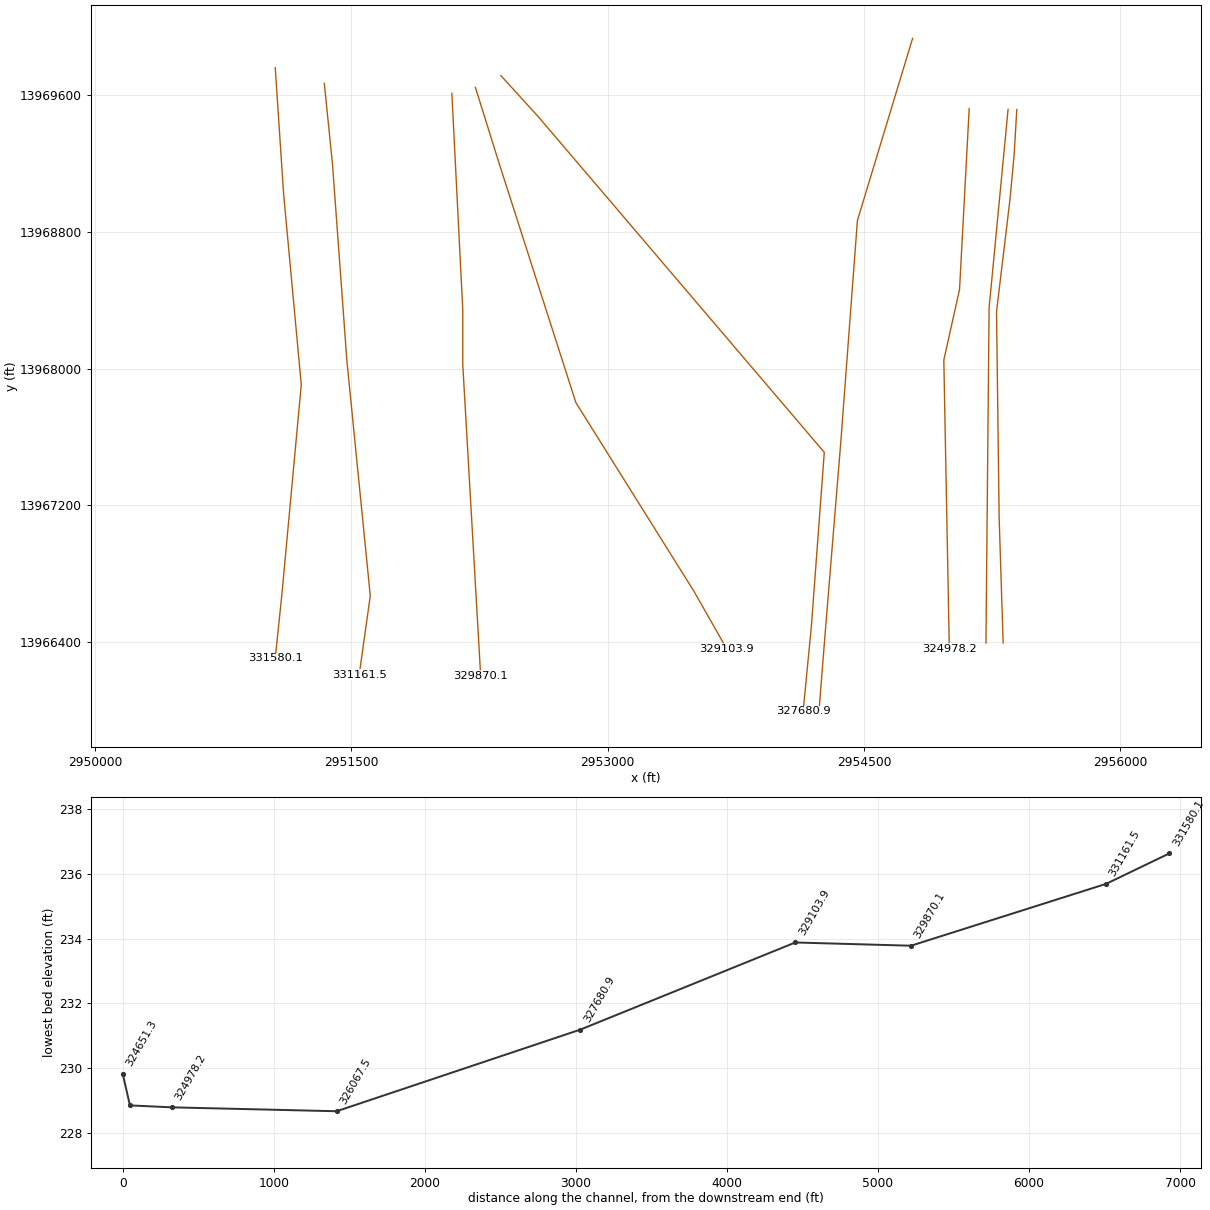
HEC-RAS study J100-00-00.prj: J100-00-00

--- J100-00-00.g01 (geometry) --- (continued)

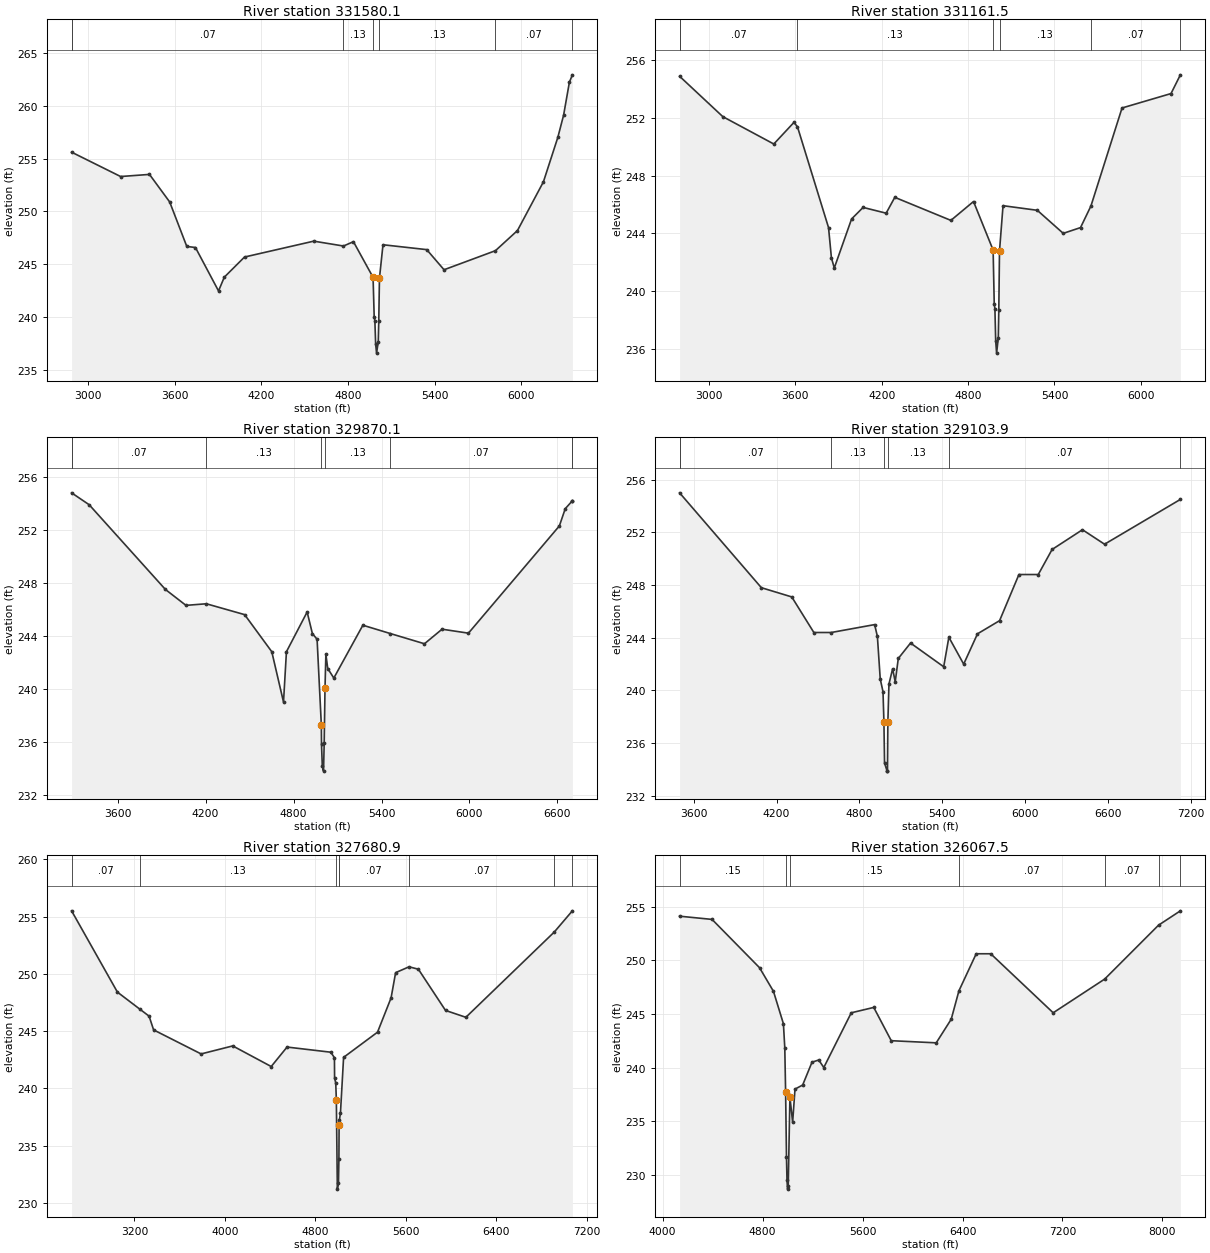
Type RM Length L Ch R = 1 ,331580.1,297.96,418.6,435.48
BEGIN DESCRIPTION:
Cross Section XS263
END DESCRIPTION:
XS GIS Cut Line= 5
    2951053.6335   13969761.7175    2951102.4641    13969024.684
     2951206.005   13967906.4432    2951092.8303   13966682.7422
    2951053.6335   13966304.1065
#Sta/Elev= 30
  2884.2   255.6  3224.2   253.3  3424.2   253.5  3564.2   250.9  3682.8   246.7
  3742.8   246.6  3902.8   242.5  3942.8   243.8  4082.8   245.7  4562.8   247.2
  4768.8  246.74  4837.9  247.15    4974  243.78  4981.8  240.03  4986.5   239.7
  4991.8  237.49  4998.2  236.63    5010   237.7  5013.5  239.65  5018.3  243.71
  5042.8  246.86  5345.9   246.4  5465.9   244.5  5822.2   246.3  5974.8   248.2
  6154.8   252.8  6254.8     257  6294.8   259.1  6334.8   262.2  6355.5   262.9
#Mann= 7 , 1 , 0
  2884.2      .2       0  2884.2     .07       0  4768.8     .13       0
    4974     .08       0  5018.3     .13       0  5822.2     .07       0
  6355.5      .2       0
Bank Sta=4974,5018.3
XS Rating Curve= 0
Exp/Cntr=.3,.1

Type RM Length L Ch R = 1 ,331161.5,717.1,1291.4,669.71
BEGIN DESCRIPTION:
Cross Section XS262
END DESCRIPTION:
XS GIS Cut Line= 5
    2951340.8104   13969669.8208    2951388.7186   13969198.1534
    2951472.5941   13968051.8554    2951609.9278   13966670.4391
    2951545.3002    13966209.967
#Sta/Elev= 30
  2797.3   254.9  3097.3   252.1  3451.4   250.2  3591.4   251.7  3615.9  251.39
  3831.4   244.4  3851.4   242.3  3871.4   241.6  3991.4     245  4071.4   245.8
  4231.4   245.4  4291.4   246.5  4680.8   244.9  4837.9  246.21    4974  242.84
  4981.8  239.09  4986.5  238.76  4991.8  236.55  4998.2  235.69    5010  236.76
  5013.5  238.71  5018.3  242.77  5042.8  245.92  5280.8   245.6  5460.8     244
  5580.8   244.4  5653.1   245.9    5869   252.7    6209   253.7    6274     255
#Mann= 7 , 1 , 0
  2797.3      .2       0  2797.3     .07       0  3615.9     .13       0
    4974     .08       0  5018.3     .13       0  5653.1     .07       0
    6274      .2       0
Bank Sta=4974,5018.3
XS Rating Curve= 0
Exp/Cntr=.3,.1

Type RM Length L Ch R = 1 ,329870.1,407.38,766.2,837.82
BEGIN DESCRIPTION:
Cross Section XS261
END DESCRIPTION:
XS GIS Cut Line= 4
    2952087.4706   13969612.3854    2952151.1845   13968348.8067
    2952151.1845     13968027.62    2952256.2045   13966201.8886
#Sta/Elev= 30
  3286.5   254.8  3406.5   253.9  3926.5   247.5  4066.5   246.3  4205.5  246.42
  4466.5   245.6  4651.7   242.8  4731.7     239  4751.7   242.8  4892.9   245.8
  4928.6  244.17  4960.7  243.74  4989.6  237.28  4990.9   235.8  4996.2  234.17
  5004.6  233.78  5009.1  235.88  5014.7  240.04  5020.6   242.6  5033.4  241.53
  5074.8  240.81  5272.9   244.8  5460.7  244.17  5692.9   243.4  5812.9   244.5
  5992.9   244.2  6612.9   252.3  6652.9   253.6  6699.1  254.17  6701.6   254.2
#Mann= 8 , 1 , 0
  3286.5      .2       0  3286.5     .07       0  4205.5     .13       0
  4989.6     .08       0  5014.7     .13       0  5460.7     .07       0
  6699.1     .07       0  6701.6      .2       0
Bank Sta=4989.6,5014.7
XS Rating Curve= 0
Exp/Cntr=.3,.1

Type RM Length L Ch R = 1 ,329103.9,1423,1423,1423
BEGIN DESCRIPTION:
Cross Section XS260
END DESCRIPTION:
XS GIS Cut Line= 5
    2952225.3156   13969646.8467    2952366.1693   13969196.1306
    2952813.6181   13967801.4232     2953504.621   13966697.3206
    2953695.6617   13966361.5419
#Sta/Elev= 30
  3498.2     255  4090.4   247.8  4310.4   247.1  4470.4   244.4    4596   244.4
  4910.4     245  4930.4   244.1  4950.9  240.88    4971  239.91  4977.7   237.6
  4982.1   234.5  5000.8  233.88  5003.4  233.91  5006.2   237.6  5014.1  240.49
  5040.7  241.65  5059.4  240.66  5081.7  242.43  5170.4   243.6  5410.4   241.8
  5447.8  244.04  5555.1     242  5655.1   244.3  5815.1   245.3  5955.1   248.8
  6095.1   248.8  6195.1   250.7  6415.1   252.2  6575.1   251.1    7124   254.5
#Mann= 7 , 1 , 0
  3498.2      .2       0  3498.2     .07       0    4596     .13       0
  4977.7     .08       0  5006.2     .13       0  5447.8     .07       0
    7124      .2       0
Bank Sta=4977.7,5006.2
XS Rating Curve= 0
Exp/Cntr=.3,.1

Type RM Length L Ch R = 1 ,327680.9,1604.38,1613.4,390.73
BEGIN DESCRIPTION:
Cross Section XS259
Ineffective at Sta 5600 based on high point in the floodplain
END DESCRIPTION:
XS GIS Cut Line= 5
    2952374.6476   13969715.7691    2952593.6465   13969475.1748
    2954267.7405   13967510.5987    2954191.8436    13966489.441
    2954143.6578   13965993.9554
#Sta/Elev= 30
  2644.6   255.5  3049.9   248.4  3245.5  246.93  3329.9   246.3  3369.9   245.1
  3789.9     243  4069.9   243.7  4409.9   241.9  4549.9   243.6  4936.7  243.15
  4968.9  242.67  4970.3  240.88  4980.4  240.47  4985.8  239.01  4994.7  231.19
  5004.6  231.74  5008.5  233.86  5010.2  236.78  5012.6   237.2  5022.1  237.84
  5049.9   242.7  5349.9   244.9  5469.9   247.9  5509.9   250.1  5628.8  250.61
  5711.1   250.4  5951.1   246.8  6131.1   246.2  6913.1  253.65  7072.9   255.5
#Mann= 8 ,-1 , 0
  2644.6     .07       0  3245.5     .13       0  4985.8     .08       0
  5010.2     .13       0  5012.6     .07       0  5628.8     .07       0
  6913.1     .07       0  7072.9      .2       0
#XS Ineff= 2 , 0
       0                    5600       0     248
Permanent Ineff=
       F       F
Bank Sta=4985.8,5010.2
XS Rating Curve= 0
Exp/Cntr=.3,.1

Type RM Length L Ch R = 1 ,326067.5,616.71,1089.3,709.83
BEGIN DESCRIPTION:
Cross Section XS258
Ineffective at Sta 6600 based on high point in the floodplain
END DESCRIPTION:
XS GIS Cut Line= 5
    2954784.7618   13969934.1361    2954461.6235   13968867.7797
     2954364.682   13967575.2264    2954271.0017   13966429.4446
    2954235.5545   13965982.4683
#Sta/Elev= 30
  4135.5   254.1  4395.5   253.8  4775.5   249.3  4886.9   247.1  4966.6  244.08
  4977.6  241.84  4984.2  237.72  4991.1  231.71  4995.1  229.54  4999.8  228.67
    5005  228.92  5018.6  237.25  5040.4   234.9  5059.3  237.99  5120.7  238.37
  5195.5   240.5  5249.7   240.7  5289.7     240  5509.7   245.1  5689.7   245.6
  5829.7   242.5  6189.7   242.3  6309.7   244.5  6371.5  247.15  6509.7   250.6
  6625.9   250.6  7125.9   245.1  7537.9  248.24  7968.8  253.26  8143.9   254.6
#Mann= 7 ,-1 , 0
  4135.5     .15       0  4984.2     .08       0  5018.6     .15       0
  6371.5     .07       0  7537.9     .07       0  7968.8     .07       0
  8143.9      .2       0
#XS Ineff= 2 , 0
       0                    6600       0     248
Permanent Ineff=
       F       F
Bank Sta=4984.2,5018.6
XS Rating Curve= 0
Exp/Cntr=.3,.1

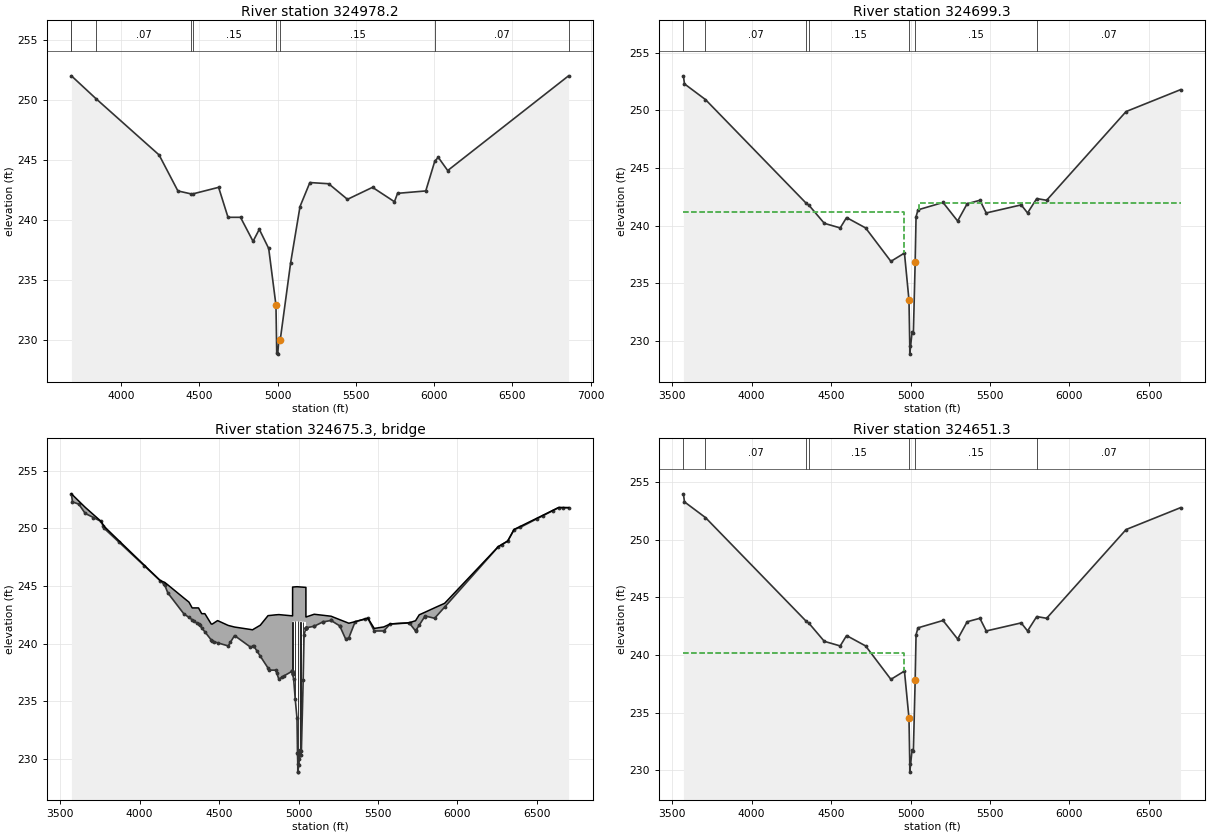
Type RM Length L Ch R = 1 ,324978.2,145.47,278.9,189.94
BEGIN DESCRIPTION:
Cross Section XS257
END DESCRIPTION:
XS GIS Cut Line= 4
    2955115.9785   13969522.1347    2955059.4293   13968463.8568
    2954967.4707   13968051.0863    2954999.6462   13966359.5737
#Sta/Elev= 30
    3684     252  3842.2  250.08    4244   245.4    4364   242.4  4449.4  242.15
  4458.4  242.15    4624   242.7    4684   240.2  4763.8   240.2  4843.8   238.2
  4883.8   239.2  4943.8   237.6  4990.2  232.87  4995.1  228.87  5001.2  228.79
  5009.6  230.12  5017.7     230  5083.8   236.4  5143.8   241.1  5206.7   243.1
  5326.7     243  5446.7   241.7  5606.7   242.7  5746.7   241.5  5766.7   242.2
  5946.7   242.4  6004.5  244.89  6026.7   245.2  6086.7   244.1  6858.5     252
#Mann= 9 , 1 , 0
    3684      .2       0    3684     .15       0  3842.2     .07       0
  4449.4     .15       0  4458.4     .15       0  4990.2     .08       0
  5017.7     .15       0  6004.5     .07       0  6858.5      .2       0
Bank Sta=4990.2,5017.7
XS Rating Curve= 0
Exp/Cntr=.5,.3

Type RM Length L Ch R = 1 ,324699.3,48,48,48
BEGIN DESCRIPTION:
Upstream Section of Kickapoo
END DESCRIPTION:
XS GIS Cut Line= 4
    2955343.5742   13969517.8993    2955232.4967   13968356.2137
    2955230.0392   13968093.8811      2955214.12   13966394.5075
#Sta/Elev= 30
  3570.5     253  3577.3   252.3  3709.4  250.94  4344.2  241.93  4360.6  241.77
  4457.3   240.2  4557.3   239.8  4597.3   240.7  4717.3   239.8  4876.3   236.9
  4961.6  237.62  4990.2  233.53  4995.1  229.53  4995.2  228.85  5009.6  230.78
  5017.7  230.66  5029.1  236.88  5034.6  240.77  5046.7  241.37  5204.4  242.01
  5296.3   240.4  5356.3   241.9  5436.3   242.2  5476.3   241.1  5696.3   241.8
  5736.3   241.1  5794.1  242.35  5856.3   242.2  6356.3   249.9  6699.1   251.8
#Mann= 7 ,-1 , 0
  3570.5     .15       0  3709.4     .07       0  4344.2     .15       0
  4360.6     .15       0  4990.2     .08       0  5029.1     .15       0
  5794.1     .07       0
#XS Ineff= 2 , 0
       0    4960   241.2    5050       0     242
Permanent Ineff=
       F       F
Bank Sta=4990.2,5029.1
XS Rating Curve= 0
Exp/Cntr=.5,.3

Type RM Length L Ch R = 3 ,324675.3,,,
BEGIN DESCRIPTION:
KICKAPOO
Structure ID: J100-00-00-17
Circular piers, twin-cylinder piers without diaphragm
END DESCRIPTION:
Node Name=Kickapoo
Bridge Culvert--1,0,-1,-1, 0
Deck Dist Width WeirC Skew NumUp NumDn MinLoCord MaxHiCord MaxSubmerge Is_Ogee
10,28,2.6,0, 60, 60, , , .95, 0, 1,1,,
  3570.5  3577.3  3617.3  3657.3  3757.3  3777.3  4130.5  4157.3  4177.3  4277.3
  4310.5  4330.5  4370.5  4377.3  4390.5  4410.5  4450.5  4457.3  4490.5  4557.3
  4597.3  4697.3  4710.5  4717.3  4759.2  4807.9  4816.3  4856.3  4876.3 4961.11
  4961.2 4962.39  4962.5  4990.2 5046.27 5046.38 5046.49  5046.6  5046.7  5098.3
  5204.4  5259.1  5296.3  5316.3  5356.3  5436.3  5476.3  5536.3  5576.3  5696.3
  5736.3  5759.2  5796.3  5856.3  5919.2  6256.3  6316.3  6356.3  6636.3  6699.1
     253  252.91  252.37  251.83  250.61  250.16  245.46  245.32   245.1  243.97
   243.6   243.1   243.1  242.93   242.6   242.6   241.7   241.7     242  241.58
  241.44  241.23   241.2  241.26   241.6  242.43  242.44   242.5  242.52  242.41
  242.41  242.41  244.91  244.94  244.88  242.38  242.36  242.33  242.31  242.55
  242.38  242.08  241.88  241.77  241.91  242.21  241.32  241.45  241.71  241.81
  241.99   242.5  242.73  243.11   243.5  248.41  248.91  249.91  251.81   251.8
     253   252.3   252.1   251.3   250.6     250  245.45   245.1   244.4   242.6
  242.27  242.07  241.67   241.6  241.37  241.02  240.32   240.2  240.07   239.8
   240.7   239.7  239.77   239.8  238.91  237.88   237.7   237.7   236.9  237.62
  241.91  241.91  241.91  241.94  241.88  241.88  241.86  241.36  241.37  241.51
  242.01  241.54   240.4   240.5   241.9   242.2   241.1   241.1   241.7   241.8
   241.1   241.6   242.4   242.2  243.17   248.4   248.9   249.9   251.8   251.8
  3570.5  3577.3  3617.3  3657.3  3757.3  3777.3  4130.5  4157.3  4177.3  4277.3
  4310.5  4330.5  4370.5  4377.3  4390.5  4410.5  4450.5  4457.3  4490.5  4557.3
  4597.3  4697.3  4710.5  4717.3  4759.2  4807.9  4816.3  4856.3  4876.3 4961.11
  4961.2 4962.39  4962.5  4990.2 5046.27 5046.38 5046.49  5046.6  5046.7  5098.3
  5204.4  5259.1  5296.3  5316.3  5356.3  5436.3  5476.3  5536.3  5576.3  5696.3
  5736.3  5759.2  5796.3  5856.3  5919.2  6256.3  6316.3  6356.3  6636.3  6699.1
     253  252.91  252.37  251.83  250.61  250.16  245.46  245.32   245.1  243.97
   243.6   243.1   243.1  242.93   242.6   242.6   241.7   241.7     242  241.58
  241.44  241.23   241.2  241.26   241.6  242.43  242.44   242.5  242.52  242.41
  242.41  242.41  244.91  244.94  244.88  242.38  242.36  242.33  242.31  242.55
  242.38  242.08  241.88  241.77  241.91  242.21  241.32  241.45  241.71  241.81
  241.99   242.5  242.73  243.11   243.5  248.41  248.91  249.91  251.81   251.8
     253   252.3   252.1   251.3   250.6     250  245.45   245.1   244.4   242.6
  242.27  242.07  241.67   241.6  241.37  241.02  240.32   240.2  240.07   239.8
   240.7   239.7  239.77   239.8  238.91  237.88   237.7   237.7   236.9  237.62
  241.91  241.91  241.91  241.94  241.88  241.88  241.86  241.36  241.37  241.51
  242.01  241.54   240.4   240.5   241.9   242.2   241.1   241.1   241.7   241.8
   241.1   241.6   242.4   242.2  243.17   248.4   248.9   249.9   251.8   251.8
Pier Skew, UpSta & Num, DnSta & Num=  ,4961.9, 2 ,4961.9, 2 , 0 , 0 , 0 ,,
       1       1
  236.39  242.91
       1       1
  236.39  242.91
Pier Skew, UpSta & Num, DnSta & Num=  ,4978.8, 2 ,4978.8, 2 , 0 , 0 , 0 ,,
       1       1
  234.15  242.92
       1       1
  234.15  242.92
Pier Skew, UpSta & Num, DnSta & Num=  ,4995.3, 2 ,4995.3, 2 , 0 , 0 , 0 ,,
       1       1
  227.91  242.94
       1       1
  227.91  242.94
Pier Skew, UpSta & Num, DnSta & Num=  ,5012.3, 2 ,5012.3, 2 , 0 , 0 , 0 ,,
       1       1
  229.33  242.92
       1       1
  229.33  242.92
Pier Skew, UpSta & Num, DnSta & Num=  ,5029.1, 2 ,5029.1, 2 , 0 , 0 , 0 ,,
       1       1
  235.61   242.9
       1       1
  235.61   242.9
Abutment Skew #Up #Dn= , 2 , 2
    4961  4993.4
  241.91  230.43
    4961  4993.4
  241.91  230.43
Abutment Skew #Up #Dn= , 2 , 2
  5006.7 5046.69
  230.34  241.86
  5006.7 5046.69
  230.34  241.86
BR Coef= 1 , 1 , 1 ,1.05, 0 ,,,.8,0,1.2,0,
WSPro=,,,, 1 ,,,, 0 ,,,, 0 ,,,,-1 ,-1 ,-1 , 0 , 0 , 0 , 0 , 0
BR U #Sta/Elev= 110
  3570.5     253  3577.3   252.3  3617.3   252.1  3657.3   251.3  3709.4  250.94
  3757.3   250.6  3770.5   250.2  3777.3     250  3870.5   248.8  4030.5  246.74
  4130.5  245.45  4150.5  245.19  4157.3   245.1  4177.3   244.4  4277.3   242.6
  4310.5  242.27  4330.5  242.07  4344.2  241.93  4360.6  241.77  4370.5  241.67
  4377.3   241.6  4390.5  241.37  4410.5  241.02  4450.5  240.32  4457.3   240.2
  4470.5  240.15  4490.5  240.07  4557.3   239.8  4570.5   240.1  4597.3   240.7
  4697.3   239.7  4710.5  239.77  4717.3   239.8  4736.3   239.4  4759.2  238.91
  4807.9  237.88  4816.3   237.7  4856.3   237.7  4861.6  237.49  4876.3   236.9
  4896.3   237.1  4909.8  237.21 4961.11  237.62  4961.2  237.62  4961.3  237.62
  4961.6  237.62  4961.9  237.42 4962.39  237.39  4962.5  237.38 4962.61  237.37
  4969.2  236.92  4978.8  235.22  4990.2  233.53  4993.3  230.53  4993.4  230.43
  4995.1  229.53  4995.2  228.85  4995.3  228.86  5001.2  229.45  5004.9     230
  5006.6  230.32  5006.7  230.34  5009.6  230.78  5012.3   230.3  5017.7  230.66
  5029.1  236.88  5034.6  240.77 5046.16  241.34 5046.27  241.34 5046.38  241.35
 5046.49  241.35  5046.6  241.36  5046.7  241.37  5046.8  241.37  5098.3  241.51
  5098.5  241.51  5152.7  241.88  5152.9  241.88  5204.2  242.01  5204.4  242.01
  5259.1  241.54  5259.3  241.53  5296.3   240.4  5316.3   240.5  5356.3   241.9
  5419.2  242.14  5436.3   242.2  5476.3   241.1  5536.3   241.1  5576.3   241.7
  5696.3   241.8  5699.2  241.75  5736.3   241.1  5739.2  241.16  5759.2   241.6
  5794.1  242.35  5796.3   242.4  5856.3   242.2  5919.2  243.17  6256.3   248.4
  6279.2  248.59  6316.3   248.9  6356.3   249.9  6396.3   250.1  6499.2  250.83
  6539.2  251.11  6599.2  251.54  6636.3   251.8  6665.9   251.8  6699.1   251.8
BR U #Mann= 7
  3570.5     .15  3709.4     .07  4344.2     .15  4360.6     .15  4990.2     .07
  5029.1     .15  5794.1     .07
BR D #Sta/Elev= 110
  3570.5  253.98  3577.3  253.28  3617.3  253.08  3657.3  252.28  3709.4  251.92
  3757.3  251.58  3770.5  251.18  3777.3  250.98  3870.5  249.78  4030.5  247.72
  4130.5  246.43  4150.5  246.17  4157.3  246.08  4177.3  245.38  4277.3  243.58
  4310.5  243.25  4330.5  243.05  4344.2  242.91  4360.6  242.75  4370.5  242.65
  4377.3  242.58  4390.5  242.35  4410.5     242  4450.5   241.3  4457.3  241.18
  4470.5  241.13  4490.5  241.05  4557.3  240.78  4570.5  241.08  4597.3  241.68
  4697.3  240.68  4710.5  240.75  4717.3  240.78  4736.3  240.38  4759.2  239.89
  4807.9  238.86  4816.3  238.68  4856.3  238.68  4861.6  238.47  4876.3  237.88
  4896.3  238.08  4909.8  238.19 4961.11   238.6  4961.2   238.6  4961.3   238.6
  4961.6   238.6  4961.9   238.4 4962.39  238.37  4962.5  238.36 4962.61  238.35
  4969.2   237.9  4978.8   236.2  4990.2  234.51  4993.3  231.51  4993.4  231.41
  4995.1  230.51  4995.2  229.83  4995.3  229.84  5001.2  230.43  5004.9  230.98
  5006.6   231.3  5006.7  231.32  5009.6  231.76  5012.3  231.28  5017.7  231.64
  5029.1  237.86  5034.6  241.75 5046.16  242.32 5046.27  242.32 5046.38  242.33
 5046.49  242.33  5046.6  242.34  5046.7  242.35  5046.8  242.35  5098.3  242.49
  5098.5  242.49  5152.7  242.86  5152.9  242.86  5204.2  242.99  5204.4  242.99
  5259.1  242.52  5259.3  242.51  5296.3  241.38  5316.3  241.48  5356.3  242.88
  5419.2  243.12  5436.3  243.18  5476.3  242.08  5536.3  242.08  5576.3  242.68
  5696.3  242.78  5699.2  242.73  5736.3  242.08  5739.2  242.14  5759.2  242.58
  5794.1  243.33  5796.3  243.38  5856.3  243.18  5919.2  244.15  6256.3  249.38
  6279.2  249.57  6316.3  249.88  6356.3  250.88  6396.3  251.08  6499.2  251.81
  6539.2  252.09  6599.2  252.52  6636.3  252.78  6665.9  252.78  6699.1  252.78
BR D #Mann= 7
  3570.5     .15  3709.4     .07  4344.2     .15  4360.6     .15  4990.2     .07
  5029.1     .15  5794.1     .07
BC Design=,, 0 ,, 0 ,,,,,,
BC HTab HWMax=253

Type RM Length L Ch R = 1 ,324651.3,202.8,202.8,202.8
BEGIN DESCRIPTION:
Downstream Section of Kickapoo
END DESCRIPTION:
XS GIS Cut Line= 6
    2955394.6096   13969516.3721    2955378.7727   13969248.0949
    2955354.2931    13968986.979    2955276.0181   13968334.6014
    2955291.3745   13967126.5583    2955314.7049   13966394.9585
#Sta/Elev= 30
  3570.5  253.98  3577.3  253.28  3709.4  251.92  4344.2  242.91  4360.6  242.75
  4457.3  241.18  4557.3  240.78  4597.3  241.68  4717.3  240.78  4876.3  237.88
  4961.6   238.6  4990.2  234.51  4995.1  230.51  4995.2  229.83  5009.6  231.76
  5017.7  231.64  5029.1  237.86  5034.6  241.75  5046.7  242.35  5204.4  242.99
  5296.3  241.38  5356.3  242.88  5436.3  243.18  5476.3  242.08  5696.3  242.78
  5736.3  242.08  5794.1  243.33  5856.3  243.18  6356.3  250.88  6699.1  252.78
#Mann= 7 ,-1 , 0
  3570.5     .15       0  3709.4     .07       0  4344.2     .15       0
  4360.6     .15       0  4990.2     .08       0  5029.1     .15       0
  5794.1     .07       0
#XS Ineff= 2 , 0
       0    4960   240.2    5050       0     241
Permanent Ineff=
       F       F
Bank Sta=4990.2,5029.1
XS Rating Curve= 0
Exp/Cntr=.5,.3