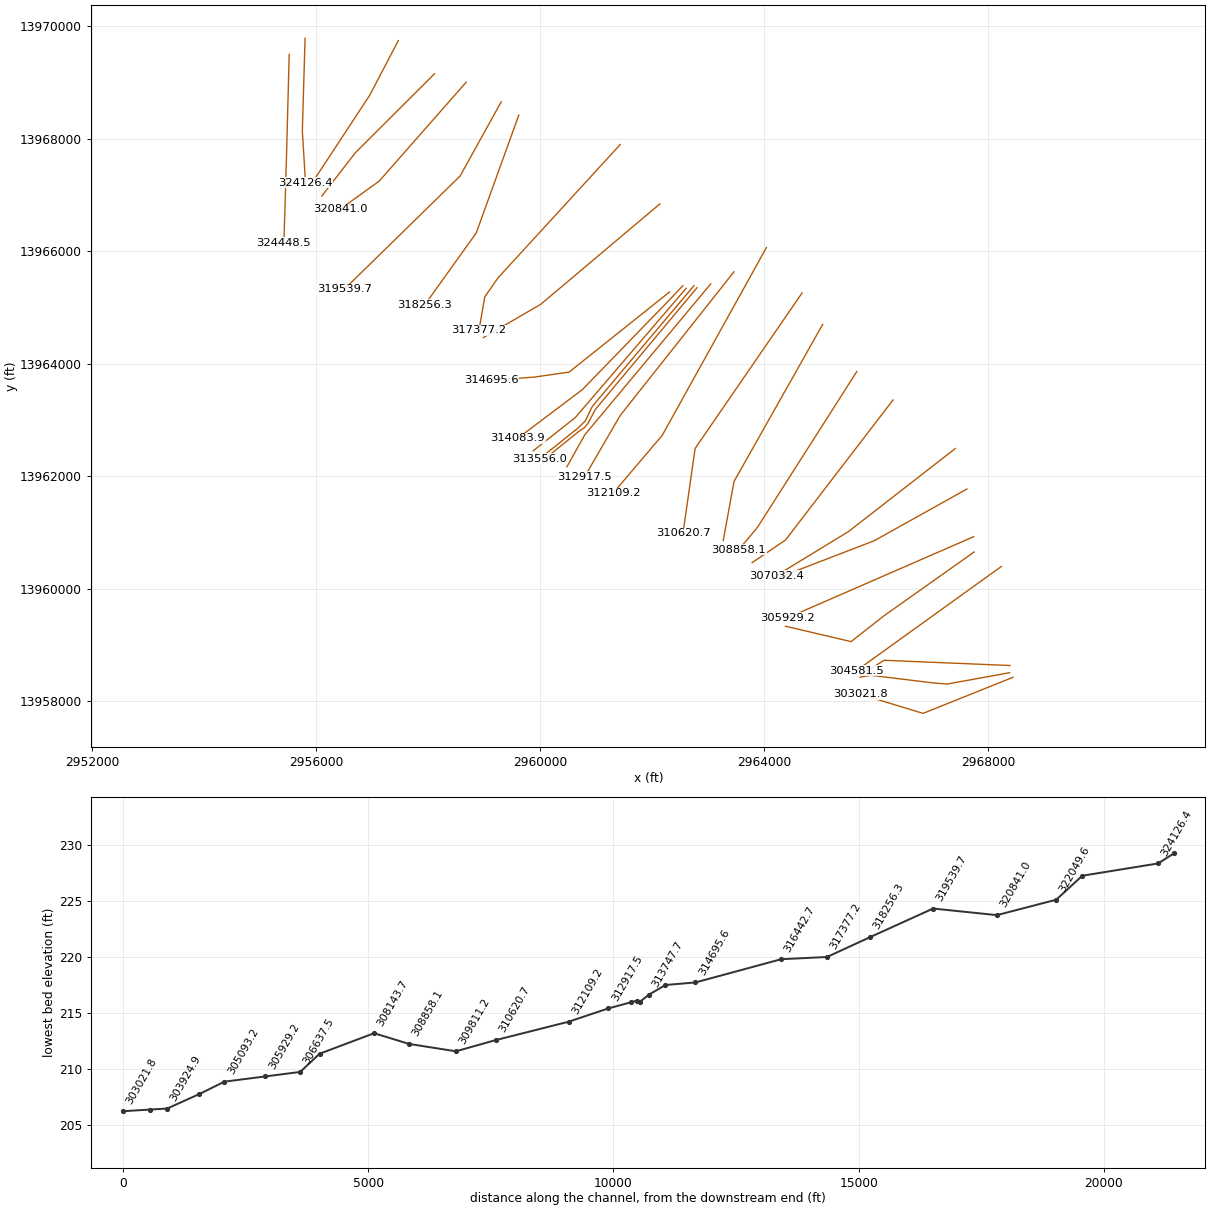
HEC-RAS study J100-00-00.prj: J100-00-00

--- J100-00-00.g01 (geometry) --- (continued)

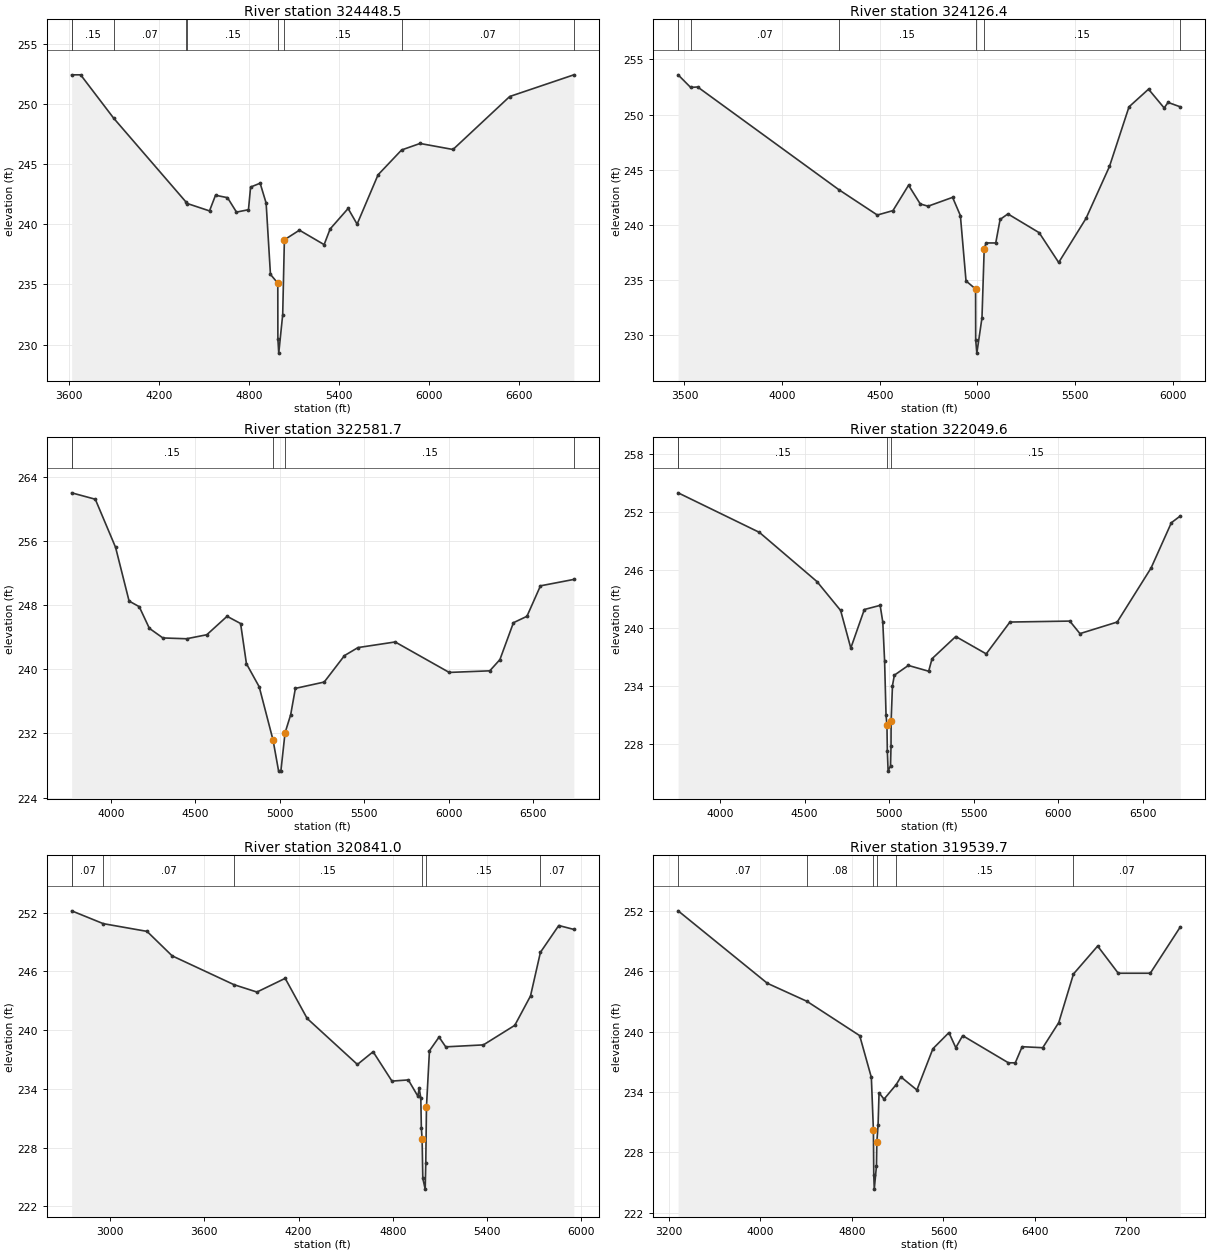
Type RM Length L Ch R = 1 ,324448.5,276.11,322.1,442.89
BEGIN DESCRIPTION:
Cross Section XS256
END DESCRIPTION:
XS GIS Cut Line= 4
    2955519.0509   13969503.5809    2955479.5091   13967979.1493
    2955441.9233   13966701.2317    2955423.8346   13966153.6612
#Sta/Elev= 30
  3614.9   252.4  3674.9   252.4  3895.3   248.8  4380.7   241.8  4387.5  241.71
  4534.9   241.1  4574.9   242.4  4654.9   242.2  4714.9     241  4794.9   241.2
    4809  243.08  4872.8   243.4  4912.7  241.75  4941.6  235.83  4990.6   235.1
  4991.1  230.48    4997  229.29  5023.3  232.49  5034.6   238.7  5134.9   239.5
  5299.8   238.3  5339.8   239.6  5459.8   241.3  5519.8     240  5659.8   244.1
  5816.8  246.16  5939.8   246.7  6159.8   246.2  6538.3   250.6  6966.2   252.4
#Mann= 9 , 1 , 0
  3614.9      .2       0  3614.9     .15       0  3895.3     .07       0
  4380.7     .15       0  4387.5     .15       0  4990.6     .08       0
  5034.6     .15       0  5816.8     .07       0  6966.2      .2       0
Bank Sta=4990.6,5034.6
XS Rating Curve= 0
Exp/Cntr=.3,.1

Type RM Length L Ch R = 1 ,324126.4,1410.89,1544.7,827.19
BEGIN DESCRIPTION:
Cross Section XS255
END DESCRIPTION:
XS GIS Cut Line= 3
    2955802.6475   13969788.7238    2955754.1767   13968140.7184
    2955810.7259   13967219.7743
#Sta/Elev= 30
  3467.4   253.6  3531.5  252.46  3567.4   252.5  4290.9  243.19  4487.4   240.9
  4567.4   241.3  4647.4   243.6  4707.4   241.9  4747.4   241.7  4872.8   242.5
  4912.7  240.85  4941.6  234.93  4990.6   234.2  4991.1  229.58    4997  228.39
  5023.3  231.59  5034.6   237.8  5043.8  238.37  5093.8  238.37  5116.1   240.5
  5156.1     241  5316.1   239.3  5416.1   236.6  5556.1   240.6  5676.1   245.3
  5776.1   250.7  5876.1   252.3  5956.1   250.6  5976.1   251.1  6038.8   250.7
#Mann= 7 , 1 , 0
  3467.4      .2       0  3467.4     .15       0  3531.5     .07       0
  4290.9     .15       0  4990.6     .08       0  5034.6     .15       0
  6038.8      .2       0
Bank Sta=4990.6,5034.6
XS Rating Curve= 0
Exp/Cntr=.3,.1

Type RM Length L Ch R = 1 ,322581.7,624.74,532.1,411.6
BEGIN DESCRIPTION:
Cross Section XS254
END DESCRIPTION:
XS GIS Cut Line= 3
    2957466.8098   13969748.3316    2956957.8669   13968778.9166
    2955923.8243   13967211.6958
#Sta/Elev= 30
  3767.1     262  3907.1   261.2  4027.1   255.2  4107.1   248.5  4167.1   247.8
  4227.1   245.1  4307.1   243.9  4447.1   243.8  4567.1   244.3  4687.1   246.6
  4767.1   245.7  4801.6  240.69  4877.2  237.81  4959.1  231.17  4991.8  227.33
  5005.5  227.29  5030.2  232.06  5063.5  234.32  5091.4  237.61    5262   238.4
    5382   241.7    5462   242.7    5682   243.4    6002   239.6    6242   239.8
    6302   241.2    6382   245.8    6462   246.6    6542   250.4  6739.6   251.2
#Mann= 5 , 1 , 0
  3767.1      .2       0  3767.1     .15       0  4959.1     .08       0
  5030.2     .15       0  6739.6      .2       0
Bank Sta=4959.1,5030.2
XS Rating Curve= 0
Exp/Cntr=.3,.1

Type RM Length L Ch R = 1 ,322049.6,629.27,1208.6,739.15
BEGIN DESCRIPTION:
Cross Section XS253
END DESCRIPTION:
XS GIS Cut Line= 3
    2958113.0864   13969158.6041    2956699.3563   13967752.9525
    2956101.5504    13966985.499
#Sta/Elev= 30
  3753.3     254  4233.3   249.9  4573.3   244.8  4713.3   241.8  4773.3   237.9
  4853.3   241.9  4946.7  242.33  4962.2  240.61    4973  236.56  4981.4  230.98
  4986.9  229.91  4989.1  227.27  4993.7  225.14    5008  225.69  5010.9  227.73
  5011.5  230.33  5019.5  234.01  5030.6  235.09  5113.3   236.1  5233.3   235.5
  5253.3   236.8  5393.3   239.1  5573.3   237.3  5713.3   240.6  6066.9   240.7
  6126.9   239.4  6346.9   240.6  6546.9   246.2  6666.9   250.9  6719.7   251.6
#Mann= 4 , 1 , 0
  3753.3      .2       0  3753.3     .15       0  4986.9     .08       0
  5011.5     .15       0
Bank Sta=4986.9,5011.5
XS Rating Curve= 0
Exp/Cntr=.3,.1

Type RM Length L Ch R = 1 ,320841.0,1009.29,1301.3,1075.09
BEGIN DESCRIPTION:
Cross Section XS252
END DESCRIPTION:
XS GIS Cut Line= 3
    2958676.8475   13969007.1587    2957126.8413   13967250.9488
    2956431.2654   13966751.9487
#Sta/Elev= 30
  2754.9   252.2  2956.2  250.89  3234.9   250.1  3394.9   247.6  3789.4  244.65
  3934.9   243.9  4114.9   245.3  4254.9   241.2  4574.9   236.5  4674.9   237.8
  4794.9   234.8  4899.2  234.92  4960.2  233.25  4968.1  234.11  4978.7  233.06
  4982.1  230.04    4987  228.85  4991.4  224.86  5006.6  223.76  5010.3  226.38
  5014.7  232.18  5033.7   237.9  5094.9   239.3  5137.3   238.3  5377.3   238.5
  5577.3   240.5  5677.3   243.5  5740.5  247.96  5857.3   250.7  5953.3   250.3
#Mann= 7 , 1 , 0
  2754.9      .2       0  2754.9     .07       0  2956.2     .07       0
  3789.4     .15       0    4987     .08       0  5014.7     .15       0
  5740.5     .07       0
Bank Sta=4987,5014.7
XS Rating Curve= 0
Exp/Cntr=.3,.1

Type RM Length L Ch R = 1 ,319539.7,689.19,1283.4,1021.67
BEGIN DESCRIPTION:
Cross Section XS251
END DESCRIPTION:
XS GIS Cut Line= 3
    2959303.0743   13968658.9317    2958570.9175   13967341.6761
    2956506.1993   13965330.3727
#Sta/Elev= 30
  3280.9     252  4060.9   244.8  4406.8  243.01    4868   239.6  4969.9  235.45
  4987.9  230.21    4991  225.77  4995.5  224.35  5014.7  226.69  5017.9  229.01
  5028.7  230.73  5037.2  233.92  5080.8  233.29  5186.8  234.73    5228   235.5
    5368   234.2    5508   238.3    5648   239.9    5708   238.4    5768   239.6
    6168   236.9    6228   236.9    6288   238.5    6468   238.4    6608   240.9
  6736.8  245.73    6948   248.5    7128   245.8    7408   245.8  7670.4   250.4
#Mann= 6 ,-1 , 0
  3280.9     .07       0  4406.8     .08       0  4987.9     .08       0
  5017.9     .08       0  5186.8     .15       0  6736.8     .07       0
Bank Sta=4987.9,5017.9
XS Rating Curve= 0
Exp/Cntr=.3,.1

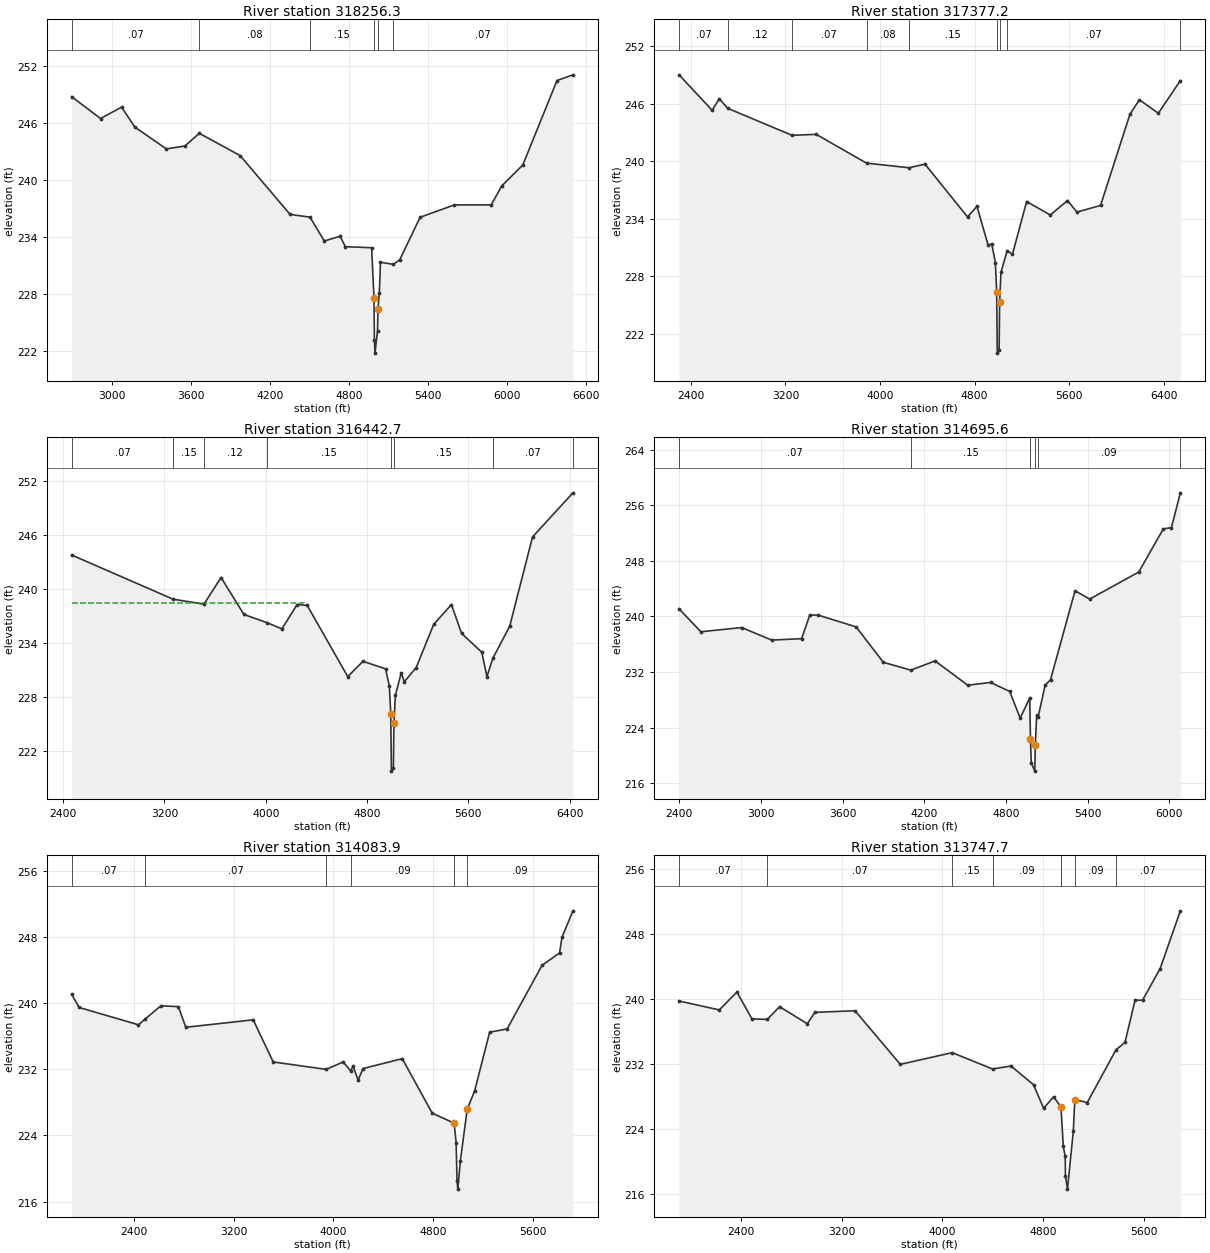
Type RM Length L Ch R = 1 ,318256.3,1127.71,879.1,828.53
BEGIN DESCRIPTION:
Cross Section XS250
END DESCRIPTION:
XS GIS Cut Line= 4
    2959617.3104   13968423.2547    2958858.2206   13966328.5546
    2957988.7506   13965118.8574    2957928.2658   13965050.8119
#Sta/Elev= 30
  2690.5   248.8  2910.5   246.5  3070.5   247.7  3170.5   245.6  3410.5   243.3
  3550.5   243.6  3660.8  244.94  3970.5   242.6  4350.5   236.4  4501.8  236.11
  4610.5   233.6  4730.5   234.1  4770.5     233  4969.9  232.89    4988  227.62
    4991  223.21  4995.5  221.79  5014.7  224.13  5017.9  226.45  5028.7  228.17
  5037.2  231.36  5135.7  231.14  5184.4  231.64  5338.5   236.1  5598.5   237.4
  5878.5   237.4  5958.5   239.4  6118.5   241.6  6378.5   250.5  6499.3   251.1
#Mann= 6 ,-1 , 0
  2690.5     .07       0  3660.8     .08       0  4501.8     .15       0
    4988     .08       0  5017.9     .15       0  5135.7     .07       0
Bank Sta=4988,5017.9
XS Rating Curve= 0
Exp/Cntr=.3,.1

Type RM Length L Ch R = 1 ,317377.2,1009.3,934.5,836.24
BEGIN DESCRIPTION:
Cross Section XS249
END DESCRIPTION:
XS GIS Cut Line= 4
    2961428.0743   13967900.6852    2959243.8116   13965527.1302
    2959010.5396   13965191.9179    2958906.3729   13964594.6956
#Sta/Elev= 30
  2300.4     249  2580.4   245.3  2640.4   246.5  2712.2  245.51  3255.9   242.7
  3460.4   242.8  3886.2   239.8  4246.2  239.32  4380.4   239.7  4740.4   234.2
  4820.4   235.3  4913.4  231.31    4946  231.36  4976.2  229.43    4987  226.37
  4992.2  220.01  5007.7  220.37  5012.1  225.37  5023.5  228.43    5076  230.69
  5120.4   230.3  5240.4   235.8  5440.4   234.4    5586   235.9    5666   234.7
    5866   235.4  6114.4   244.9  6194.4   246.4  6354.4     245  6540.7   248.4
#Mann= 9 ,-1 , 0
  2300.4     .07       0  2712.2     .12       0  3255.9     .07       0
  3886.2     .08       0  4246.2     .15       0    4987     .08       0
  5012.1     .15       0    5076     .07       0  6540.7      .2       0
Bank Sta=4987,5012.1
XS Rating Curve= 0
Exp/Cntr=.3,.1

Type RM Length L Ch R = 1 ,316442.7,1450.9,1747.1,1198.69
BEGIN DESCRIPTION:
Cross Section XS248
Ineffective at Sta 4300 based on floodplain confined upstream
END DESCRIPTION:
XS GIS Cut Line= 3
    2962135.5396   13966844.6956     2960007.433   13965058.3725
    2958986.7509   13964468.6451
#Sta/Elev= 30
  2467.6   243.8  3269.8  238.89  3512.5  238.35  3647.6   241.3  3827.6   237.2
  4007.5   236.3  4127.6   235.6  4247.6   238.3  4327.6   238.2  4647.6   230.3
  4767.6     232    4946  231.16  4976.2  229.23    4987  226.17  4992.2  219.81
  5007.7  220.17  5012.1  225.17  5023.5  228.23  5070.2  230.74  5093.8  229.73
  5187.6   231.3  5326.1   236.1  5466.1   238.3  5546.1   235.1  5706.1     233
  5746.1   230.3  5793.6  232.36  5926.1   235.9  6106.1   245.8  6424.9   250.7
#Mann= 8 ,-1 , 0
  2467.6     .07       0  3269.8     .15       0  3512.5     .12       0
  4007.5     .15       0    4987     .08       0  5012.1     .15       0
  5793.6     .07       0  6424.9      .2       0
#XS Ineff= 2 , 0
       0    4300   238.5               0
Permanent Ineff=
       F       F
Bank Sta=4987,5012.1
XS Rating Curve= 0
Exp/Cntr=.3,.1

Type RM Length L Ch R = 1 ,314695.6,308.59,611.7,754.25
BEGIN DESCRIPTION:
Cross Section XS247
END DESCRIPTION:
XS GIS Cut Line= 4
     2962306.691   13965277.8431    2960515.4753   13963854.4663
    2959894.0239   13963765.5085    2959130.4024   13963712.5843
#Sta/Elev= 30
  2399.5   241.1  2559.5   237.8  2859.5   238.4  3079.5   236.6  3299.5   236.8
  3359.5   240.2  3419.5   240.2  3699.5   238.5  3899.5   233.4  4101.5  232.27
  4279.5   233.6  4519.5   230.1  4687.4   230.5  4827.4   229.2  4904.5  225.36
  4974.6  228.26    4980  222.35  4985.9  218.96  5011.6  217.73  5015.7  221.44
  5025.5   225.8  5035.7  225.46  5087.4   230.1  5127.4   230.9  5307.4   243.7
  5415.2   242.5  5775.2   246.4  5955.2   252.6  6015.2   252.8  6080.6   257.8
#Mann= 6 ,-1 , 0
  2399.5     .07       0  4101.5     .15       0    4980     .08       0
  5015.7     .15       0  5035.7     .09       0  6080.6      .2       0
Bank Sta=4980,5015.7
XS Rating Curve= 0
Exp/Cntr=.3,.1

Type RM Length L Ch R = 1 ,314083.9,189.63,336.2,332.27
BEGIN DESCRIPTION:
Cross Section XS246
END DESCRIPTION:
XS GIS Cut Line= 4
    2962544.8042   13965390.0988    2962314.2462   13965147.0477
    2960755.9332   13963546.2509    2959599.1601    13962676.781
#Sta/Elev= 30
  1902.4   241.1  1962.4   239.5  2437.4   237.4  2492.1   238.1  2617.4   239.7
  2757.4   239.6  2817.4   237.1  3357.4     238  3517.4   232.9  3942.6     232
  4077.4   232.9    4138  231.82  4157.4   232.4  4197.4   230.7  4237.4   232.1
  4551.4   233.3  4791.4   226.7  4967.2  225.49  4982.9  223.14  4990.1  218.52
  4996.5   217.5  5016.4  220.89  5071.9  227.17  5131.4   229.4  5251.4   236.5
  5391.4   236.9  5671.4   244.6  5811.4   246.1  5831.4     248  5918.5   251.2
#Mann= 6 ,-1 , 0
  1902.4     .07       0  2492.1     .07       0  3942.6     .15       0
    4138     .09       0  4967.2     .08       0  5071.9     .09       0
Bank Sta=4967.2,5071.9
XS Rating Curve= 0
Exp/Cntr=.3,.1

Type RM Length L Ch R = 1 ,313747.7,191.7,191.7,191.7
BEGIN DESCRIPTION:
Cross Section XS245
END DESCRIPTION:
XS GIS Cut Line= 3
    2962602.5614    13965341.815    2960627.4028   13963047.2508
    2959872.8216   13962453.0411
#Sta/Elev= 30
  1904.7   239.8  2224.7   238.7  2364.7   240.9  2484.7   237.6  2605.5  237.53
  2704.7   239.1  2924.7     237  2984.7   238.4  3304.7   238.6  3664.7     232
  4077.5  233.44  4398.5  231.43  4544.7   231.8  4724.7   229.5  4804.7   226.6
  4884.7     228  4943.2  226.76  4961.5  221.89  4976.8  220.68  4978.7  218.26
  4994.8  216.64    5041  223.76    5053  227.66  5152.3   227.3  5380.6  233.79
  5452.3   234.7  5532.3   239.9  5592.3   239.9  5732.3   243.8  5892.7   250.9
#Mann= 7 ,-1 , 0
  1904.7     .07       0  2605.5     .07       0  4077.5     .15       0
  4398.5     .09       0  4943.2     .08       0    5053     .09       0
  5380.6     .07       0
Bank Sta=4943.2,5053
XS Rating Curve= 0
Exp/Cntr=.5,.3

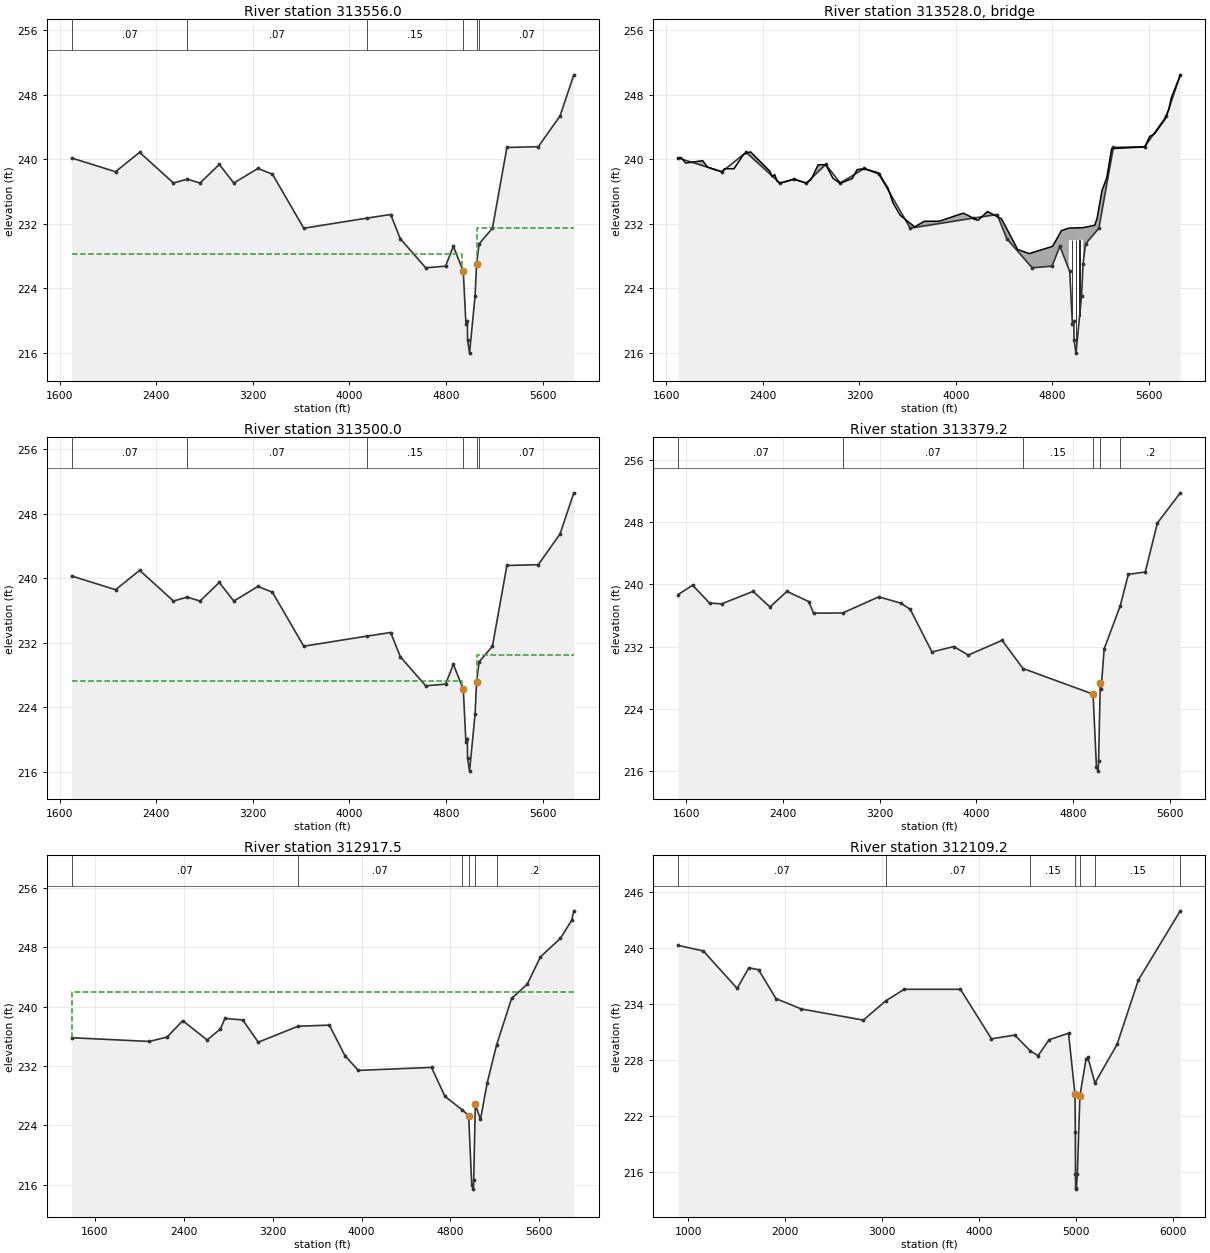
Type RM Length L Ch R = 1 ,313556.0,56,56,56
BEGIN DESCRIPTION:
Upstream Section of Margerstadt Harvester
END DESCRIPTION:
XS GIS Cut Line= 6
    2962743.1002   13965389.9559    2960927.4457   13963241.2458
    2960803.8992   13962985.0685    2960656.6473   13962842.9371
    2960607.8995   13962806.2046    2959983.7132    13962308.573
#Sta/Elev= 30
  1697.8  240.14  2061.3  238.44  2261.3  240.84  2541.3  237.04  2655.4  237.52
  2761.3  237.04  2921.3  239.34  3041.3  237.04  3241.3  238.84  3361.3  238.14
  3621.3  231.44    4147   232.7  4341.3  233.14  4421.3  230.14  4631.4  226.54
  4795.8  226.74    4861   229.2  4943.2  226.09    4965  219.52  4976.8  220.01
  4978.7  217.59  4994.8  215.97  5040.9  223.09  5052.9  226.99    5074   229.5
  5184.5  231.44  5304.5  241.44  5564.5  241.54  5744.5  245.34  5859.1  250.44
#Mann= 6 ,-1 , 0
  1697.8     .07       0  2655.4     .07       0    4147     .15       0
  4943.2     .08       0  5052.9     .09       0    5074     .07       0
#XS Ineff= 2 , 0
       0  4935.1   228.3  5053.4       0   231.5
Permanent Ineff=
       F       F
Bank Sta=4943.2,5052.9
XS Rating Curve= 0
Exp/Cntr=.5,.3

Type RM Length L Ch R = 3 ,313528.0,,,
BEGIN DESCRIPTION:
MARGERSTADT HARVESTER
Structure ID: J100-00-00-16
Square nose piers
END DESCRIPTION:
Node Name=Margerstadt Harv
Bridge Culvert--1,0,-1,-1, 0
Deck Dist Width WeirC Skew NumUp NumDn MinLoCord MaxHiCord MaxSubmerge Is_Ogee
10,36,2.6,0, 60, 60, , , .95, 0, 1,1,,
  1697.8  1721.3  1761.3  1901.3  1941.3  2061.3  2081.3  2161.3  2241.3  2297.8
  2457.8  2477.8  2497.8  2517.8  2541.3  2661.3  2761.3  2801.3  2857.8  2921.3
  2981.3  3041.3  3141.3  3181.3  3241.3  3357.8  3437.8  3477.8  3537.8  3657.8
  3737.8  3861.3  4061.3  4181.3  4261.3  4377.8  4511.4    4607    4801  4874.3
 4928.91  4935.1 4935.21  4935.3  4935.7  5052.9 5053.29  5053.4    5150    5170
    5210    5250    5290  5564.5  5604.5  5644.5    5730  5764.5  5784.5  5859.1
   240.1  240.21  239.51  239.81  239.01  238.41  238.81  238.81  240.61   240.9
   238.5   237.8   238.1  237.27  237.01  237.51  237.01  237.51   239.3  239.31
  237.61     237  237.61  238.71  238.81   238.3   236.4   234.6  233.05   231.6
   232.3  232.31  233.31  232.41  233.51   232.6  228.81   228.3   229.2  231.14
  231.43  231.44  231.44  231.44  231.45  231.51  231.51  231.51   231.8   232.7
   236.1   237.7   241.3  241.51  242.81  243.11  244.88  246.21  247.61   250.4
                                                                                
                                                                                
                                                                                
                                                                                
          227.07  227.07  229.94  229.95  230.01  230.01
                                                                                
  1697.8  1721.3  1761.3  1901.3  1941.3  2061.3  2081.3  2161.3  2241.3  2297.8
  2457.8  2477.8  2497.8  2517.8  2541.3  2661.3  2761.3  2801.3  2857.8  2921.3
  2981.3  3041.3  3141.3  3181.3  3241.3  3357.8  3437.8  3477.8  3537.8  3657.8
  3737.8  3861.3  4061.3  4181.3  4261.3  4377.8  4511.4    4607    4801  4874.3
 4928.91  4935.1 4935.21  4935.3  4935.7  5052.9 5053.29  5053.4    5150    5170
    5210    5250    5290  5564.5  5604.5  5644.5    5730  5764.5  5784.5  5859.1
   240.1  240.21  239.51  239.81  239.01  238.41  238.81  238.81  240.61   240.9
   238.5   237.8   238.1  237.27  237.01  237.51  237.01  237.51   239.3  239.31
  237.61     237  237.61  238.71  238.81   238.3   236.4   234.6  233.05   231.6
   232.3  232.31  233.31  232.41  233.51   232.6  228.81   228.3   229.2  231.14
  231.43  231.44  231.44  231.44  231.45  231.51  231.51  231.51   231.8   232.7
   236.1   237.7   241.3  241.51  242.81  243.11  244.88  246.21  247.61   250.4
                                                                                
                                                                                
                                                                                
                                                                                
          227.07  227.07  229.94  229.95  230.01  230.01
                                                                                
Pier Skew, UpSta & Num, DnSta & Num=  ,4965, 2 ,4965, 2 , 0 , 0 , 0 ,,
     1.4     1.4
  218.51  230.97
     1.4     1.4
  218.69  231.15
Pier Skew, UpSta & Num, DnSta & Num=  ,4994.8, 2 ,4994.8, 2 , 0 , 0 , 0 ,,
     1.4     1.4
  215.07  230.97
     1.4     1.4
  215.25  231.15
Pier Skew, UpSta & Num, DnSta & Num=  ,5024.2, 2 ,5024.2, 2 , 0 , 0 , 0 ,,
     1.4     1.4
  218.91  230.97
     1.4     1.4
  219.09  231.15
Abutment Skew #Up #Dn= , 2 , 2
  4935.1  4936.8
  229.94  227.03
  4935.1  4936.8
  230.12  227.21
BR Coef= 1 , 1 , 1 ,1.25, 0 ,,,.8,0,2,0,
WSPro=,,,, 1 ,,,, 0 ,,,, 0 ,,,,-1 ,-1 ,-1 , 0 , 0 , 0 , 0 , 0
BR U #Sta/Elev= 30
  1697.8  240.14  2061.3  238.44  2261.3  240.84  2541.3  237.04  2655.4  237.52
  2761.3  237.04  2921.3  239.34  3041.3  237.04  3241.3  238.84  3361.3  238.14
  3621.3  231.44    4147   232.7  4341.3  233.14  4421.3  230.14  4631.4  226.54
  4795.8  226.74    4861   229.2  4943.2  226.09    4965  219.52  4976.8  220.01
  4978.7  217.59  4994.8  215.97  5040.9  223.09  5052.9  226.99    5074   229.5
  5184.5  231.44  5304.5  241.44  5564.5  241.54  5744.5  245.34  5859.1  250.44
BR U #Mann= 6
  1697.8     .07  2655.4     .07    4147     .15  4943.2    .075  5052.9     .09
    5074     .07
BR D #Sta/Elev= 30
  1697.8  240.27  2061.3  238.57  2261.3  240.97  2541.3  237.17  2655.4  237.65
  2761.3  237.17  2921.3  239.47  3041.3  237.17  3241.3  238.97  3361.3  238.27
  3621.3  231.57    4147  232.83  4341.3  233.27  4421.3  230.27  4631.4  226.67
  4795.8  226.87    4861  229.33  4943.2  226.22    4965  219.65  4976.8  220.14
  4978.7  217.72  4994.8   216.1  5040.9  223.22  5052.9  227.12    5074  229.63
  5184.5  231.57  5304.5  241.57  5564.5  241.67  5744.5  245.47  5859.1  250.57
BR D #Mann= 6
  1697.8     .07  2655.4     .07    4147     .15  4943.2    .075  5052.9     .09
    5074     .07
BC Design=,, 0 ,, 0 ,,,,,,
BC HTab HWMax=250.44

Type RM Length L Ch R = 1 ,313500.0,120.8,120.8,120.8
BEGIN DESCRIPTION:
Downstream Section of Margerstadt Harvester
END DESCRIPTION:
XS GIS Cut Line= 6
     2962798.374   13965354.9983    2960982.3228   13963189.5195
    2960854.6703   13962947.0748    2960792.4616   13962867.7253
    2960706.6321   13962813.1932    2960036.2995    13962276.032
#Sta/Elev= 30
  1697.8  240.27  2061.3  238.57  2261.3  240.97  2541.3  237.17  2655.4  237.65
  2761.3  237.17  2921.3  239.47  3041.3  237.17  3241.3  238.97  3361.3  238.27
  3621.3  231.57    4147  232.83  4341.3  233.27  4421.3  230.27  4631.4  226.67
  4795.8  226.87    4861  229.33  4943.2  226.22    4965  219.65  4976.8  220.14
  4978.7  217.72  4994.8   216.1  5040.9  223.22  5052.9  227.12    5074  229.63
  5184.5  231.57  5304.5  241.57  5564.5  241.67  5744.5  245.47  5859.1  250.57
#Mann= 6 ,-1 , 0
  1697.8     .07       0  2655.4     .07       0    4147     .15       0
  4943.2     .08       0  5052.9     .09       0    5074     .07       0
#XS Ineff= 2 , 0
       0  4935.1   227.3  5053.4       0   230.5
Permanent Ineff=
       F       F
Bank Sta=4943.2,5052.9
XS Rating Curve= 0
Exp/Cntr=.5,.3

Type RM Length L Ch R = 1 ,313379.2,316.69,461.7,417.62
BEGIN DESCRIPTION:
Cross Section XS244
END DESCRIPTION:
XS GIS Cut Line= 3
    2963043.8258   13965423.7614    2960793.7362   13962737.2659
    2960476.1907   13962170.2203
#Sta/Elev= 30
  1531.8   238.7  1651.8   239.9  1791.8   237.6  1891.8   237.5  2151.8   239.1
  2291.8   237.1  2431.8   239.1  2611.8   237.8  2651.8   236.3  2892.7  236.32
  3191.8   238.4  3371.8   237.6  3451.8   236.8  3631.8   231.3  3811.8     232
  3931.8   230.9  4211.8   232.8  4384.7  229.17  4964.3  225.87  4992.4  216.47
  5005.9  215.95    5010  217.23  5024.3  227.36    5031  226.52  5056.1   231.7
  5188.5  237.21  5256.1   241.3  5396.1   241.6  5496.1   247.9    5686   251.8
#Mann= 6 ,-1 , 0
  1531.8     .07       0  2892.7     .07       0  4384.7     .15       0
  4964.3     .08       0  5024.3     .15       0  5188.5      .2       0
Bank Sta=4964.3,5024.3
XS Rating Curve= 0
Exp/Cntr=.3,.1

Type RM Length L Ch R = 1 ,312917.5,711.62,808.3,715.98
BEGIN DESCRIPTION:
Cross Section XS243
END DESCRIPTION:
XS GIS Cut Line= 3
    2963458.1868   13965637.6855    2961428.8273   13963085.0538
    2960793.7362   13961996.3263
#Sta/Elev= 30
  1390.1   235.8  2090.1   235.3  2250.1   235.9  2390.1   238.1  2610.1   235.5
  2730.1     237  2770.1   238.4  2930.1   238.2  3070.1   235.2  3428.9  237.35
  3710.1   237.5  3850.1   233.4  3970.1   231.4  4630.1   231.8  4751.1   227.9
  4905.5  226.09  4964.3  225.32  4992.4  215.92  5005.9   215.4    5010  216.68
  5024.3  226.81  5071.1   224.8  5131.1   229.7  5215.3   234.8  5351.1   241.1
  5491.1     243  5611.1   246.7  5791.1   249.2  5891.1   251.6  5911.5   252.9
#Mann= 6 ,-1 , 0
  1390.1     .07       0  3428.9     .07       0  4905.5     .15       0
  4964.3     .08       0  5024.3     .15       0  5215.3      .2       0
#XS Ineff= 2 , 0
       0  1390.1     242               0
Permanent Ineff=
       F       F
Bank Sta=4964.3,5024.3
XS Rating Curve= 0
Exp/Cntr=.3,.1

Type RM Length L Ch R = 1 ,312109.2,678.74,1488.5,1362
BEGIN DESCRIPTION:
Cross Section XS242
END DESCRIPTION:
XS GIS Cut Line= 4
    2964036.5136   13966068.9605    2963741.5321    13965537.091
    2962177.3275   13962729.7053    2961300.2969   13961701.4626
#Sta/Elev= 30
   897.1   240.3  1157.1   239.7  1505.3   235.7  1625.3   237.9  1725.3   237.7
  1905.3   234.6  2165.3   233.5  2805.3   232.3  3034.1  234.35  3225.3   235.6
  3805.3   235.6  4125.3   230.3  4365.3   230.7  4523.4  229.02  4605.3   228.5
    4719   230.2    4919   230.9  4985.2   224.4  4989.1  220.29  4990.5  215.82
    4992  214.34  4998.4  214.21  5009.6  215.79  5036.2  224.21    5099   228.1
    5119   228.3  5190.9  225.57    5419   229.7    5639   236.6  6070.5     244
#Mann= 7 ,-1 , 0
   897.1     .07       0  3034.1     .07       0  4523.4     .15       0
  4985.2     .08       0  5036.2     .15       0  5190.9     .15       0
  6070.5      .2       0
Bank Sta=4985.2,5036.2
XS Rating Curve= 0
Exp/Cntr=.3,.1

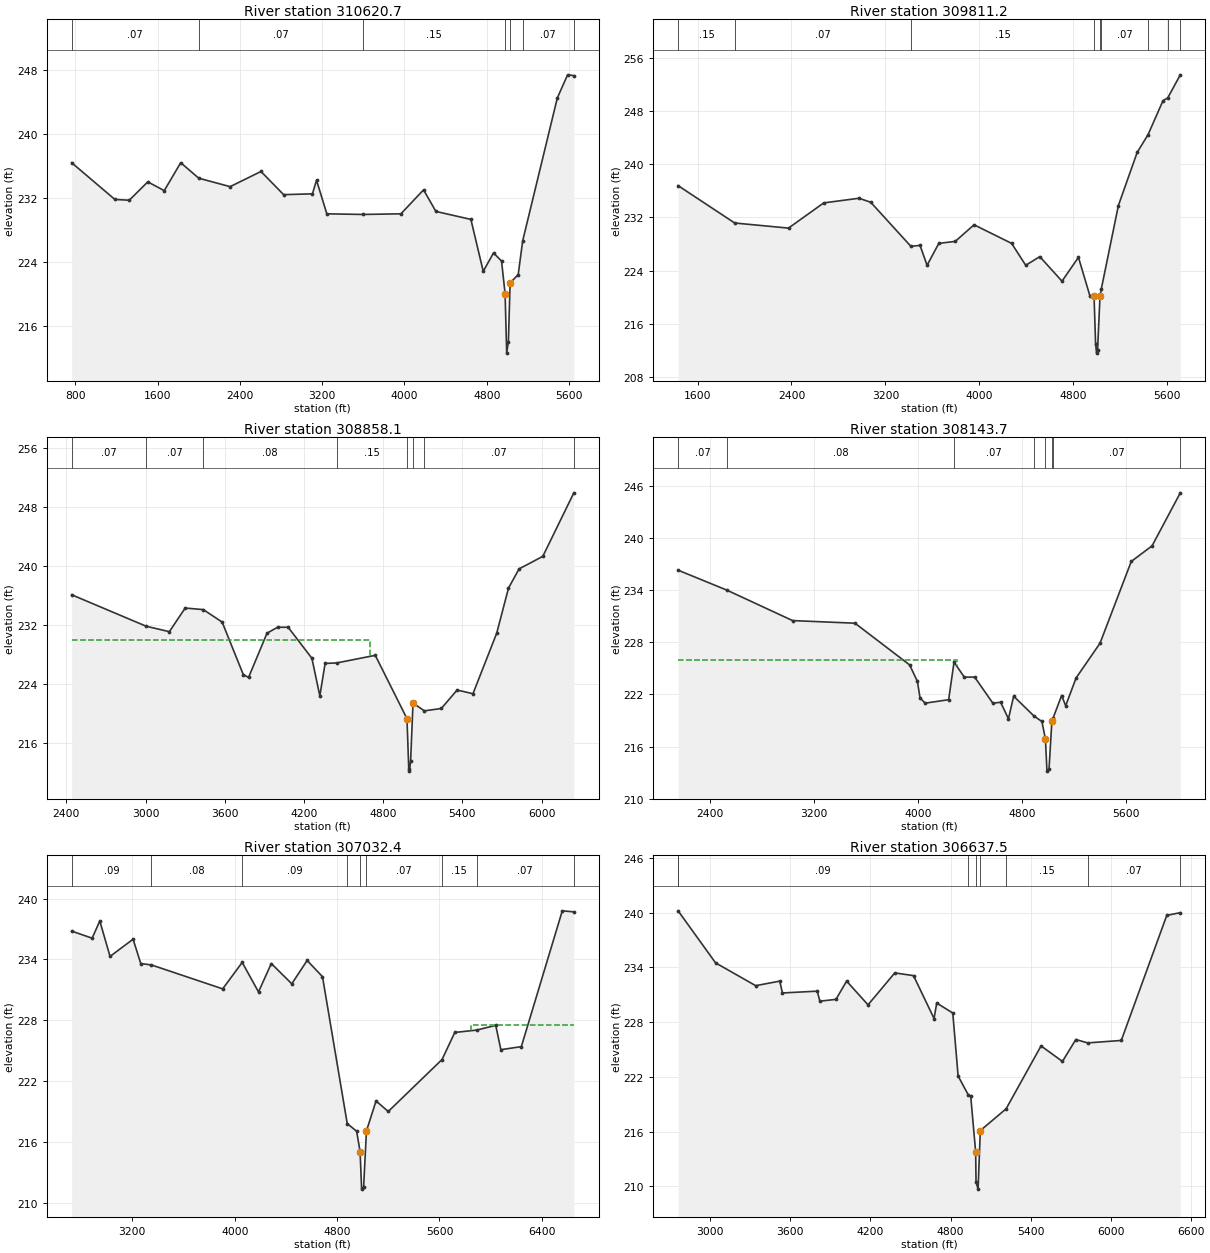
Type RM Length L Ch R = 1 ,310620.7,858.37,809.5,764.4
BEGIN DESCRIPTION:
Cross Section XS241
Ineffective at Sta 4200 based on topo upstream of side channel
END DESCRIPTION:
XS GIS Cut Line= 3
    2964673.6546   13965261.8501    2962764.5435   13962496.9654
    2962548.4053   13960991.7171
#Sta/Elev= 30
   765.4   236.4  1185.4   231.8  1325.4   231.7  1505.4     234  1665.4   232.9
  1825.4   236.4  2000.6  234.46  2305.4   233.4  2605.4   235.3  2825.4   232.4
  3105.4   232.5  3145.4   234.2  3245.4     230  3593.4  229.92  3965.4     230
  4185.4     233  4305.4   230.3  4645.4   229.3  4765.4   222.8  4865.4   225.1
  4943.4  224.09  4977.9  220.01  4993.4  212.56    5010     214  5026.6  221.34
  5105.4   222.4  5148.9  226.62  5485.4   244.5  5585.4   247.4    5646   247.3
#Mann= 7 ,-1 , 0
   765.4     .07       0  2000.6     .07       0  3593.4     .15       0
  4977.9     .08       0  5026.6     .15       0  5148.9     .07       0
    5646      .2       0
#XS Ineff= 2 , 0
       0    4200     230               0
Permanent Ineff=
       F       F
Bank Sta=4977.9,5026.6
XS Rating Curve= 0
Exp/Cntr=.3,.1

Type RM Length L Ch R = 1 ,309811.2,836.11,953.1,660.8
BEGIN DESCRIPTION:
Cross Section XS240
Ineffective at Sta 4000 based on topo upstream of side channel
END DESCRIPTION:
XS GIS Cut Line= 3
    2965041.4935   13964702.0952    2963459.2735   13961910.3045
    2963266.2929   13960860.4903
#Sta/Elev= 30
  1434.5   236.8  1916.3  231.17  2374.5   230.4  2674.5   234.2  2974.5   234.9
  3074.5   234.3  3416.9  227.65  3494.5   227.8  3554.5   224.8  3654.5   228.1
  3794.5   228.4  3954.5   230.9  4274.5   228.1  4394.5   224.8  4514.5   226.1
  4703.5   222.4  4843.5     226  4942.2  220.13  4976.5  220.11  4989.6  212.93
  4997.8  211.56  5006.1  211.99  5027.2  220.16  5038.3  221.23  5183.5   233.8
  5343.5   241.8  5436.1  244.48  5563.5   249.6  5604.4  250.04  5710.9   253.5
#Mann= 9 ,-1 , 0
  1434.5     .15       0  1916.3     .07       0  3416.9     .15       0
  4976.5     .08       0  5027.2     .15       0  5038.3     .07       0
  5436.1     .15       0  5604.4     .07       0  5710.9      .2       0
#XS Ineff= 2 , 0
       0    4000     230               0
Permanent Ineff=
       F       F
Bank Sta=4976.5,5027.2
XS Rating Curve= 0
Exp/Cntr=.3,.1

Type RM Length L Ch R = 1 ,308858.1,651.25,714.4,563.82
BEGIN DESCRIPTION:
Cross Section XS239
Ineffective at Sta 4700 based on topo upstream of side channel
END DESCRIPTION:
XS GIS Cut Line= 3
    2965649.2274   13963862.4628    2963876.1115    13961092.067
    2963544.1849   13960698.3867
#Sta/Elev= 30
  2440.5   236.1  3004.6  231.84  3180.5   231.1  3300.5   234.3    3438  234.09
  3580.5   232.4  3740.5   225.3  3780.5   224.9  3920.5   230.9  4000.5   231.7
  4080.5   231.7  4260.5   227.5  4320.5   222.4  4360.5   226.8  4448.9  226.87
  4740.5   227.9  4980.8  219.32  4994.1  212.54  4999.5  212.22  5008.2   213.6
  5026.4  221.44  5112.2  220.38  5240.5   220.7  5360.5   223.2  5480.5   222.7
  5660.5   230.9  5749.7     237  5829.7   239.6  6009.7   241.3  6244.7   249.9
#Mann= 8 ,-1 , 0
  2440.5     .07       0  3004.6     .07       0    3438     .08       0
  4448.9     .15       0  4980.8     .08       0  5026.4     .15       0
  5112.2     .07       0  6244.7      .2       0
#XS Ineff= 2 , 0
       0    4700     230               0
Permanent Ineff=
       F       F
Bank Sta=4980.8,5026.4
XS Rating Curve= 0
Exp/Cntr=.3,.1

Type RM Length L Ch R = 1 ,308143.7,1042.37,1111.3,634.7
BEGIN DESCRIPTION:
Cross Section XS238
Ineffective at Sta 4300 based on topo upstream of side channel
END DESCRIPTION:
XS GIS Cut Line= 3
    2966296.9438   13963358.6834    2964377.8609   13960868.2096
    2963783.4808     13960466.81
#Sta/Elev= 30
  2155.7   236.3  2531.4     234  3035.7   230.5  3515.7   230.2  3935.7   225.4
  3995.7   223.5  4015.7   221.6  4055.7     221  4235.7   221.4  4277.3  225.72
  4355.7     224  4435.7     224  4575.7     221  4635.7   221.1  4695.7   219.2
  4735.7   221.8  4891.4  219.53  4952.8  218.89  4979.9  216.88  4991.8  213.18
  5007.4  213.39  5029.5  218.92  5037.9  219.25  5104.5  221.88  5135.7   220.7
  5215.7   223.9  5399.8   227.9  5639.8   237.3  5799.8   239.1    6017   245.2
#Mann= 8 ,-1 , 0
  2155.7     .07       0  2531.4     .08       0  4277.3     .07       0
  4891.4     .15       0  4979.9     .08       0  5029.5     .15       0
  5037.9     .07       0    6017      .2       0
#XS Ineff= 2 , 0
       0    4300     226               0
Permanent Ineff=
       F       F
Bank Sta=4979.9,5029.5
XS Rating Curve= 0
Exp/Cntr=.3,.1

Type RM Length L Ch R = 1 ,307032.4,473.41,394.9,239.13
BEGIN DESCRIPTION:
Cross Section XS237.5
Ineffective at Sta 5850 based on topo upstream of side channel
END DESCRIPTION:
XS GIS Cut Line= 3
    2967408.1752   13962495.4268    2965499.9209   13961017.3971
     2964209.247    13960233.278
#Sta/Elev= 30
  2726.1   236.8  2886.1   236.1  2946.1   237.8  3026.1   234.3  3206.1     236
  3266.1   233.6  3349.8  233.46  3906.1   231.1  4058.8  233.71  4186.1   230.8
  4286.1   233.6  4446.1   231.6  4566.1   233.9  4686.1   232.3  4879.3  217.81
  4952.8  217.05  4979.9  215.04  4991.8  211.34  5007.4  211.55  5029.5  217.08
  5104.5  220.04  5199.8     219  5620.2  224.13  5719.8   226.8  5889.7  227.03
  6039.8   227.5  6079.8   225.1  6239.8   225.4  6559.8   238.8    6650   238.7
#Mann= 9 ,-1 , 0
  2726.1     .09       0  3349.8     .08       0  4058.8     .09       0
  4879.3     .07       0  4979.9     .08       0  5029.5     .07       0
  5620.2     .15       0  5889.7     .07       0    6650      .2       0
#XS Ineff= 2 , 0
       0                    5850       0   227.5
Permanent Ineff=
       F       F
Bank Sta=4979.9,5029.5
XS Rating Curve= 0
Exp/Cntr=.3,.1

Type RM Length L Ch R = 1 ,306637.5,669.99,708.3,694.74
BEGIN DESCRIPTION:
Cross Section XS237
END DESCRIPTION:
XS GIS Cut Line= 3
     2967616.366   13961775.3767    2965961.0908   13960855.7794
    2964223.4765    13960188.918
#Sta/Elev= 30
  2762.9   240.2  3042.9   234.5  3342.9     232  3522.9   232.5  3542.9   231.2
  3802.9   231.4  3822.9   230.3  3942.9   230.5  4022.9   232.5  4182.9   229.9
  4382.9   233.4  4522.9   233.1  4676.5   228.4  4696.5   230.1  4816.5     229
  4856.5   222.1  4932.9  220.02  4950.7  219.89  4987.6  213.78  4990.4  210.48
  5005.7  209.71  5022.3  216.12  5215.2  218.51  5476.5   225.4  5636.5   223.7
  5736.5   226.1    5825  225.73  6076.5     226  6416.5   239.7  6517.7     240
#Mann= 8 , 1 , 0
  2762.9      .2       0  2762.9     .09       0  4932.9     .07       0
  4987.6     .08       0  5022.3     .07       0  5215.2     .15       0
    5825     .07       0  6517.7      .2       0
Bank Sta=4987.6,5022.3
XS Rating Curve= 0
Exp/Cntr=.3,.1

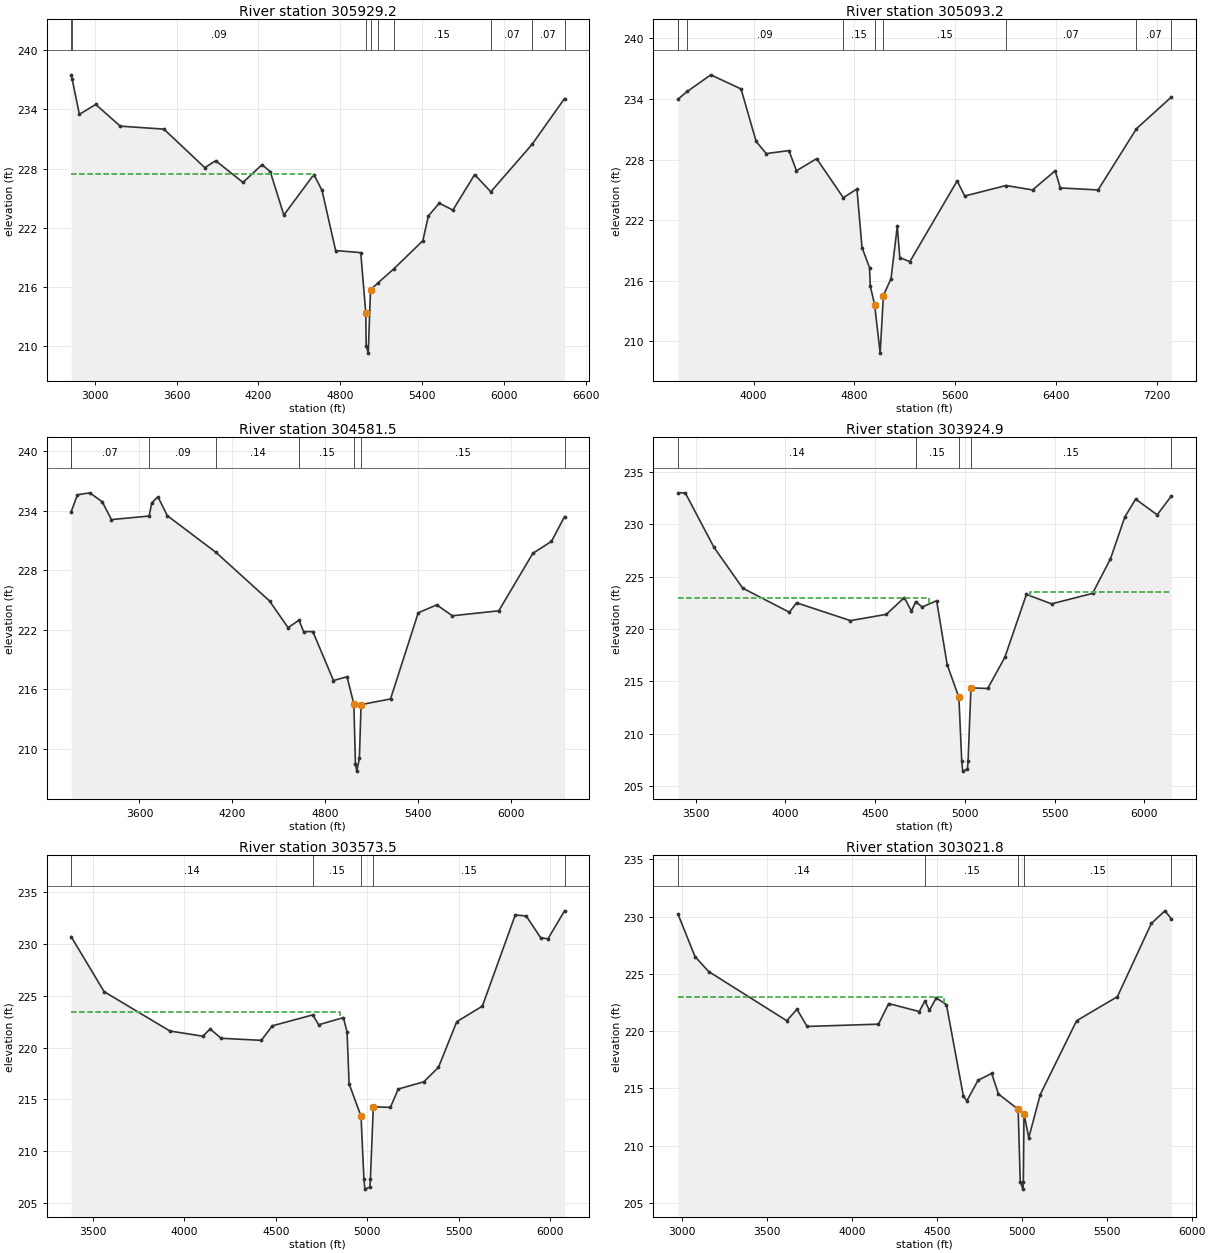
Type RM Length L Ch R = 1 ,305929.2,512.83,836,780.39
BEGIN DESCRIPTION:
Cross Section XS236
Ineffective at Sta 4600 based on topo upstream of side channel
END DESCRIPTION:
XS GIS Cut Line= 2
    2967736.3135   13960927.7478     2964416.457   13959486.4688
#Sta/Elev= 30
  2826.5   237.5  2832.6  237.12  2886.5   233.5  3006.5   234.5  3186.5   232.3
  3506.5     232  3806.5   228.1  3886.5   228.8  4086.5   226.6  4226.5   228.4
  4286.5   227.7  4386.5   223.3  4606.5   227.4  4666.5   225.8  4766.5   219.7
  4950.7  219.49  4987.6  213.38  4990.4  210.08  5005.7  209.31  5022.3  215.72
    5080  216.46  5194.2  217.86  5406.5   220.7  5446.5   223.2  5526.5   224.5
  5626.5   223.8  5786.5   227.4  5904.6  225.65  6207.2  230.45  6445.7   235.1
#Mann= 9 ,-1 , 0
  2826.5     .07       0  2832.6     .09       0  4987.6     .08       0
  5022.3     .09       0    5080     .07       0  5194.2     .15       0
  5904.6     .07       0  6207.2     .07       0  6445.7      .2       0
#XS Ineff= 2 , 0
       0    4600   227.5               0
Permanent Ineff=
       F       F
Bank Sta=4987.6,5022.3
XS Rating Curve= 0
Exp/Cntr=.3,.1

Type RM Length L Ch R = 1 ,305093.2,503.55,511.7,582.52
BEGIN DESCRIPTION:
Cross Section XS235
END DESCRIPTION:
XS GIS Cut Line= 4
      2967744.31   13960655.8669    2966130.1243   13959517.3457
    2965548.7203   13959062.3338    2964378.3494   13959335.7184
#Sta/Elev= 30
  3400.9     234  3473.8  234.75  3660.9   236.4  3900.9     235  4020.9   229.8
  4100.9   228.6  4280.9   228.9  4340.9   226.9  4500.9   228.1  4712.6  224.23
  4820.9   225.1  4860.9   219.3  4920.9   217.3  4926.7  215.48  4961.1  213.63
    5005  208.84  5030.7  214.54  5091.1  216.21  5140.9   221.4  5160.9   218.3
  5240.9   217.9  5616.2   225.9  5676.2   224.4  6004.4  225.44  6214.5     225
  6394.5   226.9  6434.5   225.2  6734.5     225  7039.5  231.07  7316.4   234.2
#Mann= 9 , 1 , 0
  3400.9      .2       0  3400.9     .07       0  3473.8     .09       0
  4712.6     .15       0  4961.1     .08       0  5030.7     .15       0
  6004.4     .07       0  7039.5     .07       0  7316.4      .2       0
Bank Sta=4961.1,5030.7
XS Rating Curve= 0
Exp/Cntr=.3,.1

Type RM Length L Ch R = 1 ,304581.5,931.97,656.6,381.37
BEGIN DESCRIPTION:
Cross Section XS234
END DESCRIPTION:
XS GIS Cut Line= 2
    2968232.0964   13960399.9789    2965643.8133   13958544.7237
#Sta/Elev= 30
  3159.4   233.9  3199.4   235.6  3279.4   235.8  3359.4   234.9  3419.4   233.1
  3662.6  233.46  3679.4   234.8  3719.4   235.4  3779.4   233.5  4094.2  229.79
  4439.4   224.9  4559.4   222.2    4630  222.96  4659.4   221.8  4719.4   221.8
  4852.4  216.87    4940  217.25  4983.8  214.51  4994.2  208.49  5002.6  207.73
  5019.6  209.01  5030.5  214.44  5220.7  215.01  5399.4   223.7  5519.4   224.5
  5619.4   223.4  5919.4   223.9  6139.4   229.7  6259.4   230.9  6343.9   233.4
#Mann= 8 , 1 , 0
  3159.4      .2       0  3159.4     .07       0  3662.6     .09       0
  4094.2     .14       0    4630     .15       0  4983.8     .08       0
  5030.5     .15       0  6343.9      .2       0
Bank Sta=4983.8,5030.5
XS Rating Curve= 0
Exp/Cntr=.3,.1

Type RM Length L Ch R = 1 ,303924.9,382.45,351.4,318.37
BEGIN DESCRIPTION:
Cross Section XS233
Ineffective at Sta 4800 based on topo downstream of the cross section
Ineffective at Sta 5360 based on topo upstream of the cross section
END DESCRIPTION:
XS GIS Cut Line= 3
    2968384.1372   13958637.3544    2966137.8436    13958729.985
    2965713.2863   13958467.5315
#Sta/Elev= 30
  3402.5     233  3442.5     233  3602.5   227.8  3762.5   223.9  4022.5   221.6
  4062.5   222.5  4362.5   220.8  4562.5   221.4  4662.5     223  4702.5   221.7
  4725.4  222.61  4762.5   222.1  4842.5   222.7  4901.2   216.6  4966.4  213.47
  4982.5  207.36  4987.8  206.43  5014.2  206.62  5017.5  207.37  5033.7  214.38
    5127  214.32  5222.5   217.3  5342.5   223.3  5482.5   222.4  5710.7   223.4
  5810.7   226.7  5890.7   230.7  5950.7   232.4  6070.7   230.9  6149.8   232.7
#Mann= 5 ,-1 , 0
  3402.5     .14       0  4725.4     .15       0  4966.4     .08       0
  5033.7     .15       0  6149.8      .2       0
#XS Ineff= 2 , 0
       0    4800     223    5360       0   223.5
Permanent Ineff=
       F       F
Bank Sta=4966.4,5033.7
XS Rating Curve= 0
Exp/Cntr=.3,.1

Type RM Length L Ch R = 1 ,303573.5,551.7,551.7,551.7
BEGIN DESCRIPTION:
Cross Section XS232.5
Ineffective at Sta 4850 based on topo downstream of the cross section
END DESCRIPTION:
XS GIS Cut Line= 5
    2968376.0435   13958509.1415    2967260.8431   13958307.0582
    2967006.2698   13958328.7061    2965895.4499   13958463.8058
     2965708.094   13958429.1103
#Sta/Elev= 30
  3381.2   230.7  3561.2   225.4  3921.2   221.6  4101.2   221.1  4141.2   221.8
  4201.2   220.9  4421.2   220.7  4481.2   222.1  4702.7  223.16  4734.6   222.2
  4870.1   222.9  4890.1   221.5  4901.2  216.51  4966.4  213.38  4982.5  207.27
  4987.8  206.34  5014.2  206.53  5017.5  207.28  5033.7  214.29    5127  214.23
  5170.1     216  5310.1   216.7  5390.1   218.1  5490.1   222.5  5630.1     224
  5810.1   232.8  5870.1   232.7  5949.1   230.6  5989.1   230.5  6079.6   233.2
#Mann= 5 ,-1 , 0
  3381.2     .14       0  4702.7     .15       0  4966.4     .08       0
  5033.7     .15       0  6079.6      .2       0
#XS Ineff= 2 , 0
       0    4850   223.4               0
Permanent Ineff=
       F       F
Bank Sta=4966.4,5033.7
XS Rating Curve= 0
Exp/Cntr=.3,.1

Type RM Length L Ch R = 1 ,303021.8,1436.55,1852.9,2310.96
BEGIN DESCRIPTION:
Cross Section XS232
Ineffective at Sta 4540 based on topo downstream of the cross section
END DESCRIPTION:
XS GIS Cut Line= 3
    2968435.9201   13958426.8113    2966832.9033   13957786.2687
    2965705.5671   13958127.8857
#Sta/Elev= 30
  2976.4   230.2  3076.4   226.5  3156.4   225.2  3616.4   220.9  3676.4   221.9
  3736.4   220.4  4156.4   220.6  4216.4   222.4  4396.4   221.7  4429.7  222.63
  4456.4   221.8  4496.4   222.9  4556.4   222.3  4656.4   214.3  4676.4   213.9
  4742.7   215.7  4822.7   216.3  4862.7   214.5  4978.6  213.16  4990.9  206.85
  5006.8  206.19  5009.1  206.78    5013  212.77  5041.2  210.69  5108.7  214.45
  5322.7   220.9  5562.7     223  5762.7   229.4  5842.7   230.5  5880.6   229.8
#Mann= 5 ,-1 , 0
  2976.4     .14       0  4429.7     .15       0  4978.6     .08       0
    5013     .15       0  5880.6      .2       0
#XS Ineff= 2 , 0
       0    4540     223               0
Permanent Ineff=
       F       F
Bank Sta=4978.6,5013
XS Rating Curve= 0
Exp/Cntr=.3,.1