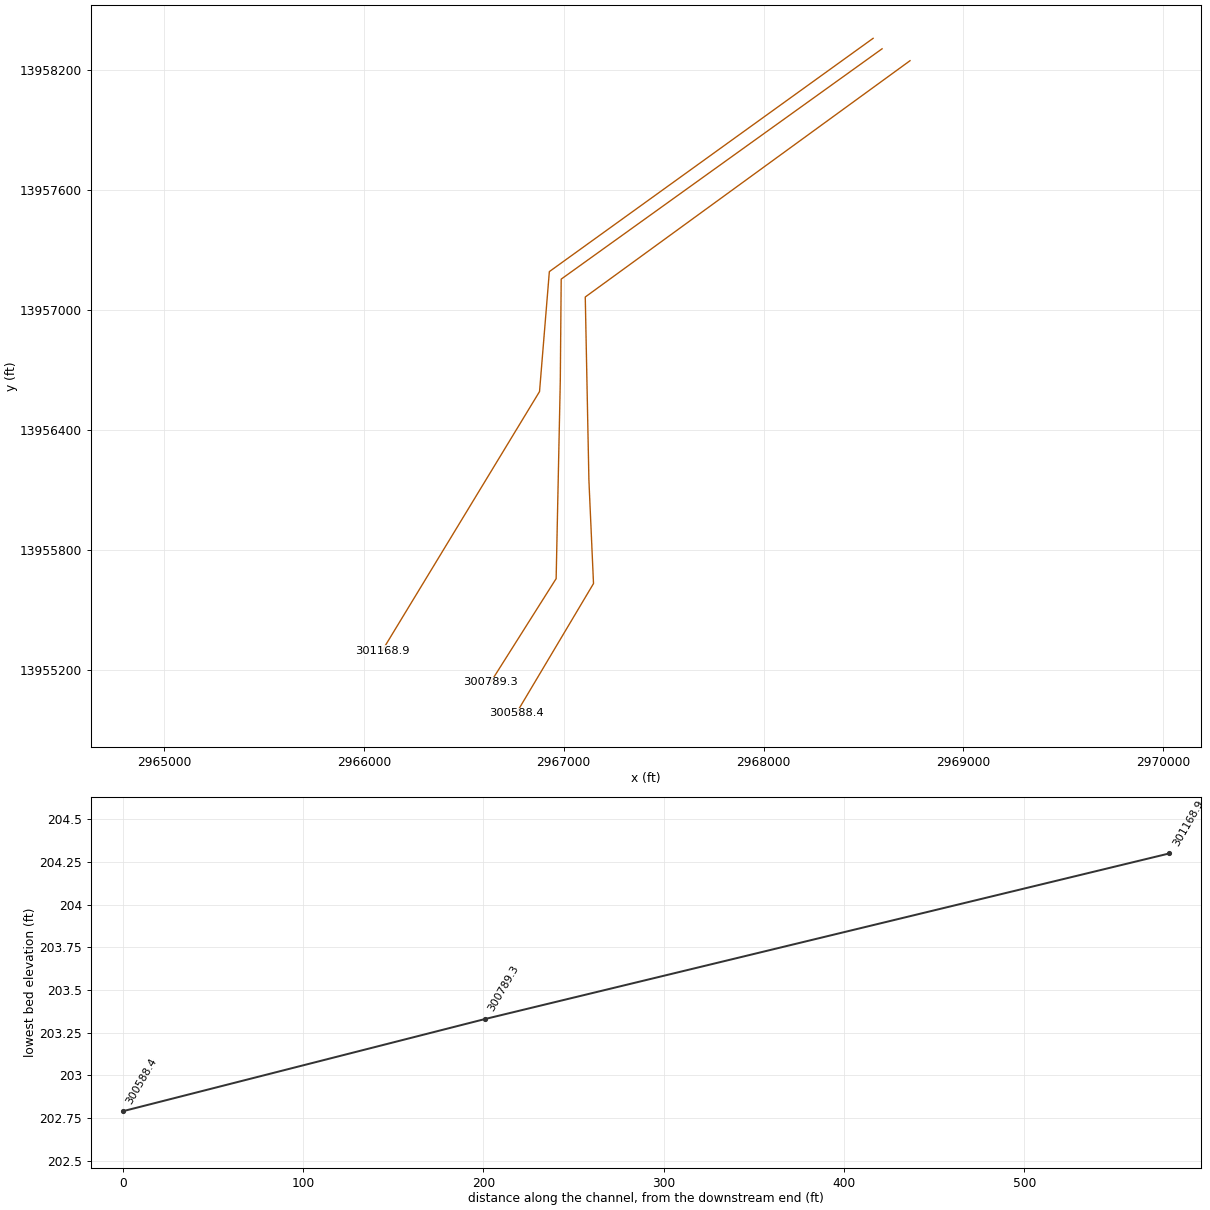
HEC-RAS study J100-00-00.prj: J100-00-00

--- J100-00-00.g01 (geometry) --- (continued)

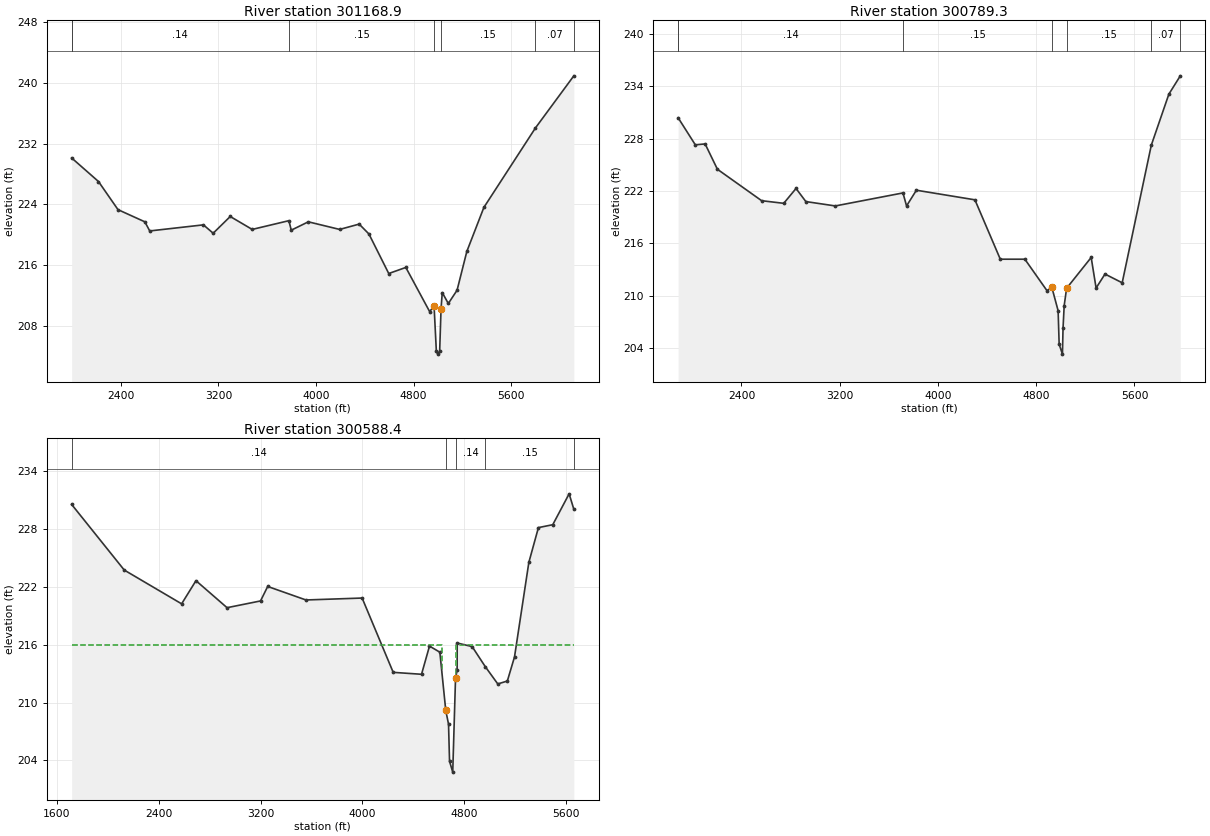
Type RM Length L Ch R = 1 ,301168.9,126.26,379.6,574.58
BEGIN DESCRIPTION:
Cross Section XS231
END DESCRIPTION:
XS GIS Cut Line= 4
    2968548.1886   13958359.4502    2966928.0759   13957192.1402
    2966878.8889   13956591.7605    2966091.5282   13955294.9312
#Sta/Elev= 30
  1996.9   230.1  2216.9     227  2376.9   223.3  2596.9   221.7  2636.9   220.5
  3076.9   221.3  3156.9   220.2  3296.9   222.4  3476.9   220.7  3777.6  221.85
  3796.9   220.6  3936.9   221.7  4193.7   220.7  4353.7   221.4  4433.7   220.1
  4596.1   214.9  4736.1   215.7  4931.1   209.9  4967.7  210.61  4986.4  204.66
    4998   204.3  5013.5  204.69  5024.9   210.3  5034.8  212.39  5084.4  210.96
  5156.1   212.7  5236.1   217.8  5376.1   223.6  5798.8  234.05  6113.3   240.9
#Mann= 7 , 1 , 0
  1996.9      .2       0  1996.9     .14       0  3777.6     .15       0
  4967.7     .08       0  5024.9     .15       0  5798.8     .07       0
  6113.3      .2       0
Bank Sta=4967.7,5024.9
XS Rating Curve= 0
Exp/Cntr=.3,.1

Type RM Length L Ch R = 1 ,300789.3,92.53,200.9,116.22
BEGIN DESCRIPTION:
Cross Section XS230
END DESCRIPTION:
XS GIS Cut Line= 5
     2968593.096   13958307.0582    2966987.3321    13957154.471
    2966982.8426   13956647.9221    2966962.0369   13955655.6586
    2966634.4467   13955137.3816
#Sta/Elev= 30
  1884.3   230.4  2024.3   227.3  2104.3   227.4  2204.3   224.5  2564.3   220.9
  2744.3   220.6  2844.3   222.3  2924.3   220.8  3164.3   220.3    3715  221.79
  3744.3   220.3  3824.3   222.1  4300.9     221  4507.5   214.2  4707.5   214.2
  4887.5   210.6  4927.4  210.97  4978.3   208.3  4986.7  204.46  5013.4  203.33
  5018.4  206.32  5027.5  208.87  5047.4  210.87  5247.5   214.4  5287.5   210.9
  5359.9   212.5  5499.9   211.5    5737  227.26  5879.9   233.1  5973.1   235.2
#Mann= 7 , 1 , 0
  1884.3      .2       0  1884.3     .14       0    3715     .15       0
  4927.4     .08       0  5047.4     .15       0    5737     .07       0
  5973.1      .2       0
Bank Sta=4927.4,5047.4
XS Rating Curve= 0
Exp/Cntr=.5,.3

Type RM Length L Ch R = 1 ,300588.4,50,50,50
BEGIN DESCRIPTION:
Upstream Section of Hegar Road
END DESCRIPTION:
XS GIS Cut Line= 5
     2968732.991   13958247.4725    2967107.7659   13957065.0383
    2967125.9817   13956148.1802    2967149.0205   13955630.9006
    2966762.3672   13954981.3229
#Sta/Elev= 30
1715.409  230.532128.874  223.732579.926  220.232692.689  222.632937.009  219.83
3200.123  220.533256.505  222.033557.206  220.633998.768  220.834243.088  213.13
4465.795  212.934528.379  215.854609.756  215.224656.271  209.184678.072  207.76
4685.965  203.924711.055  202.794733.138  212.574745.636  213.354746.105  216.17
4863.567   215.8 4966.37  213.735065.131  211.935140.307  212.235196.688  214.73
5309.451  224.535384.627  228.13 5497.39  228.435626.034  231.635663.058  230.03
#Mann= 5 ,-1 , 0
1715.409     .14       04656.271     .08       04733.138     .14       0
 4966.37     .15       05663.058      .2       0
#XS Ineff= 2 , 0
       04625.825     2164739.528       0     216
Permanent Ineff=
       F       F
Bank Sta=4656.271,4733.138
XS Rating Curve= 0
Skew Angle= 20
Exp/Cntr=.5,.3