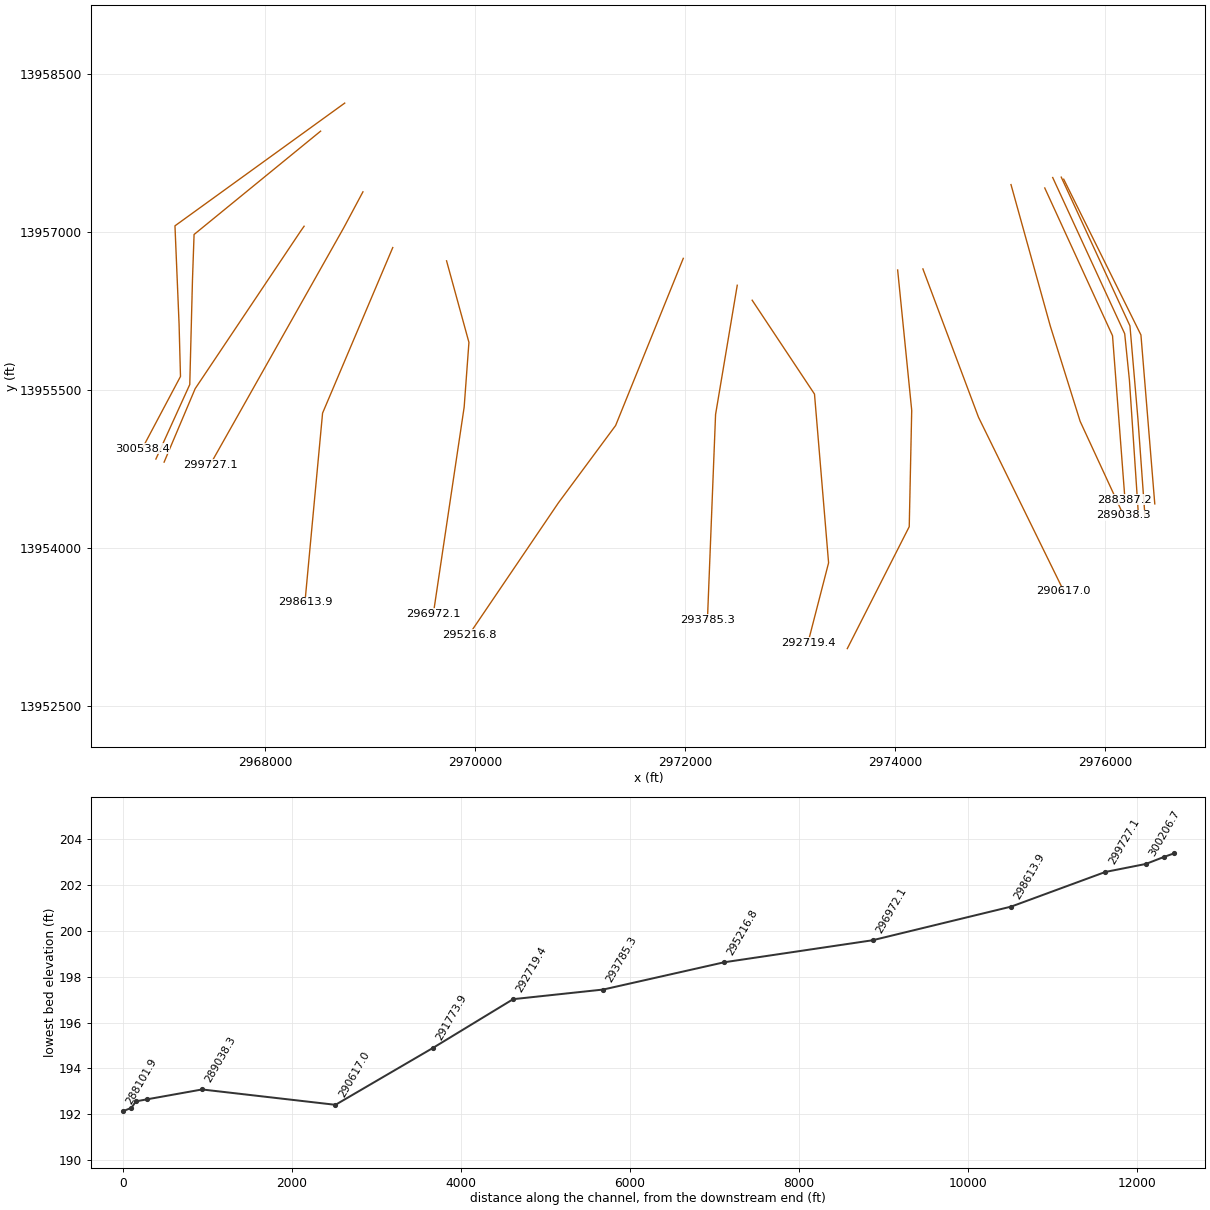
HEC-RAS study J100-00-00.prj: J100-00-00

--- J100-00-00.g01 (geometry) --- (continued)

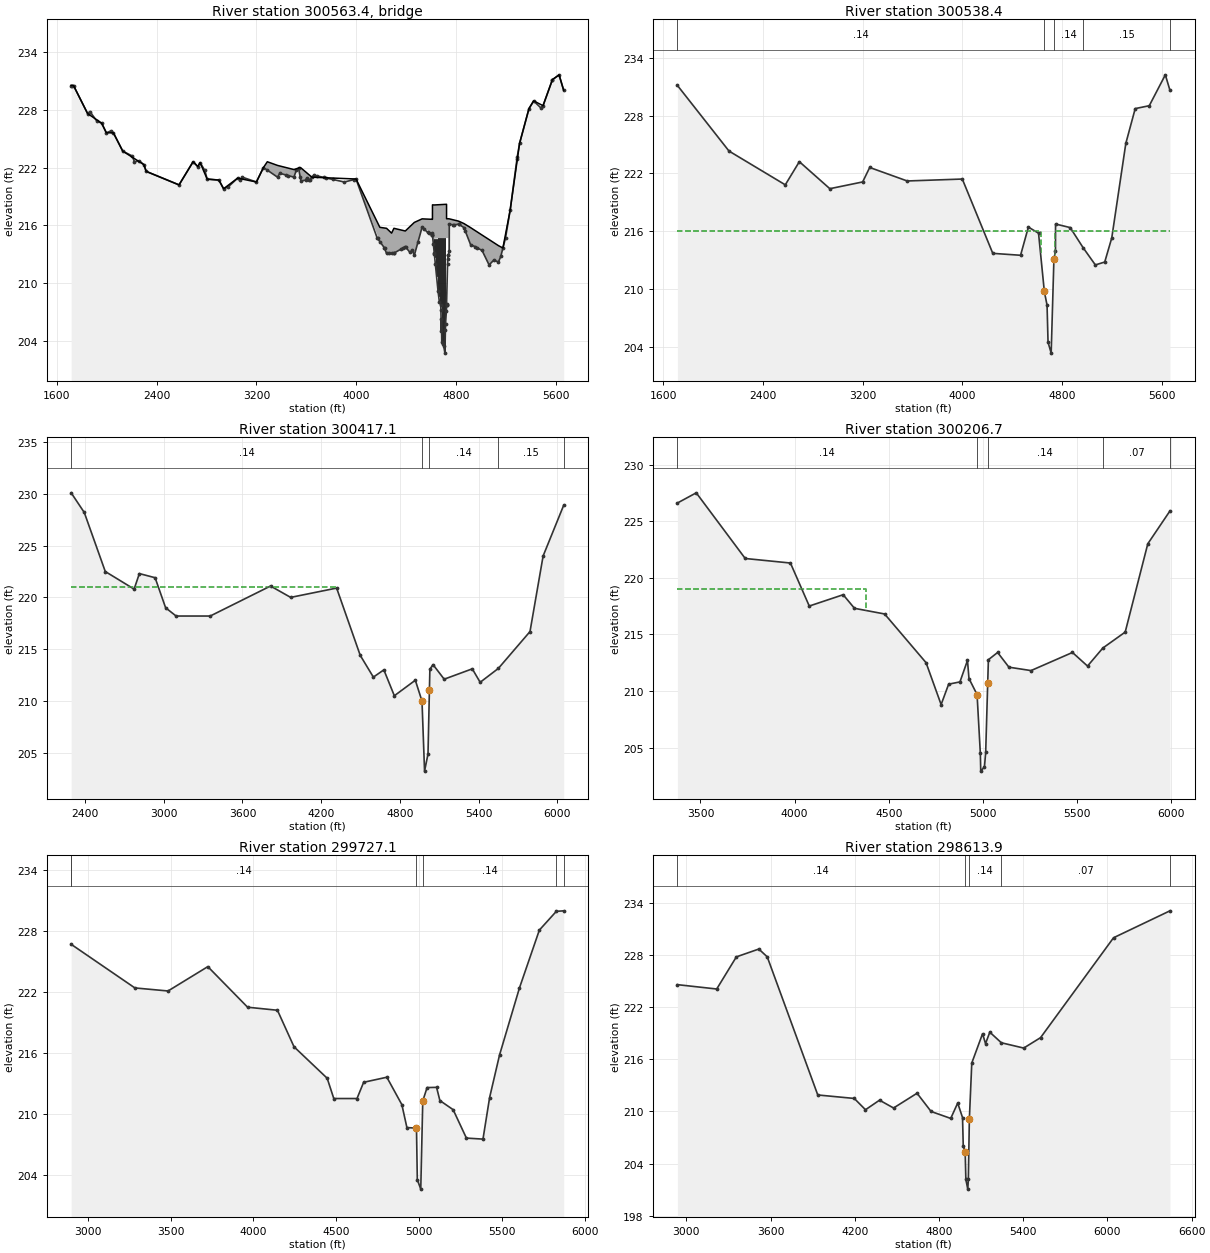
Type RM Length L Ch R = 3 ,300563.4,,,
BEGIN DESCRIPTION:
HEGAR ROAD
Structure ID: J100-00-00-15
Elongated pier with semi-circular ends
END DESCRIPTION:
Node Name=Hegar Road
Bridge Culvert--1,0,-1,-1, 0
Deck Dist Width WeirC Skew NumUp NumDn MinLoCord MaxHiCord MaxSubmerge Is_Ogee
10,30,2.6,20, 60, 60, , , .95, 0, 1,1,,
1715.4091734.2031846.9661959.7291997.3172053.6982128.8742298.0182316.8122579.926
2692.6892730.2772749.0712805.4522899.4222937.0093049.7723200.1233256.5053287.515
3369.2683500.8253538.4133550.6293557.2063644.5983998.768 4189.624243.0884283.589
4302.3834393.4394465.7954528.3794609.7564611.156 4611.264625.9284626.0134724.117
 4724.224739.3314739.4344745.6364746.1054821.2814863.5674916.848 5008.755065.131
5140.3075175.8275234.2765309.4515384.6275422.214 5497.395572.5655626.0345663.058
   230.5   230.5   227.6   226.6   225.6   225.6   223.7   222.3   221.6   220.2
   222.6   222.1   222.5   220.8   220.7   219.8   220.9   220.5     222   222.6
  222.22  221.79  221.95     222  221.96     221  220.81   215.8   215.7   215.2
   215.7  215.42  216.31  216.68  216.63  216.63  218.13  218.12  218.12  218.19
  216.69  216.69  216.69  216.68  216.68  216.44  216.19  215.77     215  214.53
   213.9  213.66  217.61  224.51  228.11  228.91  228.41  231.11  231.61     230
   230.5   230.5   227.6   226.6   225.6   225.6   223.7   222.3   221.6   220.2
   222.6   222.1   222.5   220.8   220.7   219.8   220.9   220.5     222  221.73
     221     221   221.9  221.05   220.6  220.99   220.8  214.32   213.1   213.1
  213.12   213.8   212.9  215.82  215.19  215.01  214.99  213.09  214.62  214.69
  214.69  214.69  212.93  213.32  216.14  216.13  215.77     214   213.4   211.9
   212.2  213.65   217.6   224.5   228.1   228.9   228.4   231.1   231.6     230
1715.4091734.2031846.9661959.7291997.3172053.6982128.8742298.0182316.8122579.926
2692.6892730.2772749.0712805.4522899.4222937.0093049.7723200.1233256.5053287.515
3369.2683500.8253538.4133550.6293557.2063644.5983998.768 4189.624243.0884283.589
4302.3834393.4394465.7954528.3794609.7564611.156 4611.264625.9284626.0134724.117
 4724.224739.3314739.4344745.6364746.1054821.2814863.5674916.848 5008.755065.131
5140.3075175.8275234.2765309.4515384.6275422.214 5497.395572.5655626.0345663.058
   230.5   230.5   227.6   226.6   225.6   225.6   223.7   222.3   221.6   220.2
   222.6   222.1   222.5   220.8   220.7   219.8   220.9   220.5     222   222.6
  222.22  221.79  221.95     222  221.96     221  220.81   215.8   215.7   215.2
   215.7  215.42  216.31  216.68  216.63  216.63  218.13  218.12  218.12  218.19
  216.69  216.69  216.69  216.68  216.68  216.44  216.19  215.77     215  214.53
   213.9  213.66  217.61  224.51  228.11  228.91  228.41  231.11  231.61     230
   230.5   230.5   227.6   226.6   225.6   225.6   223.7   222.3   221.6   220.2
   222.6   222.1   222.5   220.8   220.7   219.8   220.9   220.5     222  221.73
     221     221   221.9  221.05   220.6  220.99   220.8  214.32   213.1   213.1
  213.12   213.8   212.9  215.82  215.19  215.01  214.99  213.09  214.62  214.69
  214.69  214.69  212.93  213.32  216.14  216.13  215.77     214   213.4   211.9
   212.2  213.65   217.6   224.5   228.1   228.9   228.4   231.1   231.6     230
Pier Skew= 20
Pier Skew, UpSta & Num, DnSta & Num=  ,4628.644, 2 ,4628.644, 2 , 0 , 0 , 0 ,,
     5.4     5.4
  211.68  215.62
     5.4     5.4
  211.68  215.62
Pier Skew, UpSta & Num, DnSta & Num=  ,4644.149, 2 ,4644.149, 2 , 0 , 0 , 0 ,,
    11.2    11.2
  209.66  215.63
    11.2    11.2
  209.66  215.63
Pier Skew, UpSta & Num, DnSta & Num=  ,4660.406, 2 ,4660.406, 2 , 0 , 0 , 0 ,,
    11.2    11.2
  207.67  215.64
    11.2    11.2
  207.67  215.64
Pier Skew, UpSta & Num, DnSta & Num=  ,4676.475, 2 ,4676.475, 2 , 0 , 0 , 0 ,,
    11.2    11.2
  206.76  215.66
    11.2    11.2
  206.76  215.66
Pier Skew, UpSta & Num, DnSta & Num=  ,4692.073, 2 ,4692.073, 2 , 0 , 0 , 0 ,,
    11.2    11.2
  202.84  215.67
    11.2    11.2
  202.84  215.67
Pier Skew, UpSta & Num, DnSta & Num=  ,4708.236, 2 ,4708.236, 2 , 0 , 0 , 0 ,,
    11.2    11.2
  201.94  215.68
    11.2    11.2
  201.94  215.68
BR Coef= 1 , 1 , 1 ,.9, 0 ,,,.8,0,1.33,0,
WSPro=,,,, 1 ,,,, 0 ,,,, 0 ,,,,-1 ,-1 ,-1 , 0 , 0 , 0 , 0 , 0
BR U #Sta/Elev= 134
1715.409   230.5 1723.02   230.51734.203   230.51846.966   227.6 1865.76   227.8
1922.141   226.81959.729   226.61997.317   225.62034.904   225.82053.698   225.6
2128.874   223.72204.049   223.22222.843   222.62260.431   222.72298.018   222.3
2316.812   221.62579.926   220.22692.689   222.62730.277   222.12749.071   222.5
2786.658   221.72805.452   220.82899.422   220.72937.009   219.82974.597     220
3049.772   220.93068.566   220.7 3087.36     2213200.123   220.53256.505     222
3287.515  221.733369.268     2213388.062   221.43437.865  221.223456.659  221.16
3500.825     2213519.619   221.73538.413   221.93550.629  221.053557.206   220.6
3594.794   220.73604.097   220.93622.891   220.73625.804  220.743644.598  220.99
3660.479   221.23682.186  221.143738.567  220.983757.361  220.923813.742  220.76
3904.799   220.53982.887  220.753998.768   220.84167.913   214.74170.826  214.65
 4189.62  214.324224.294   213.74227.207  213.614243.088   213.14264.795   213.1
4283.589   213.1 4299.47   213.14302.383  213.124358.764  213.544377.558  213.68
4393.439   213.84396.352  213.754431.026   213.2 4449.82   213.44465.795   212.9
4496.429  214.334528.379  215.824540.595  215.674573.296  215.274585.418  215.24
4609.756  215.194611.156  215.01 4611.26  214.994611.363  214.984618.683  214.03
4625.928  213.094626.013  213.084633.906  212.054656.271  209.154666.514  208.08
4678.072  207.734678.824  207.274682.488  205.02 4682.77  206.314685.965  203.89
4698.369  203.794698.839  203.684700.531  203.554711.055  202.764714.532  205.13
4715.753  205.754722.895  207.164724.013  207.754724.117   207.8 4724.22  207.86
 4732.01  211.954733.138  212.544739.331  212.934739.434  212.934745.636  213.32
4746.105  216.144777.773  216.054780.216  216.044821.281  216.134823.724  216.11
4863.567  215.774872.776  215.464916.848     2144952.368   213.8 4966.37   213.7
 5008.75   213.45065.131   211.95102.719   212.45140.307   212.25159.101   212.8
5175.827  213.655196.688   214.75234.276   217.6 5288.59   222.95290.658   223.1
5309.451   224.55384.627   228.15422.214   228.95478.596   228.2 5497.39   228.4
5570.498  231.035572.565   231.15626.034   231.65663.058     230
BR U #Mann= 5
1715.409     .14 1723.02     .144656.271    .0754733.138     .14 4966.37     .15
BR U Banks=4656.271,4733.138
BR D #Sta/Elev= 134
1715.409   230.5 1723.02   230.51734.203   230.51846.966   227.6 1865.76   227.8
1922.141   226.81959.729   226.61997.317   225.62034.904   225.82053.698   225.6
2128.874   223.72204.049   223.22222.843   222.62260.431   222.72298.018   222.3
2316.812   221.62579.926   220.22692.689   222.62730.277   222.12749.071   222.5
2786.658   221.72805.452   220.82899.422   220.72937.009   219.82974.597     220
3049.772   220.93068.566   220.7 3087.36     2213200.123   220.53256.505     222
3287.515  221.733369.268     2213388.062   221.43437.865  221.223456.659  221.16
3500.825     2213519.619   221.73538.413   221.93550.629  221.053557.206   220.6
3594.794   220.73604.097   220.93622.891   220.73625.804  220.743644.598  220.99
3660.479   221.23682.186  221.143738.567  220.983757.361  220.923813.742  220.76
3904.799   220.53982.887  220.753998.768   220.84167.913   214.74170.826  214.65
 4189.62  214.324224.294   213.74227.207  213.614243.088   213.14264.795   213.1
4283.589   213.1 4299.47   213.14302.383  213.124358.764  213.544377.558  213.68
4393.439   213.84396.352  213.754431.026   213.2 4449.82   213.44465.795   212.9
4496.429  214.334528.379  215.824540.595  215.674573.296  215.274585.418  215.24
4609.756  215.194611.156  215.01 4611.26  214.994611.363  214.984618.683  214.03
4625.928  213.094626.013  213.084633.906  212.054656.271  209.154666.514  208.08
4678.072  207.734678.824  207.274682.488  205.02 4682.77  206.314685.965  203.89
4698.369  203.794698.839  203.684700.531  203.554711.055  202.764714.532  205.13
4715.753  205.754722.895  207.164724.013  207.754724.117   207.8 4724.22  207.86
 4732.01  211.954733.138  212.544739.331  212.934739.434  212.934745.636  213.32
4746.105  216.144777.773  216.054780.216  216.044821.281  216.134823.724  216.11
4863.567  215.774872.776  215.464916.848     2144952.368   213.8 4966.37   213.7
 5008.75   213.45065.131   211.95102.719   212.45140.307   212.25159.101   212.8
5175.827  213.655196.688   214.75234.276   217.6 5288.59   222.95290.658   223.1
5309.451   224.55384.627   228.15422.214   228.95478.596   228.2 5497.39   228.4
5570.498  231.035572.565   231.15626.034   231.65663.058     230
BR D #Mann= 5
1715.409     .14 1723.02     .144656.271    .0754733.138     .14 4966.37     .15
BR D Banks=4656.271,4733.138
BC Design=,, 0 ,, 0 ,,,,,,
BC HTab HWMax=231.63

Type RM Length L Ch R = 1 ,300538.4,121.3,121.3,121.3
BEGIN DESCRIPTION:
Downstream Section of Hegar Road
END DESCRIPTION:
XS GIS Cut Line= 5
    2968755.3114   13958221.3898    2967138.7198   13957056.8035
    2967177.8674   13956124.2186    2967191.3103   13955627.4559
    2966825.2644   13954940.1475
#Sta/Elev= 30
1715.409  231.122128.874  224.322579.926  220.822692.689  223.222937.009  220.42
3200.123  221.123256.505  222.623557.206  221.223998.768  221.424243.088  213.72
4465.795  213.524528.379  216.444609.756  215.814656.271  209.774678.072  208.35
4685.965  204.514711.055  203.384733.138  213.164745.636  213.944746.105  216.76
4863.567  216.39 4966.37  214.325065.131  212.525140.307  212.825196.688  215.32
5309.451  225.125384.627  228.72 5497.39  229.025626.034  232.225663.058  230.62
#Mann= 5 ,-1 , 0
1715.409     .14       04656.271     .08       04733.138     .14       0
 4966.37     .15       05663.058      .2       0
#XS Ineff= 2 , 0
       04625.825     2164739.528       0     216
Permanent Ineff=
       F       F
Bank Sta=4656.271,4733.138
XS Rating Curve= 0
Skew Angle= 20
Exp/Cntr=.5,.3

Type RM Length L Ch R = 1 ,300417.1,575.06,210.4,66.06
BEGIN DESCRIPTION:
Cross Section XS229
Ineffective at Sta 4315 based on topo upstream of the cross section
END DESCRIPTION:
XS GIS Cut Line= 5
    2968525.7349   13957955.2836    2967320.7196   13956974.8054
    2967305.5136   13956544.6674       2967279.7   13955550.8407
    2966957.1475   13954844.0172
#Sta/Elev= 30
  2293.8   230.1  2393.8   228.2  2553.8   222.5  2773.8   220.8  2813.8   222.3
  2933.8   221.9  3013.8     219  3093.8   218.2  3353.8   218.2  3813.8   221.1
  3967.3     220  4317.7   220.9  4497.7   214.4  4597.7   212.3  4677.7     213
  4757.7   210.5  4917.7     212  4968.5  209.98    4988  203.22  5014.2  204.87
    5025  211.01  5028.6  213.06  5052.4  213.51  5137.7   212.1  5351.9   213.1
  5411.9   211.8  5550.6  213.14  5791.9   216.7  5891.9     224  6048.8   228.9
#Mann= 5 ,-1 , 0
  2293.8     .14       0  4968.5     .08       0    5025     .14       0
  5550.6     .15       0  6048.8      .2       0
#XS Ineff= 2 , 0
       0    4315     221               0
Permanent Ineff=
       F       F
Bank Sta=4968.5,5025
XS Rating Curve= 0
Exp/Cntr=.3,.1

Type RM Length L Ch R = 1 ,300206.7,407.41,479.6,468.87
BEGIN DESCRIPTION:
Cross Section XS228
Ineffective at Sta 4380 based on topo upstream of the cross section
END DESCRIPTION:
XS GIS Cut Line= 4
    2968368.6726   13957053.0354    2968336.9612   13957008.3071
    2967331.3273   13955512.1201     2967035.378   13954814.6807
#Sta/Elev= 30
  3377.6   226.6  3477.6   227.5  3737.6   221.7  3977.6   221.3  4077.6   217.5
  4257.6   218.5  4317.6   217.3  4477.6   216.8  4697.6   212.5  4777.6   208.8
  4817.6   210.6  4877.6   210.8  4917.6   212.7  4925.5   211.1  4968.5  209.68
  4985.9  204.48    4988  202.92  5007.7   203.3  5014.2  204.57    5025  210.71
  5028.6  212.76  5077.6   213.4  5137.6   212.1  5254.9   211.8  5474.9   213.4
  5554.9   212.2  5636.1  213.79  5754.9   215.2  5874.9     223  5992.5   225.9
#Mann= 5 ,-1 , 0
  3377.6     .14       0  4968.5     .08       0    5025     .14       0
  5636.1     .07       0  5992.5      .2       0
#XS Ineff= 2 , 0
       0    4380     219               0
Permanent Ineff=
       F       F
Bank Sta=4968.5,5025
XS Rating Curve= 0
Exp/Cntr=.3,.1

Type RM Length L Ch R = 1 ,299727.1,682.48,1113.2,1086.34
BEGIN DESCRIPTION:
Cross Section XS227
END DESCRIPTION:
XS GIS Cut Line= 3
    2968929.0318   13957379.5576    2968747.4762   13957040.7895
    2967473.3026   13954789.3371
#Sta/Elev= 30
  2900.3   226.7  3284.7   222.4  3484.7   222.1  3724.7   224.5  3964.7   220.5
  4144.7   220.2  4244.7   216.6  4444.7   213.5  4484.7   211.5  4624.7   211.5
  4664.7   213.1  4804.7   213.6  4895.2   210.9  4925.7  208.64  4983.5  208.58
  4988.5   203.5  5009.3  202.57  5021.4  211.26  5047.4  212.58  5104.7   212.6
  5124.7   211.3  5204.7   210.4  5284.7   207.6  5384.7   207.5  5424.7   211.6
  5484.7   215.8  5604.7   222.4  5724.7   228.1  5827.2  229.95  5871.6     230
#Mann= 6 , 1 , 0
  2900.3      .2       0  2900.3     .14       0  4983.5     .08       0
  5021.4     .14       0  5827.2     .07       0  5871.6      .2       0
Bank Sta=4983.5,5021.4
XS Rating Curve= 0
Exp/Cntr=.3,.1

Type RM Length L Ch R = 1 ,298613.9,1278.43,1641.8,1357.37
BEGIN DESCRIPTION:
Cross Section XS226
Ineffective at Sta 5160 based on topo downstream of the cross section
END DESCRIPTION:
XS GIS Cut Line= 3
    2969213.0815   13956850.7693    2968544.5703    13955279.797
    2968376.7814   13953485.7462
#Sta/Elev= 30
  2936.1   224.6  3216.1   224.1  3356.1   227.8  3516.1   228.7  3576.1   227.8
  3936.1   211.9  4196.1   211.5  4276.1   210.2  4376.1   211.3  4476.1   210.4
  4643.4   212.1  4743.4     210  4883.4   209.2  4933.1  210.97  4967.5   209.3
  4972.6  206.03  4986.3  205.32  4991.2  202.17  5004.9  201.06  5008.9  202.17
  5016.1   209.1  5033.4  215.58  5110.2  218.95  5131.3  217.81  5161.8  219.13
  5244.1  217.91  5403.4   217.3  5523.4   218.5  6043.4     230  6445.3   233.1
#Mann= 5 ,-1 , 0
  2936.1     .14       0  4986.3     .08       0  5016.1     .14       0
  5244.1     .07       0  6445.3      .2       0
#XS Ineff= 2 , 0
       0                    5160       0     219
Permanent Ineff=
       F       F
Bank Sta=4986.3,5016.1
XS Rating Curve= 0
Exp/Cntr=.3,.1

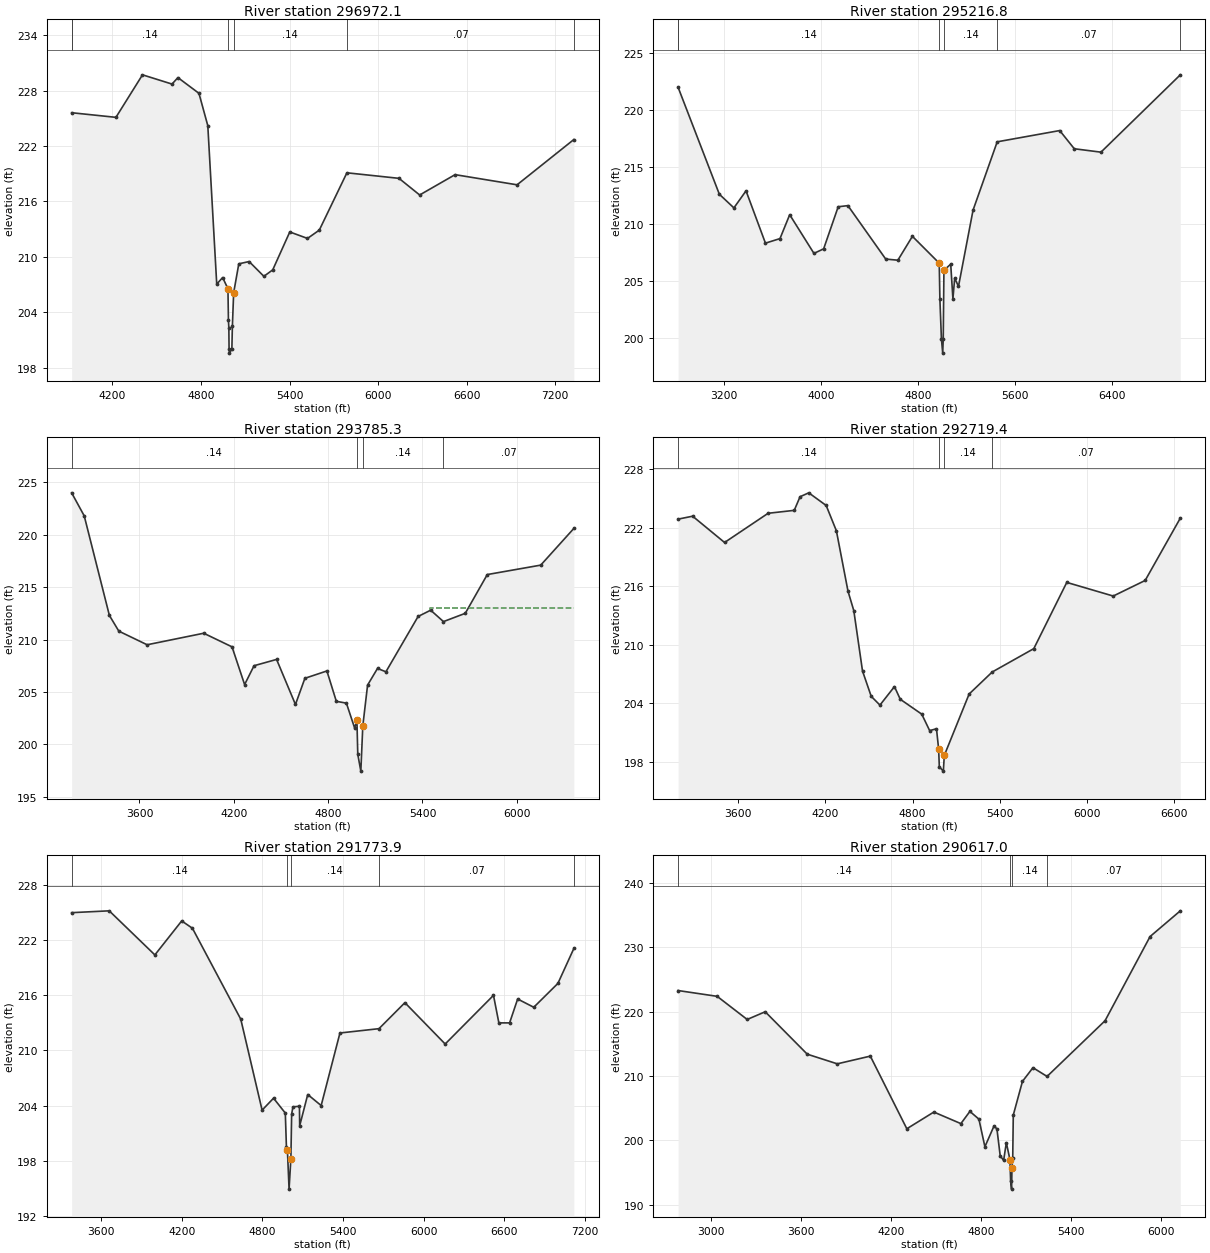
Type RM Length L Ch R = 1 ,296972.1,1687.57,1755.3,1022.67
BEGIN DESCRIPTION:
Cross Section XS225
END DESCRIPTION:
XS GIS Cut Line= 4
    2969725.4714   13956724.6426    2969938.5091   13955950.9527
    2969893.1499   13955337.0906    2969599.3446   13953374.4013
#Sta/Elev= 30
  3923.9   225.6  4223.9   225.1  4403.9   229.7  4603.9   228.7  4643.9   229.4
  4786.4   227.7  4846.4   224.2  4906.9  207.06    4947  207.77  4982.9  206.55
  4986.2  203.17    4989  202.32  4990.5  200.06    4993  199.59  5009.5  200.03
  5012.9  202.48  5021.6  206.12  5056.4  209.25  5126.4   209.5  5226.4   207.9
  5286.4   208.6  5401.9   212.7  5521.9     212  5601.9   212.9  5788.9   219.1
  6141.9   218.5  6281.9   216.7  6521.9   218.9  6941.9   217.8  7326.5   222.7
#Mann= 6 , 1 , 0
  3923.9      .2       0  3923.9     .14       0  4982.9     .08       0
  5021.6     .14       0  5788.9     .07       0  7326.5      .2       0
Bank Sta=4982.9,5021.6
XS Rating Curve= 0
Exp/Cntr=.3,.1

Type RM Length L Ch R = 1 ,295216.8,866.9,1431.5,1635.53
BEGIN DESCRIPTION:
Cross Section XS224
END DESCRIPTION:
XS GIS Cut Line= 4
    2971979.9867   13956748.2913    2971335.7161   13955162.2431
    2970790.3606   13954427.9455    2969938.5091    13953175.982
#Sta/Elev= 30
  2821.4     222  3161.4   212.6  3281.4   211.4  3381.4   212.9  3541.4   208.3
  3661.4   208.7  3741.4   210.8  3941.4   207.4  4021.4   207.8  4141.4   211.5
  4221.4   211.6  4533.3   206.9  4633.3   206.8  4753.3   208.9  4974.5  206.54
  4979.9  203.37  4992.5  199.89  5003.2  198.63  5007.5  199.87  5013.2  205.92
  5069.2  206.45  5087.3   203.4  5101.9  205.22  5133.3   204.5  5253.3   211.2
  5452.5  217.21    5968   218.2    6088   216.6    6308   216.3  6962.3   223.1
#Mann= 6 , 1 , 0
  2821.4      .2       0  2821.4     .14       0  4974.5     .08       0
  5013.2     .14       0  5452.5     .07       0  6962.3      .2       0
Bank Sta=4974.5,5013.2
XS Rating Curve= 0
Exp/Cntr=.3,.1

Type RM Length L Ch R = 1 ,293785.3,1006.87,1065.9,1085.46
BEGIN DESCRIPTION:
Cross Section XS223
Ineffective at Sta 5450 based on topo upstream of the cross section
END DESCRIPTION:
XS GIS Cut Line= 3
    2972494.0636     13956493.04    2972287.5541   13955266.8902
    2972210.1131   13953317.9572
#Sta/Elev= 30
  3168.9     224  3248.9   221.8  3408.9   212.3  3468.9   210.8  3648.9   209.5
  4008.9   210.6  4188.9   209.3  4268.9   205.7  4328.9   207.5  4472.3   208.1
  4592.3   203.8  4652.3   206.3  4792.3     207  4852.3   204.1  4916.3  203.93
  4968.7  201.55  4983.2  202.31  4988.6  199.05  5008.1  197.44  5020.6  201.75
    5051  205.65  5114.1  207.24  5167.6  206.92  5372.3   212.2  5452.3   212.8
  5533.6  211.71  5672.3   212.5  5812.3   216.2  6152.3   217.1  6362.8   220.6
#Mann= 4 ,-1 , 0
  3168.9     .14       0  4983.2     .08       0  5020.6     .14       0
  5533.6     .07       0
#XS Ineff= 2 , 0
       0                    5450       0     213
Permanent Ineff=
       F       F
Bank Sta=4983.2,5020.6
XS Rating Curve= 0
Exp/Cntr=.3,.1

Type RM Length L Ch R = 1 ,292719.4,940.87,945.5,811.66
BEGIN DESCRIPTION:
Cross Section XS222
END DESCRIPTION:
XS GIS Cut Line= 4
    2972636.0388   13956351.0648    2973229.7535   13955460.4928
    2973363.9519    13953859.059    2973167.9392   13953101.8985
#Sta/Elev= 30
  3184.8   222.9  3284.8   223.2  3504.8   220.5  3804.8   223.5  3984.8   223.8
  4024.8   225.2  4084.8   225.6  4204.8   224.3  4275.1   221.7  4355.1   215.5
  4395.1   213.5  4455.1   207.3  4515.1   204.7  4575.1   203.8  4675.1   205.7
  4715.1   204.4  4863.2  202.87  4917.6  201.18  4964.7  201.37  4979.6  199.27
  4984.2  197.46    5012  197.02  5018.4  198.63  5189.6  204.94  5348.6   207.2
  5635.1   209.6  5862.2   216.4  6182.2     215  6402.2   216.6  6644.3     223
#Mann= 4 ,-1 , 0
  3184.8     .14       0  4979.6     .08       0  5018.4     .14       0
  5348.6     .07       0
Bank Sta=4979.6,5018.4
XS Rating Curve= 0
Exp/Cntr=.3,.1

Type RM Length L Ch R = 1 ,291773.9,580.43,1156.9,1054.89
BEGIN DESCRIPTION:
Cross Section XS221
Ineffective at Sta 5500 based on topo upstream of the cross section
END DESCRIPTION:
XS GIS Cut Line= 4
    2974021.6631   13956637.9304    2974155.6728   13955305.7168
     2974132.024    13954202.108    2973542.1786   13953045.1546
#Sta/Elev= 30
  3378.5     225  3658.5   225.2  3998.5   220.4  4198.5   224.1  4278.5   223.3
  4638.5   213.4  4797.4   203.5  4882.7   204.8  4970.3  203.18  4978.7  199.45
  4986.1  199.15  4998.3   194.9  5011.9  198.23  5017.5  203.08  5027.3  203.86
  5075.6  203.92  5077.4   201.8  5137.4   205.2  5237.4     204  5377.4   211.9
  5668.1  212.37  5861.3   215.2  6161.3   210.7  6521.3     216  6561.3     213
  6641.3     213  6701.3   215.6  6821.3   214.7  7001.3   217.3  7119.9   221.1
#Mann= 5 ,-1 , 0
  3378.5     .14       0  4986.1     .08       0  5011.9     .14       0
  5668.1     .07       0  7119.9      .2       0
#XS Ineff= 2 , 0
       0                    5500       0     212
Permanent Ineff=
       F       F
Bank Sta=4986.1,5011.9
XS Rating Curve= 0
Exp/Cntr=.3,.1

Type RM Length L Ch R = 1 ,290617.0,1186.28,1578.7,1040.49
BEGIN DESCRIPTION:
Cross Section XS220
Ineffective at Sta 5150 based on topo downstream of the cross section
END DESCRIPTION:
XS GIS Cut Line= 3
    2974262.3008   13956647.9221    2974791.4812   13955241.0765
    2975604.6122   13953589.0009
#Sta/Elev= 30
  2782.8   223.3  3042.8   222.4  3242.8   218.8  3362.8     220  3642.8   213.4
  3842.8   211.9  4062.8   213.1  4305.9   201.8  4485.9   204.4  4665.9   202.6
  4725.9   204.5  4785.9   203.3  4825.9     199  4885.9   202.2  4905.9   201.8
  4927.8  197.59  4950.6  196.88  4968.6  199.63  4992.7     197  4997.2  193.66
  5003.5  192.41  5006.1  195.67  5011.2   197.3  5014.9  203.93    5076  209.17
  5145.9   211.3  5239.9  209.94  5625.9   218.6  5925.9   231.7  6127.2   235.7
#Mann= 4 ,-1 , 0
  2782.8     .14       0  4992.7     .08       0  5006.1     .14       0
  5239.9     .07       0
#XS Ineff= 2 , 0
       0                    5150       0     211
Permanent Ineff=
       F       F
Bank Sta=4992.7,5006.1
XS Rating Curve= 0
Exp/Cntr=.3,.1

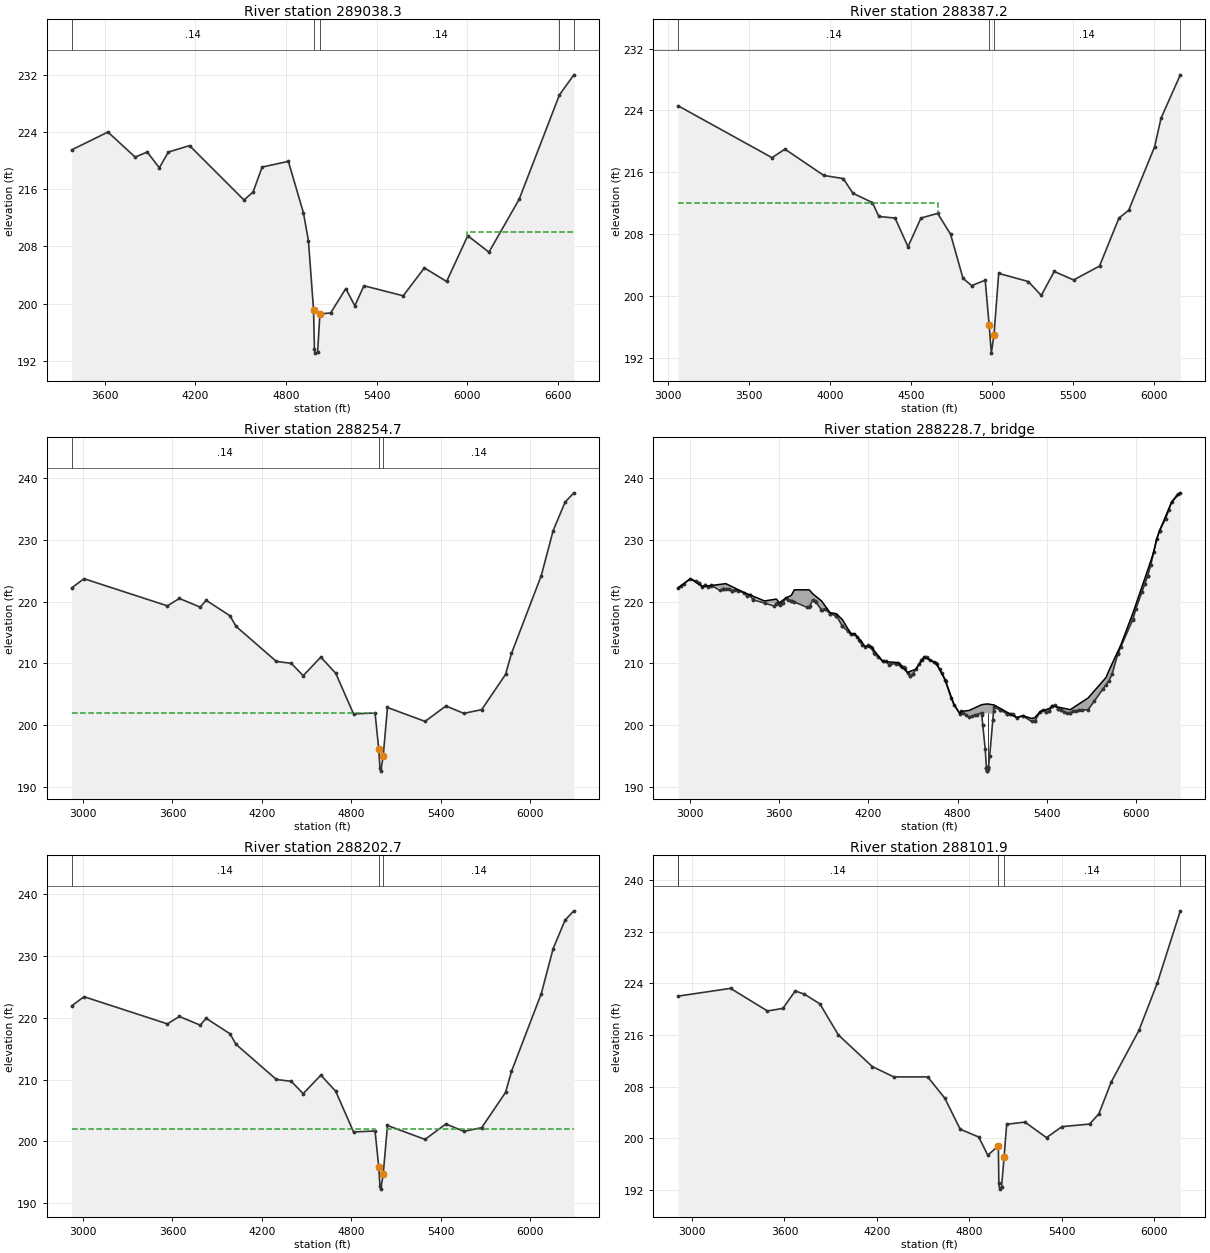
Type RM Length L Ch R = 1 ,289038.3,660.21,651.1,433.27
BEGIN DESCRIPTION:
Cross Section XS219
Ineffective at Sta 6000 based on topo upstream of the cross section
END DESCRIPTION:
XS GIS Cut Line= 4
    2975101.2454   13957448.1462    2975475.5438   13956105.8348
    2975759.4943    13955202.356    2976172.5132    13954311.784
#Sta/Elev= 30
  3382.3   221.5  3622.3     224  3802.3   220.5  3882.3   221.2  3962.3     219
  4022.3   221.2  4162.3   222.1  4522.3   214.5  4582.3   215.6  4642.3   219.1
  4815.8   219.9  4915.8   212.7  4948.8   208.8  4982.6  199.15  4988.5  193.66
  4991.5  193.08  5009.4   193.2  5024.7  198.56  5095.8   198.7  5195.8   202.1
  5255.8   199.7  5315.8   202.5  5575.8   201.1  5715.8     205  5862.9   203.1
  6002.9   209.5  6142.9   207.2  6342.9   214.6  6609.1  229.18  6704.6     232
#Mann= 5 ,-1 , 0
  3382.3     .14       0  4982.6     .08       0  5024.7     .14       0
  6609.1     .07       0  6704.6      .2       0
#XS Ineff= 2 , 0
       0                    6000       0     210
Permanent Ineff=
       F       F
Bank Sta=4982.6,5024.7
XS Rating Curve= 0
Exp/Cntr=.3,.1

Type RM Length L Ch R = 1 ,288387.2,63.68,132.5,81.74
BEGIN DESCRIPTION:
Cross Section XS218.6
Ineffective at Sta 4670 based on topo upstream of the cross section
END DESCRIPTION:
XS GIS Cut Line= 4
    2975422.8433   13957416.0007    2976068.1802   13956014.3012
     2976186.145   13954466.8804     2976186.145   13954459.9413
#Sta/Elev= 30
  3063.3   224.6  3643.3   217.9  3723.3     219  3963.3   215.6  4083.3   215.2
  4143.3   213.3  4263.3   212.1  4303.3   210.3  4403.3   210.1  4483.3   206.4
  4563.3   210.1  4666.4   210.7  4746.4     208    4823  202.31  4876.5  201.37
  4960.1  202.07  4984.7  196.26  4997.9  192.65  5014.5  195.02  5043.4  202.95
  5226.4   201.9  5306.4   200.1  5386.4   203.2  5506.4   202.1  5666.4   203.9
  5786.4   210.1  5846.4   211.1  6006.4   219.3  6046.4     223  6165.3   228.6
#Mann= 4 ,-1 , 0
  3063.3     .14       0  4984.7     .08       0  5014.5     .14       0
  6165.3      .2       0
#XS Ineff= 2 , 0
       0    4670     212               0
Permanent Ineff=
       F       F
Bank Sta=4984.7,5014.5
XS Rating Curve= 0
Exp/Cntr=.5,.3

Type RM Length L Ch R = 1 ,288254.7,52,52,52
BEGIN DESCRIPTION:
Upstream Section of Nichols Murrell Road
END DESCRIPTION:
XS GIS Cut Line= 4
    2975498.4164   13957515.0562    2976184.1904    13956032.898
    2976229.3557   13955589.4571    2976315.7727   13954299.7854
#Sta/Elev= 30
  2923.4  222.21  3006.3  223.71  3566.3  219.31  3646.3  220.51  3786.3  219.11
  3826.3  220.21  3986.3  217.71  4026.3  216.01  4297.8  210.31  4397.8  210.01
  4477.8  208.01  4595.9  211.01  4695.9  208.41  4815.9  201.81  4960.1  201.98
  4984.7  196.17  4993.2  193.03  4997.9  192.56  5014.5  194.93  5043.4  202.86
  5295.9  200.61  5435.9  203.11  5555.7  201.91  5675.9  202.51  5835.9  208.21
  5875.9  211.61  6075.9  224.21  6155.7   231.5  6235.9  236.11  6294.5  237.61
#Mann= 3 ,-1 , 0
  2923.4     .14       0  4984.7     .08       0  5014.5     .14       0
#XS Ineff= 2 , 0
       0    4960     202    5041       0     202
Permanent Ineff=
       F       F
Bank Sta=4984.7,5014.5
XS Rating Curve= 0
Exp/Cntr=.5,.3

Type RM Length L Ch R = 3 ,288228.7,,,
BEGIN DESCRIPTION:
NICHOLS MURRELL ROAD
Structure ID: J100-00-00-14
Square nose piers
END DESCRIPTION:
Node Name=Nichols Murrell
Bridge Culvert--1,0,-1,-1, 0
Deck Dist Width WeirC Skew NumUp NumDn MinLoCord MaxHiCord MaxSubmerge Is_Ogee
10,32,2.6,0, 60, 60, , , .95, 0, 1,1,,
  2923.4  3006.3  3086.3  3243.4  3366.3  3503.4  3583.4  3603.4  3646.3  3683.4
  3703.4  3803.4  3826.3  3886.3  3943.4  3986.3  4026.3  4083.4  4106.3  4157.8
  4177.8  4217.8  4297.8  4397.8  4463.4  4477.8  4518.8  4575.9  4655.9  4715.9
  4775.9  4815.9    4823  4876.5  4960.1 4968.41  4968.5  4997.9 5035.89    5036
  5043.4  5195.9  5235.9  5295.9  5315.9  5355.9  5415.9  5435.9  5555.9  5675.9
  5795.7  5815.9  5895.7  5975.9  6075.9  6115.7  6135.9  6155.7  6235.9  6294.5
   222.2  223.71  222.41   222.9  221.46   220.1   220.4   219.8  220.57     221
   221.9   221.9  221.27   220.1   218.2  218.03  217.06  214.77  214.81   213.4
  212.71  212.71  210.31  210.12  208.51  208.68  209.04  211.01  210.01  207.31
  203.31  201.81  202.22  202.37  203.29  203.33  203.33  203.43   203.3   203.3
  203.27  201.21  201.51  201.09  201.19  202.21  202.69  203.11   202.5   204.4
   207.7  208.84     213  218.11  225.11  227.99  230.11   231.5   236.1   237.6
   222.2   223.7   222.4  222.06   221.4  219.75  219.64  219.53   220.5  220.13
  219.93  219.19   220.2   218.6  218.06   217.7     216  214.76   214.8     213
   212.7   212.7   210.3     210   208.5     208  209.03     211     210   207.3
   203.3   201.8  202.21  201.27  201.97  200.01  201.83  201.93   201.8  200.82
  202.85   201.2   201.5   200.6   200.6   202.2   202.3   203.1   201.9   202.5
  206.52   207.2  212.69   217.1   224.2  227.98   230.1  231.49   236.1   237.6
  2923.4  3006.3  3086.3  3243.4  3366.3  3503.4  3583.4  3603.4  3646.3  3683.4
  3703.4  3803.4  3826.3  3886.3  3943.4  3986.3  4026.3  4083.4  4106.3  4157.8
  4177.8  4217.8  4297.8  4397.8  4463.4  4477.8  4518.8  4575.9  4655.9  4715.9
  4775.9  4815.9    4823  4876.5  4960.1 4968.41  4968.5  4997.9 5035.89    5036
  5043.4  5195.9  5235.9  5295.9  5315.9  5355.9  5415.9  5435.9  5555.9  5675.9
  5795.7  5815.9  5895.7  5975.9  6075.9  6115.7  6135.9  6155.7  6235.9  6294.5
   222.2  223.71  222.41   222.9  221.46   220.1   220.4   219.8  220.57     221
   221.9   221.9  221.27   220.1   218.2  218.03  217.06  214.77  214.81   213.4
  212.71  212.71  210.31  210.12  208.51  208.68  209.04  211.01  210.01  207.31
  203.31  201.81  202.22  202.37  203.29  203.33  203.33  203.43   203.3   203.3
  203.27  201.21  201.51  201.09  201.19  202.21  202.69  203.11   202.5   204.4
   207.7  208.84     213  218.11  225.11  227.99  230.11   231.5   236.1   237.6
  221.95  223.45  222.15  221.81  221.15   219.5  219.39  219.28  220.25  219.88
  219.68  218.94  219.95  218.35  217.81  217.45  215.75  214.51  214.55  212.75
  212.45  212.45  210.05  209.75  208.25  207.75  208.78  210.75  209.75  207.05
  203.05  201.55  201.96  201.02  201.72  199.76  201.58  201.68  201.55  200.57
   202.6  200.95  201.25  200.35  200.35  201.95  202.05  202.85  201.65  202.25
  206.27  206.95  212.44  216.85  223.95  227.73  229.85  231.24  235.85  237.35
Pier Skew, UpSta & Num, DnSta & Num=  ,5003.2, 2 ,5003.2, 2 , 0 , 0 , 0 ,,
     1.1     1.1
   191.9  202.91
     1.1     1.1
  191.65  202.66
Abutment Skew #Up #Dn= , 2 , 2
  4968.3  4993.3
  201.83  193.01
  4968.3  4993.3
  201.58  192.76
Abutment Skew #Up #Dn= , 2 , 2
  5006.6 5036.09
   193.2   201.8
  5006.6 5036.09
  192.95  201.55
BR Coef= 1 , 1 , 1 ,1.25, 0 ,,,.8,0,2,0,
WSPro=,,,, 1 ,,,, 0 ,,,, 0 ,,,,-1 ,-1 ,-1 , 0 , 0 , 0 , 0 , 0
BR U #Sta/Elev= 193
  2923.4   222.2  2943.4  222.56  2963.4  222.92  3006.3   223.7  3043.4  223.27
  3063.4  223.03  3066.3     223  3086.3   222.4  3103.4  222.66  3106.3   222.7
  3126.3   222.4  3143.4  222.57  3146.3   222.6  3206.3   221.8  3223.4  222.06
  3226.3   222.1  3243.4  222.06  3266.3     222  3283.4  221.74  3286.3   221.7
  3306.3   221.9  3323.4  221.76  3366.3   221.4  3386.3   220.9  3403.4  220.99
  3406.3     221  3423.4   220.4  3426.3   220.3  3503.4  219.75  3566.3   219.3
  3583.4  219.64  3586.3   219.7  3603.4  219.53  3606.3   219.5  3623.4  219.76
  3626.3   219.8  3646.3   220.5  3663.4  220.33  3683.4  220.13  3686.3   220.1
  3703.4  219.93  3786.3   219.1  3803.4  219.19  3806.3   219.2  3826.3   220.2
  3843.4  220.03  3846.3     220  3883.4   218.7  3886.3   218.6  3906.3   218.8
  3943.4  218.06  3946.3     218  3983.4  217.72  3986.3   217.7  4023.4  216.12
  4026.3     216  4063.4   215.2  4083.4  214.76  4086.3   214.7  4106.3   214.8
  4126.3   214.3  4137.8   213.8  4143.4  213.58  4157.8     213  4177.8   212.7
  4197.8   212.9  4203.4  212.84  4217.8   212.7  4223.4  212.42  4237.8   211.7
  4243.4  211.57  4263.4   211.1  4297.8   210.3  4303.4   210.3  4317.8   210.3
  4337.8   209.8  4343.4  209.82  4383.4  209.95  4397.8     210  4403.4  209.86
  4417.8   209.5  4423.4  209.47  4437.8   209.4  4443.4   209.2  4463.4   208.5
  4477.8     208  4478.8  208.01  4497.8   208.2  4498.8  208.24  4518.8  209.03
  4538.8  209.82  4555.9   210.5  4558.8  210.57  4575.9     211  4578.8     211
  4595.9     211  4615.9   210.5  4638.8  210.21  4655.9     210  4658.8  209.88
  4678.8  209.08  4695.9   208.4  4715.9   207.3  4718.8  207.09  4755.9   204.4
  4775.9   203.3  4815.9   201.8    4823  202.21  4838.8  201.93  4856.4  201.62
  4876.5  201.27  4893.8  201.41  4918.4  201.61  4928.3   201.7  4960.1  201.97
  4961.7  201.59 4968.41  200.01  4968.5  199.99  4984.7  196.16  4993.2  193.02
  4993.3  193.01  4997.1  192.63  4997.9  192.55  5000.1  192.95    5003  193.11
  5003.2  192.84  5006.5  193.19  5006.6   193.2  5014.5  194.92 5035.89  200.79
    5036  200.82  5041.2  202.25  5043.4  202.85  5084.5   202.5  5087.5  202.46
  5131.2   201.8  5132.1  201.79    5153  201.79  5158.8   201.8  5174.4   201.8
  5195.9   201.2  5235.9   201.5  5238.8  201.46  5295.9   200.6  5315.9   200.6
  5318.8  200.72  5355.9   202.2  5375.9   202.5  5395.7   202.1  5395.9   202.1
  5415.7   202.3  5415.9   202.3  5435.7  203.09  5435.9   203.1  5455.9   203.2
  5475.7  202.61  5475.9   202.6  5495.7   202.5  5495.9   202.5  5515.9   202.1
  5535.7     202  5555.7   201.9  5555.9   201.9  5575.9   202.3  5595.7  202.35
  5615.9   202.4  5635.7  202.43  5675.9   202.5  5715.7  203.84  5775.7  205.85
  5795.7  206.52  5815.9   207.2  5835.9   208.2  5875.7  211.58  5875.9   211.6
  5895.7  212.69  5975.7  217.09  5975.9   217.1  5995.9   218.8  6035.7  221.49
  6055.7  222.84  6075.7  224.19  6075.9   224.2  6095.9   225.9  6115.7  227.98
  6135.9   230.1  6155.7  231.49  6155.9   231.5  6195.9   233.4  6217.2  234.84
  6235.9   236.1  6275.9   237.4  6294.5   237.6
BR U #Mann= 4
  2923.4     .14  4984.7    .075  5014.5     .14  6217.2      .2
BR U Banks=4984.7,5014.5
BR D #Sta/Elev= 193
  2923.4  221.95  2943.4  222.31  2963.4  222.67  3006.3  223.45  3043.4  223.02
  3063.4  222.78  3066.3  222.75  3086.3  222.15  3103.4  222.41  3106.3  222.45
  3126.3  222.15  3143.4  222.32  3146.3  222.35  3206.3  221.55  3223.4  221.81
  3226.3  221.85  3243.4  221.81  3266.3  221.75  3283.4  221.49  3286.3  221.45
  3306.3  221.65  3323.4  221.51  3366.3  221.15  3386.3  220.65  3403.4  220.74
  3406.3  220.75  3423.4  220.15  3426.3  220.05  3503.4   219.5  3566.3  219.05
  3583.4  219.39  3586.3  219.45  3603.4  219.28  3606.3  219.25  3623.4  219.51
  3626.3  219.55  3646.3  220.25  3663.4  220.08  3683.4  219.88  3686.3  219.85
  3703.4  219.68  3786.3  218.85  3803.4  218.94  3806.3  218.95  3826.3  219.95
  3843.4  219.78  3846.3  219.75  3883.4  218.45  3886.3  218.35  3906.3  218.55
  3943.4  217.81  3946.3  217.75  3983.4  217.47  3986.3  217.45  4023.4  215.87
  4026.3  215.75  4063.4  214.95  4083.4  214.51  4086.3  214.45  4106.3  214.55
  4126.3  214.05  4137.8  213.55  4143.4  213.33  4157.8  212.75  4177.8  212.45
  4197.8  212.65  4203.4  212.59  4217.8  212.45  4223.4  212.17  4237.8  211.45
  4243.4  211.32  4263.4  210.85  4297.8  210.05  4303.4  210.05  4317.8  210.05
  4337.8  209.55  4343.4  209.57  4383.4   209.7  4397.8  209.75  4403.4  209.61
  4417.8  209.25  4423.4  209.22  4437.8  209.15  4443.4  208.95  4463.4  208.25
  4477.8  207.75  4478.8  207.76  4497.8  207.95  4498.8  207.99  4518.8  208.78
  4538.8  209.57  4555.9  210.25  4558.8  210.32  4575.9  210.75  4578.8  210.75
  4595.9  210.75  4615.9  210.25  4638.8  209.96  4655.9  209.75  4658.8  209.63
  4678.8  208.83  4695.9  208.15  4715.9  207.05  4718.8  206.84  4755.9  204.15
  4775.9  203.05  4815.9  201.55    4823  201.96  4838.8  201.68  4856.4  201.37
  4876.5  201.02  4893.8  201.16  4918.4  201.36  4928.3  201.45  4960.1  201.72
  4961.7  201.34 4968.41  199.76  4968.5  199.74  4984.7  195.91  4993.2  192.77
  4993.3  192.76  4997.1  192.38  4997.9   192.3  5000.1   192.7    5003  192.86
  5003.2  192.59  5006.5  192.94  5006.6  192.95  5014.5  194.67 5035.89  200.54
    5036  200.57  5041.2     202  5043.4   202.6  5084.5  202.25  5087.5  202.21
  5131.2  201.55  5132.1  201.54    5153  201.54  5158.8  201.55  5174.4  201.55
  5195.9  200.95  5235.9  201.25  5238.8  201.21  5295.9  200.35  5315.9  200.35
  5318.8  200.47  5355.9  201.95  5375.9  202.25  5395.7  201.85  5395.9  201.85
  5415.7  202.05  5415.9  202.05  5435.7  202.84  5435.9  202.85  5455.9  202.95
  5475.7  202.36  5475.9  202.35  5495.7  202.25  5495.9  202.25  5515.9  201.85
  5535.7  201.75  5555.7  201.65  5555.9  201.65  5575.9  202.05  5595.7   202.1
  5615.9  202.15  5635.7  202.18  5675.9  202.25  5715.7  203.59  5775.7   205.6
  5795.7  206.27  5815.9  206.95  5835.9  207.95  5875.7  211.33  5875.9  211.35
  5895.7  212.44  5975.7  216.84  5975.9  216.85  5995.9  218.55  6035.7  221.24
  6055.7  222.59  6075.7  223.94  6075.9  223.95  6095.9  225.65  6115.7  227.73
  6135.9  229.85  6155.7  231.24  6155.9  231.25  6195.9  233.15  6217.2  234.59
  6235.9  235.85  6275.9  237.15  6294.5  237.35
BR D #Mann= 4
  2923.4     .14  4984.7    .075  5014.5     .14  6217.2      .2
BR D Banks=4984.7,5014.5
BC Design=,, 0 ,, 0 ,,,,,,
BC HTab HWMax=237.61

Type RM Length L Ch R = 1 ,288202.7,100.8,100.8,100.8
BEGIN DESCRIPTION:
Downstream Section of Nichols Murrell Road
END DESCRIPTION:
XS GIS Cut Line= 4
    2975579.7743   13957519.0434    2976234.1371    13956107.873
     2976311.012   13955214.2024     2976377.513   13954297.1892
#Sta/Elev= 30
  2923.4  221.93  3006.3  223.43  3566.3  219.03  3646.3  220.23  3786.3  218.83
  3826.3  219.93  3986.3  217.43  4026.3  215.73  4297.8  210.03  4397.8  209.73
  4477.8  207.73  4595.9  210.73  4695.9  208.13  4815.9  201.53  4960.1   201.7
  4984.7  195.89  4993.2  192.75  4997.9  192.28  5014.5  194.65  5043.4  202.58
  5295.9  200.33  5435.9  202.83  5555.7  201.63  5675.9  202.23  5835.9  207.93
  5875.9  211.33  6075.9  223.93  6155.7  231.22  6235.9  235.83  6294.5  237.33
#Mann= 3 ,-1 , 0
  2923.4     .14       0  4984.7     .08       0  5014.5     .14       0
#XS Ineff= 2 , 0
       0    4960     202    5041       0     202
Permanent Ineff=
       F       F
Bank Sta=4984.7,5014.5
XS Rating Curve= 0
Exp/Cntr=.5,.3

Type RM Length L Ch R = 1 ,288101.9,234.91,472.1,589.5
BEGIN DESCRIPTION:
Cross Section XS218.4
END DESCRIPTION:
XS GIS Cut Line= 3
    2975603.2601     13957499.27    2976338.8054   13956021.2403
    2976470.6484   13954418.3067
#Sta/Elev= 30
  2909.6     222  3249.6   223.2  3489.6   219.7  3589.6   220.1  3669.6   222.8
  3729.6   222.3  3829.6   220.8  3949.6     216  4169.6   211.1  4309.6   209.5
  4529.6   209.5  4640.5   206.2  4740.5   201.4  4860.5   200.2  4919.4  197.38
    4988  198.82  4991.3  193.04  4996.2  192.13  5008.5  192.45    5025  197.03
  5041.9  202.17  5160.5   202.5  5300.5   200.1  5400.5   201.8  5580.5   202.2
  5640.5   203.8  5720.5   208.7  5900.5   216.7  6020.5   224.1  6168.9   235.2
#Mann= 5 , 1 , 0
  2909.6      .2       0  2909.6     .14       0    4988     .08       0
    5025     .14       0  6168.9      .2       0
Bank Sta=4988,5025
XS Rating Curve= 0
Exp/Cntr=.3,.1