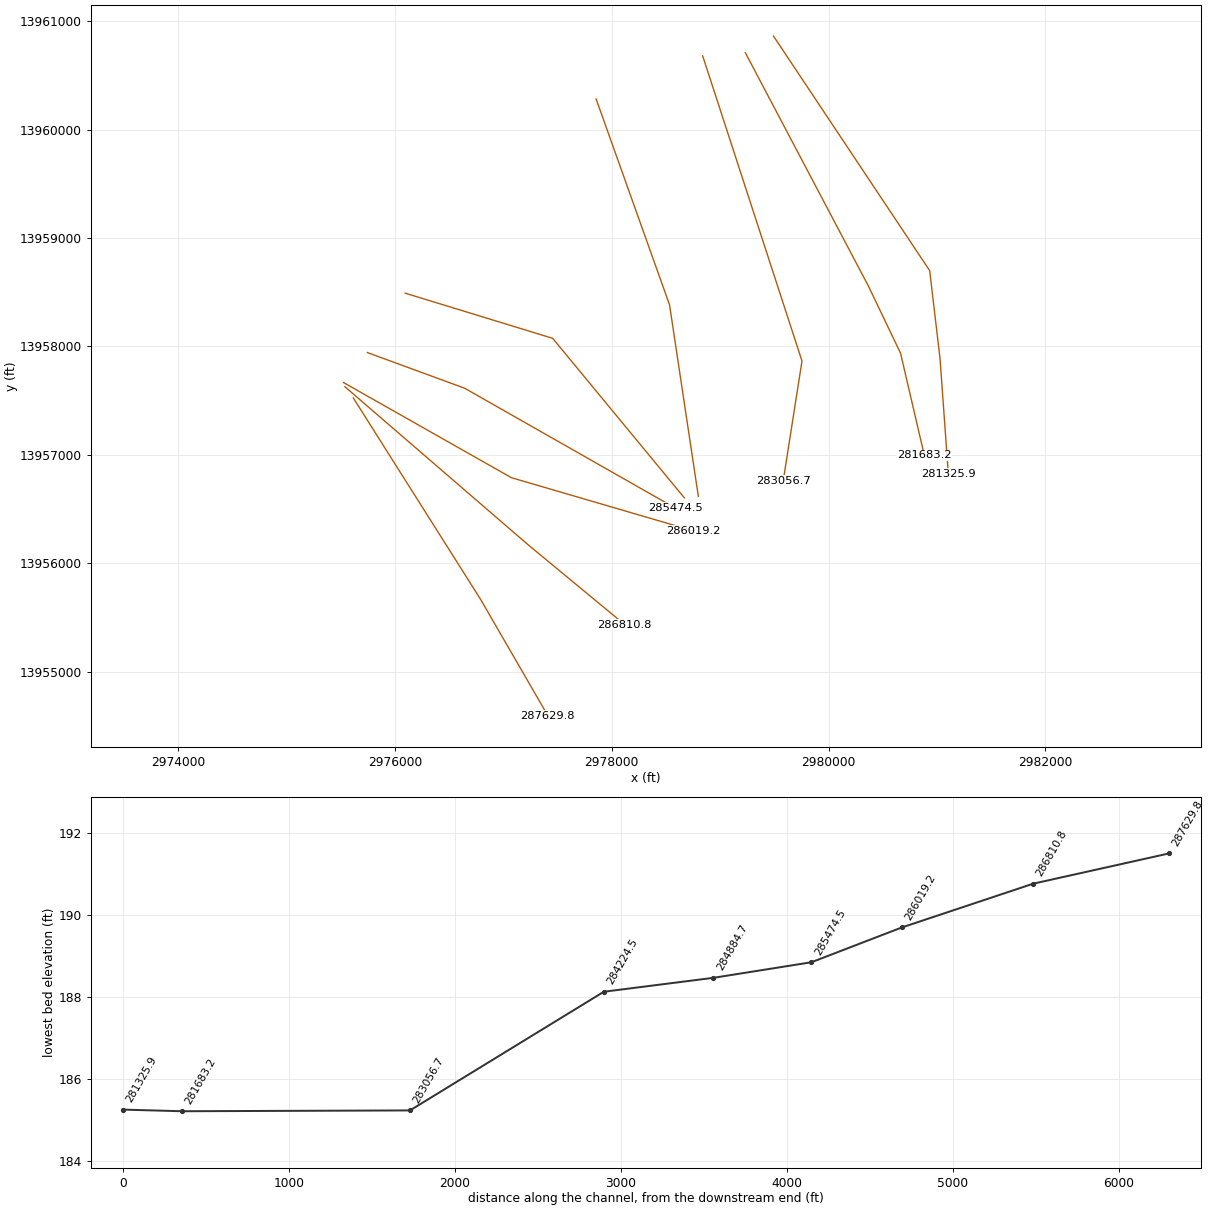
HEC-RAS study J100-00-00.prj: J100-00-00

--- J100-00-00.g01 (geometry) --- (continued)

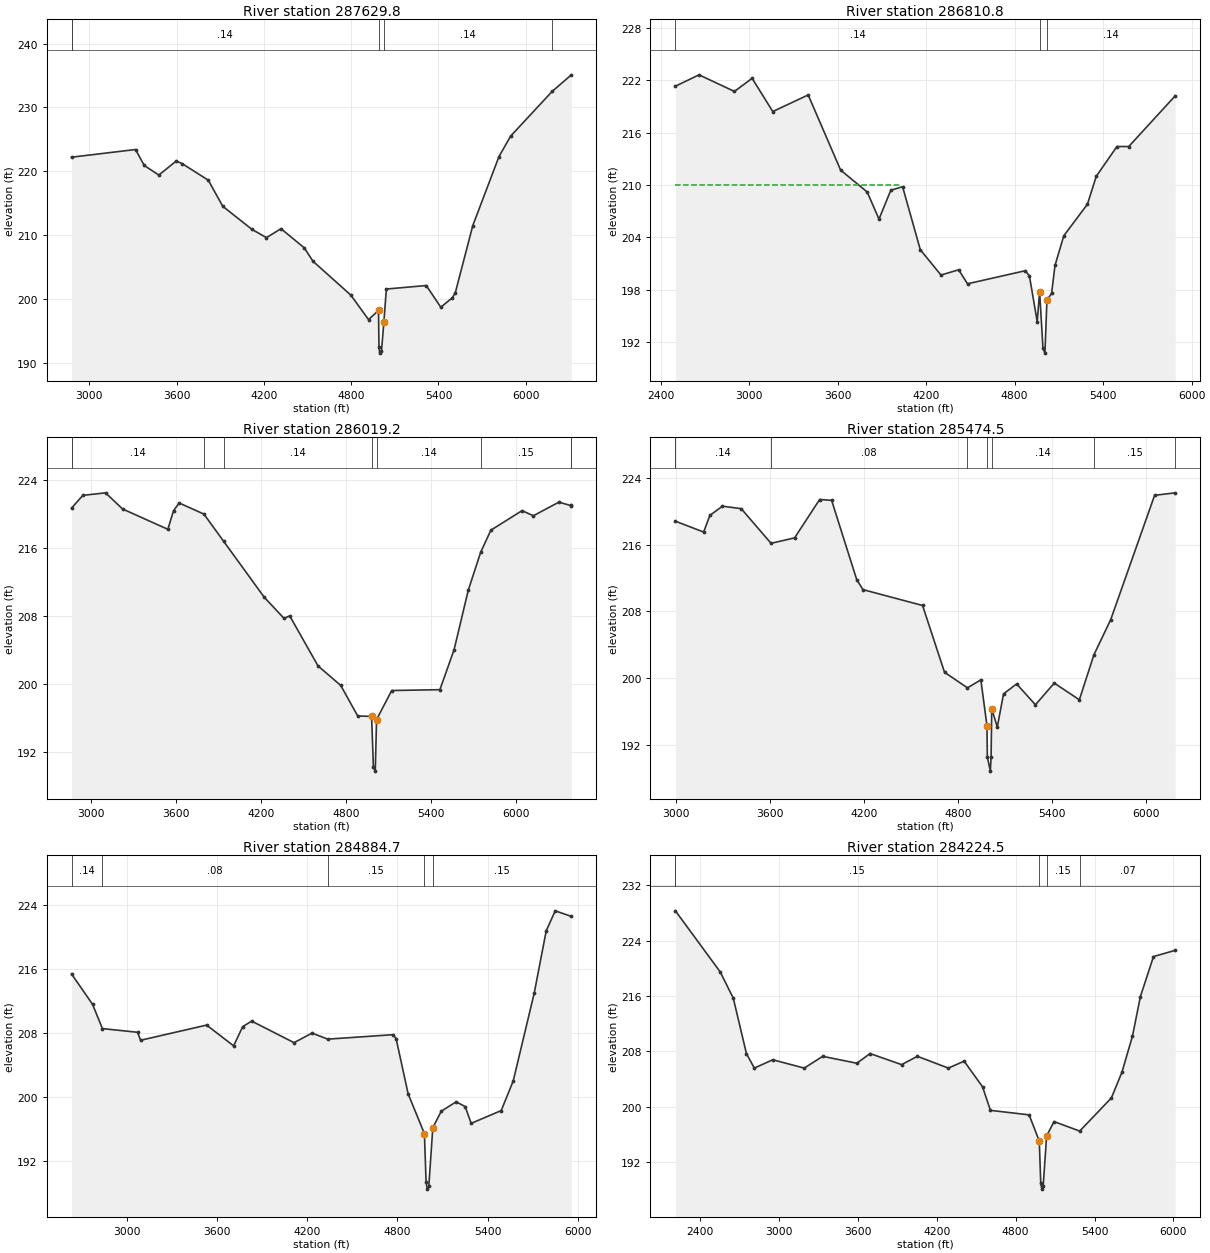
Type RM Length L Ch R = 1 ,287629.8,597.55,819,817.76
BEGIN DESCRIPTION:
Cross Section XS218
END DESCRIPTION:
XS GIS Cut Line= 3
     2975617.519   13957525.5873    2976792.0415   13955667.0022
    2977411.5699   13954595.7345
#Sta/Elev= 30
  2877.7   222.2  3317.7   223.4  3377.7   220.9  3477.7   219.4  3597.7   221.6
  3637.7   221.2  3817.7   218.6  3917.7   214.5  4117.7   210.9  4217.7   209.6
  4317.7     211  4477.7     208  4537.7   205.9  4797.7   200.6  4919.4  196.76
    4988   198.2  4991.3  192.42  4996.2  191.51  5008.5  191.83    5025  196.41
  5041.9  201.55  5316.3   202.1  5416.3   198.7  5496.3   200.2  5516.3     201
  5636.3   211.5  5816.3   222.3  5896.3   225.5    6182  232.51  6313.8   235.1
#Mann= 5 , 1 , 0
  2877.7      .2       0  2877.7     .14       0    4988     .08       0
    5025     .14       0    6182     .07       0
Bank Sta=4988,5025
XS Rating Curve= 0
Exp/Cntr=.3,.1

Type RM Length L Ch R = 1 ,286810.8,479.2,791.6,796.63
BEGIN DESCRIPTION:
Cross Section XS217
END DESCRIPTION:
XS GIS Cut Line= 3
     2975540.078    13957628.842    2977230.8741    13956170.369
    2978121.4461   13955434.6791
#Sta/Elev= 30
  2500.7   221.3  2660.7   222.6  2900.7   220.7  3020.7   222.2  3160.7   218.4
  3400.7   220.3  3620.7   211.7  3800.7   209.2  3880.7   206.1  3960.7   209.4
  4040.7   209.8  4160.7   202.6  4300.7   199.7  4420.7   200.3  4480.7   198.7
  4873.6   200.2  4900.7  199.57  4953.1  194.37  4969.5   197.8  4992.2   191.3
  5005.5  190.77  5019.1  196.85  5050.7   197.6  5073.6   200.8  5133.6   204.2
  5293.6   207.8  5353.6     211  5493.6   214.4  5573.6   214.4  5888.8   220.2
#Mann= 3 ,-1 , 0
  2500.7     .14       0  4969.5     .08       0  5019.1     .14       0
#XS Ineff= 2 , 0
       0    4020     210               0
Permanent Ineff=
       F       F
Bank Sta=4969.5,5019.1
XS Rating Curve= 0
Exp/Cntr=.3,.1

Type RM Length L Ch R = 1 ,286019.2,544.7,544.7,544.7
BEGIN DESCRIPTION:
Cross Section XS216
END DESCRIPTION:
XS GIS Cut Line= 3
    2975527.1711   13957667.5625     2977075.992   13956789.8974
    2978753.8813   13956299.4374
#Sta/Elev= 30
  2861.6   220.7  2941.6   222.2  3101.6   222.5  3221.6   220.6  3541.6   218.2
  3581.6   220.4  3621.6   221.3  3796.3  219.99  3934.4  216.81  4221.6   210.2
  4361.6   207.7  4401.6     208  4601.6   202.1  4761.8   199.8  4881.8   196.2
  4979.7  196.15  4992.6  190.15  5005.6   189.7  5014.8  195.78  5121.8   199.2
  5461.8   199.3  5561.8     204  5661.8     211  5749.7   215.5  5821.8   218.1
  6041.8   220.4  6121.8   219.8  6301.8   221.4  6385.8     221  6389.9   221.1
#Mann= 9 , 1 , 0
  2861.6      .2       0  2861.6     .14       0  3796.3     .08       0
  3934.4     .14       0  4979.7     .08       0  5014.8     .14       0
  5749.7     .15       0  6385.8     .07       0  6389.9      .2       0
Bank Sta=4979.7,5014.8
XS Rating Curve= 0
Exp/Cntr=.3,.1

Type RM Length L Ch R = 1 ,285474.5,717.04,589.8,430.79
BEGIN DESCRIPTION:
Cross Section XS215
END DESCRIPTION:
XS GIS Cut Line= 3
    2975747.1623   13957944.2048    2976645.0451   13957614.7953
    2978584.7915   13956511.2646
#Sta/Elev= 30
  2998.5   218.8  3178.5   217.5  3218.5   219.5  3298.5   220.6  3418.5   220.3
  3608.5  216.15  3758.5   216.8  3918.5   221.4  3994.9   221.3  4154.9   211.8
  4194.9   210.6  4574.9   208.7  4714.9   200.7  4861.2  198.83  4946.7  199.79
  4985.6   194.3  4988.1  190.54  5007.4  188.85    5012  190.57  5016.2  196.31
  5051.6  194.13  5091.4  198.11  5174.9   199.3  5294.9   196.8  5414.9   199.4
  5574.9   197.4    5668   202.8  5774.9     207  6054.9   221.9  6186.6   222.2
#Mann= 8 , 1 , 0
  2998.5      .2       0  2998.5     .14       0  3608.5     .08       0
  4861.2     .14       0  4985.6     .08       0  5016.2     .14       0
    5668     .15       0  6186.6      .2       0
Bank Sta=4985.6,5016.2
XS Rating Curve= 0
Exp/Cntr=.3,.1

Type RM Length L Ch R = 1 ,284884.7,1051.39,660.2,482.46
BEGIN DESCRIPTION:
Cross Section XS214.5
END DESCRIPTION:
XS GIS Cut Line= 3
    2976095.9366   13958491.5623    2977456.0015   13958075.2159
    2978670.3452   13956604.1253
#Sta/Elev= 30
  2628.8   215.4  2768.8   211.6  2834.6  208.56  3068.8   208.1  3088.8   207.1
  3528.8     209  3708.8   206.4  3768.8   208.8  3828.8   209.5  4111.2   206.8
  4231.2     208  4335.6  207.24  4771.2   207.8  4791.2   207.3  4871.2   200.4
  4979.7  195.41  4990.8  189.34  4999.1  188.47  5009.1  188.87  5035.6  196.16
    5092  198.22  5191.2   199.4  5251.2   198.8  5291.2   196.7  5491.2   198.3
  5571.2     202  5711.2     213  5791.2   220.8  5851.2   223.3  5958.7   222.6
#Mann= 5 ,-1 , 0
  2628.8     .14       0  2834.6     .08       0  4335.6     .15       0
  4979.7     .08       0  5035.6     .15       0
Bank Sta=4979.7,5035.6
XS Rating Curve= 0
Exp/Cntr=.3,.1

Type RM Length L Ch R = 1 ,284224.5,1007.22,1167.8,1115.73
BEGIN DESCRIPTION:
Cross Section XS214
END DESCRIPTION:
XS GIS Cut Line= 3
    2977856.9997   13960281.9878    2978534.0337   13958383.6375
    2978799.5373    13956618.039
#Sta/Elev= 30
  2212.7   228.3  2552.7   219.5  2652.7   215.7  2752.7   207.7  2812.7   205.6
  2952.7   206.8  3192.7   205.6  3332.7   207.3  3592.7   206.3  3692.7   207.7
  3932.7   206.1  4052.7   207.3  4288.2   205.6  4408.2   206.6  4548.2   202.9
  4608.2   199.5  4902.5  198.85  4979.7  195.07  4990.8     189  4999.1  188.13
  5009.1  188.53  5035.6  195.82    5092  197.88  5287.1  196.51  5528.2   201.3
  5608.2     205  5688.2   210.2  5748.2   215.9  5848.2   221.7  6013.6   222.6
#Mann= 5 , 1 , 0
  2212.7      .2       0  2212.7     .15       0  4979.7     .08       0
  5035.6     .15       0  5287.1     .07       0
Bank Sta=4979.7,5035.6
XS Rating Curve= 0
Exp/Cntr=.3,.1

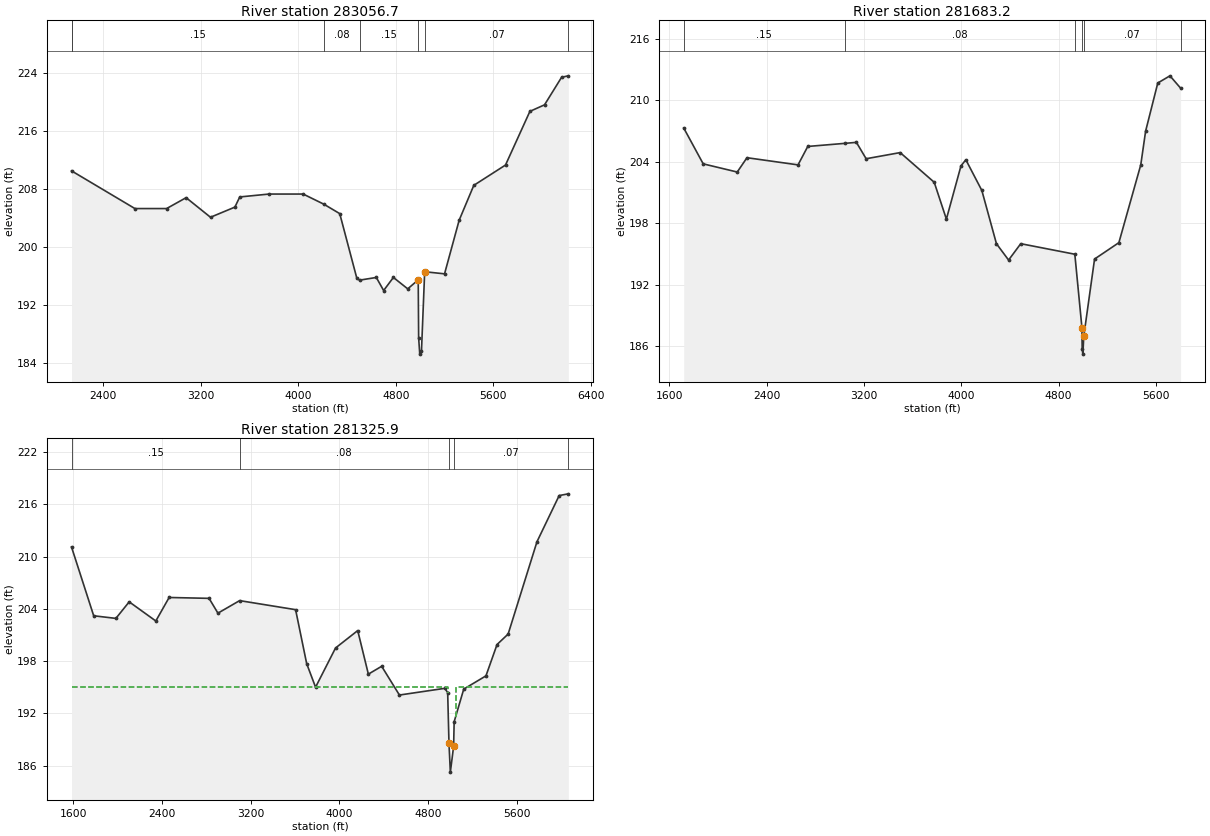
Type RM Length L Ch R = 1 ,283056.7,767.6,1373.5,1077.76
BEGIN DESCRIPTION:
Cross Section XS213
END DESCRIPTION:
XS GIS Cut Line= 3
    2978839.3628   13960680.2431      2979755.35   13957865.9056
    2979582.7727    13956764.066
#Sta/Elev= 30
  2139.5   210.5  2659.5   205.3  2919.5   205.3  3079.5   206.8  3279.5   204.1
  3479.5   205.5  3519.5   206.9  3759.5   207.3  4039.5   207.3  4209.4   205.9
  4339.5   204.6  4479.5   195.7  4502.4  195.43  4639.5   195.8  4699.5     194
  4779.5   195.8  4897.2  194.23  4983.2  195.47  4986.6  187.48  4995.8  185.23
    5010   185.7  5036.1  196.59  5199.1   196.3  5319.1   203.7  5439.1   208.5
  5699.1   211.3  5899.1   218.7  6019.1   219.6  6159.1   223.4  6214.4   223.6
#Mann= 7 , 1 , 0
  2139.5      .2       0  2139.5     .15       0  4209.4     .08       0
  4502.4     .15       0  4983.2     .08       0  5036.1     .07       0
  6214.4      .2       0
Bank Sta=4983.2,5036.1
XS Rating Curve= 0
Exp/Cntr=.3,.1

Type RM Length L Ch R = 1 ,281683.2,466.52,357.3,235.45
BEGIN DESCRIPTION:
Cross Section XS218.5
Ineffective at Sta 4050 based on topo upstream of the cross section
END DESCRIPTION:
XS GIS Cut Line= 4
    2979232.9021   13960708.9888    2980367.2364   13958558.1345
    2980664.0937   13957938.6062      2980883.51   13956996.4068
#Sta/Elev= 30
  1717.5   207.3  1877.5   203.8  2157.5     203  2237.5   204.4  2657.5   203.7
  2737.5   205.5  3040.5   205.8  3137.5   205.9  3217.5   204.3  3497.5   204.9
  3777.5     202  3877.5   198.4  3997.5   203.6  4037.5   204.2  4169.1   201.2
  4289.1     196  4389.1   194.4  4489.1     196  4933.8  194.97  4992.1  187.81
  4994.3  185.71    5000  185.21  5007.3  186.95  5096.1   194.5  5296.1   196.1
  5476.1   203.7  5516.1     207  5616.1   211.7  5716.1   212.4  5803.5   211.2
#Mann= 6 ,-1 , 0
  1717.5     .15       0  3040.5     .08       0  4933.8     .07       0
  4992.1     .08       0  5007.3     .07       0  5803.5      .2       0
#XS Ineff= 2 , 0
       0    4050     202               0
Permanent Ineff=
       F       F
Bank Sta=4992.1,5007.3
XS Rating Curve= 0
Exp/Cntr=.5,.3

Type RM Length L Ch R = 1 ,281325.9,32,32,32
BEGIN DESCRIPTION:
Upstream Section of Wood Bridge DS of Nichols Murrell
END DESCRIPTION:
XS GIS Cut Line= 4
    2979492.5516   13960862.4176    2980932.9911   13958699.2771
    2981028.1969   13957889.3274    2981104.8667   13956827.8453
#Sta/Elev= 30
    1585   211.1    1785   203.2    1985   202.9    2105   204.8    2345   202.6
    2465   205.3    2825   205.2    2905   203.5  3100.5  204.94    3605   203.9
    3705   197.7    3785     195    3965   199.5    4165   201.5  4260.9   196.5
  4380.9   197.4  4540.9   194.1  4950.2  194.87  4975.9  194.38  4987.7  188.55
    5000  185.25  5029.4   188.2  5034.4  191.04  5120.7  194.78  5320.9   196.3
  5420.9   199.9  5520.9   201.1  5780.9   211.7  5980.9     217  6063.6   217.2
#Mann= 5 ,-1 , 0
    1585     .15       0  3100.5     .08       0  4987.7     .08       0
  5029.4     .07       0  6063.6      .2       0
#XS Ineff= 2 , 0
       0  4975.9     195  5046.8       0     195
Permanent Ineff=
       F       F
Bank Sta=4987.7,5029.4
XS Rating Curve= 0
Exp/Cntr=.5,.3