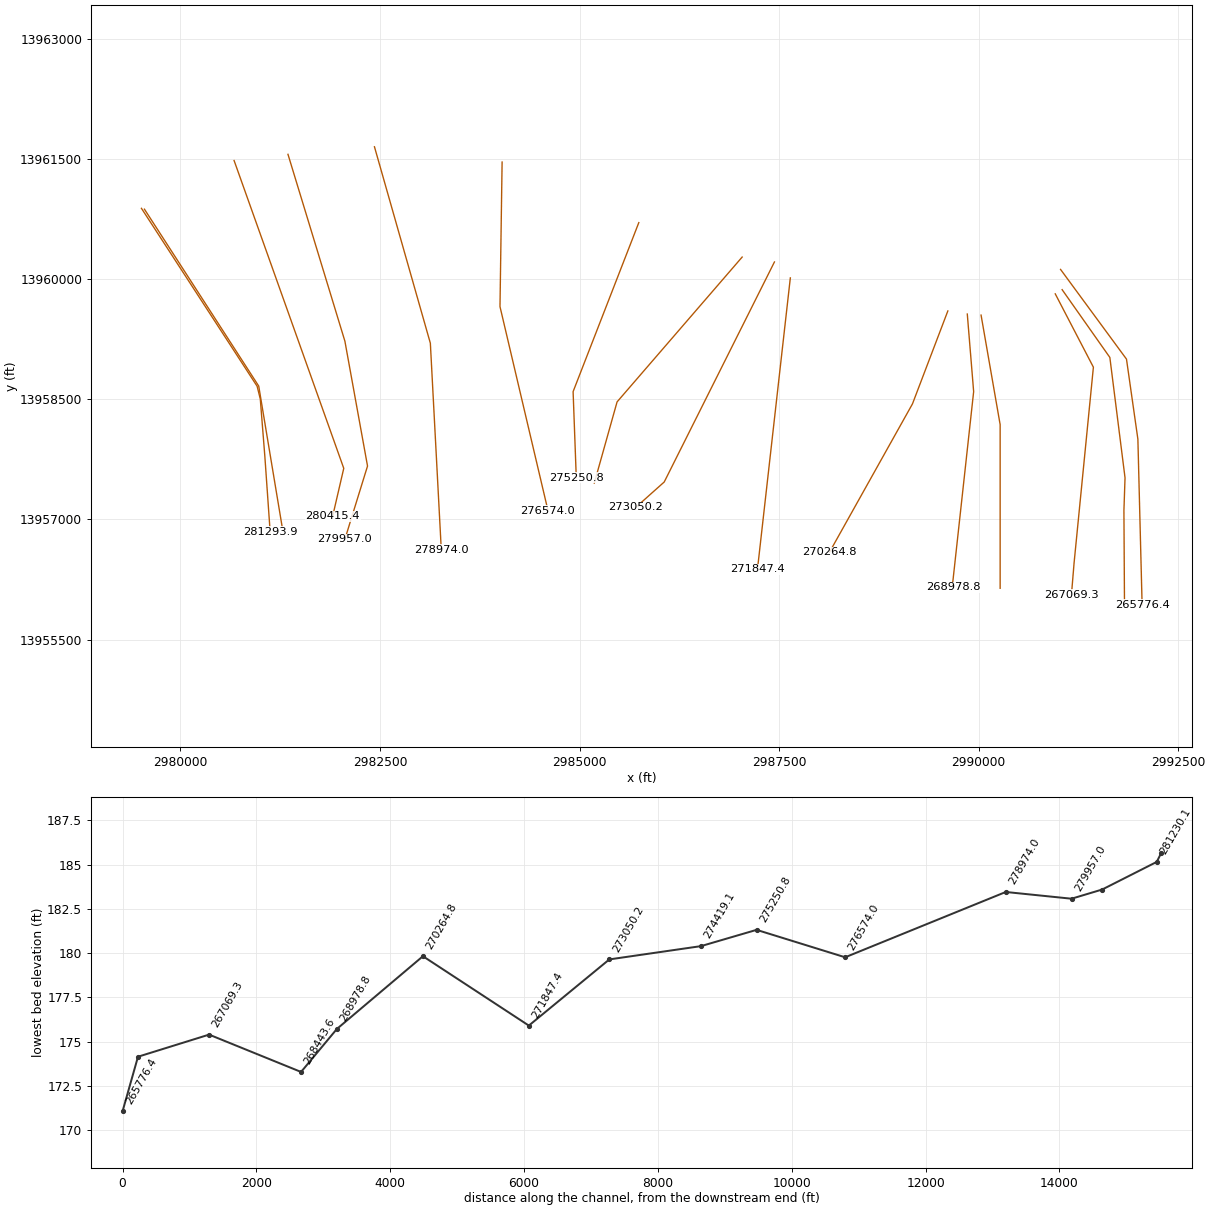
HEC-RAS study J100-00-00.prj: J100-00-00

--- J100-00-00.g01 (geometry) --- (continued)

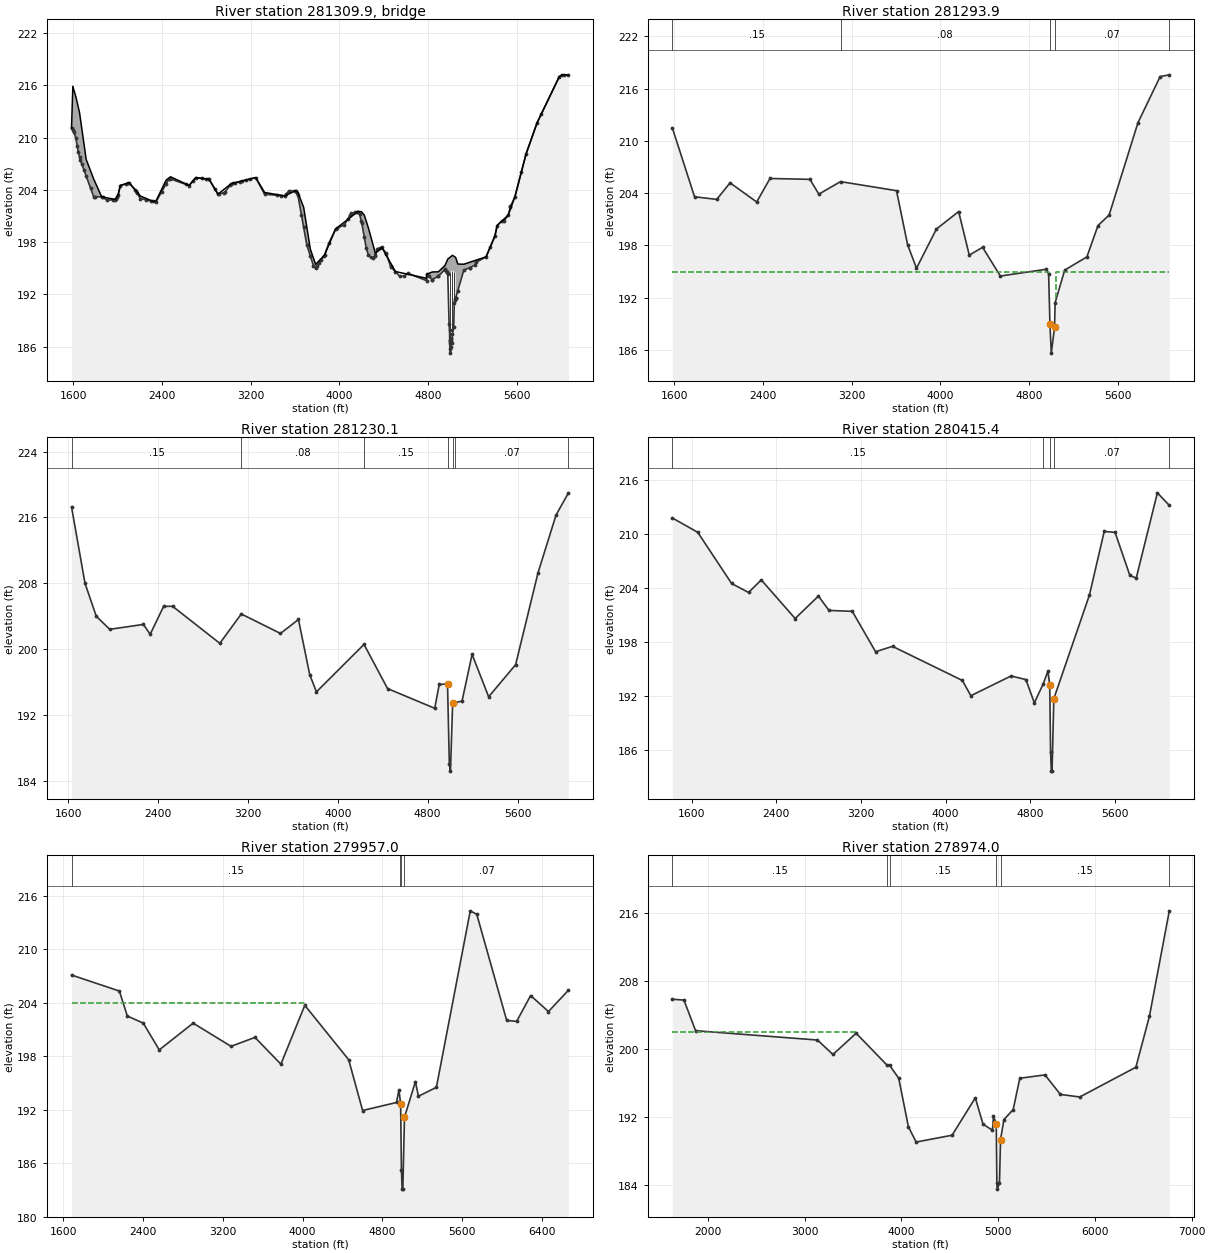
Type RM Length L Ch R = 3 ,281309.9,,,
BEGIN DESCRIPTION:
WD BRDG, APPROX. 6,615' DS NICHOLS MURRELL RD.
Structure ID: J100-00-00-13a
Circular piers, twin-cylinder piers without diaphragm
END DESCRIPTION:
Node Name=DS Nichols Murre
Bridge Culvert--1,0,-1,-1, 0
Deck Dist Width WeirC Skew NumUp NumDn MinLoCord MaxHiCord MaxSubmerge Is_Ogee
10,12,2.6,0, 60, 60, , , .95, 0, 1,1,,
    1585    1597    1625    1657    1717    1785    1857    1977    2005    2025
    2105    2205    2317    2345    2437    2477    2645    2705    2825    2905
    3025    3245    3325    3505    3605    3625    3677    3705    3737    3785
    3865    3965    4165    4197  4223.6  4260.9  4323.6  4380.9  4503.6  4785.5
 4785.61    4836    4891  4950.2  4975.9  5017.9 5046.59  5046.7  5066.3  5120.7
  5320.9  5400.9  5420.9  5520.9  5580.9  5680.9  5780.9  5980.9  6007.3  6063.6
   211.1   215.9  214.64   212.9   207.5  205.24   203.2   202.9  203.41  204.51
  204.81   203.3  202.69   202.7   205.1   205.5  204.51  205.41  205.21  203.51
  204.71  205.41   203.7  203.31   203.9   203.7     202  199.76   197.2  195.44
  196.51  199.51  201.51   201.5   201.1  199.61   196.7  197.41  194.62  193.84
   194.3  194.57  194.59   195.3  196.05  196.48  196.25  196.24  195.48  195.46
  196.31  198.71  199.91  201.11  203.21  208.11  211.71  217.01  217.21   217.2
   211.1  210.86   209.9   207.8  205.58   203.2   203.2  202.89   203.4   204.5
   204.8     203  202.68   202.6  204.67  205.25   204.5   205.4   205.2   203.5
   204.7   205.4   203.5   203.3   203.9   203.4   199.7   197.7  196.42     195
   196.5   199.5   201.5   200.4  198.55   196.5  196.51   197.4  194.61  193.57
  194.29   193.7  194.07  194.87  194.38  194.73   194.5  191.57  192.42  194.78
   196.3   198.7   199.9   201.1   203.2   208.1   211.7     217   217.2   217.2
    1585    1597    1625    1657    1717    1785    1905    1985    2025    2105
    2205    2345    2465    2645    2705    2825    2905    3025    3245    3325
    3505    3605    3625    3677    3705    3737    3785    3865    3965    4165
    4197  4223.6  4260.9  4320.9  4340.9  4380.9  4460.9  4540.9  4620.9  4785.5
 4785.61    4836    4891  4950.2  4975.9  5017.9 5046.59  5046.7  5066.3  5120.7
  5320.9  5400.9  5420.9  5520.9  5580.9  5680.9  5780.9  5980.9  6007.3  6063.6
  211.57   215.9  214.64   212.9   207.5  205.24  203.27  203.37  204.97  205.27
  203.47  203.07  205.77  204.97  205.87  205.67  203.97  205.17  205.87  203.97
  203.77  204.37  203.87     202  199.76   197.2  195.47  196.97  199.97  201.97
   201.5   201.1  199.61  196.87  197.67  197.87  195.73  194.57  194.87  194.04
  194.76  194.57  194.59  195.34  196.05  196.48  196.25  196.24  195.48  195.46
  196.77  199.17  200.37  201.57  203.67  208.57  212.17  217.47  217.67  217.67
  211.57  211.33  210.37  208.27  206.05  203.67  203.27  203.37  204.97  205.27
  203.47  203.07  205.77  204.97  205.87  205.67  203.97  205.17  205.87  203.97
  203.77  204.37  203.87  200.17  198.17  196.89  195.47  196.97  199.97  201.97
  200.87  199.02  196.97  196.87  197.67  197.87  195.67  194.57  194.87  194.04
  194.76  194.17  194.54  195.34  194.85   195.2  194.97  192.04  192.89  195.25
  196.77  199.17  200.37  201.57  203.67  208.57  212.17  217.47  217.67  217.67
Pier Skew, UpSta & Num, DnSta & Num=  ,4994.2, 2 ,4994.2, 2 , 0 , 0 , 0 ,,
       1       1
  184.71  195.59
       1       1
  185.18  196.06
Pier Skew, UpSta & Num, DnSta & Num=  ,5015, 2 ,5015, 2 , 0 , 0 , 0 ,,
       1       1
  185.48  195.75
       1       1
  185.95  196.22
Pier Skew, UpSta & Num, DnSta & Num=  ,5034.4, 2 ,5034.4, 2 , 0 , 0 , 0 ,,
       1       1
  189.76  195.59
       1       1
  190.23  196.06
Abutment Skew #Up #Dn= , 2 , 2
  4968.8  4993.8
  194.51   186.7
  4968.8  4993.8
  194.98  187.17
Abutment Skew #Up #Dn= , 2 , 2
  5040.6 5046.79
  191.31   194.5
  5040.6 5046.79
  191.78  194.97
BR Coef= 1 , 1 , 1 ,1.05, 0 ,,,.8,0,1.2,0,
WSPro=,,,, 1 ,,,, 0 ,,,, 0 ,,,,-1 ,-1 ,-1 , 0 , 0 , 0 , 0 , 0
BR U #Sta/Elev= 170
    1585   211.1    1597  210.86    1605   210.7    1625   209.9    1637     209
    1645   208.4    1657   207.8    1665   207.4    1677  206.98    1697  206.28
    1717  205.58    1757  204.18    1785   203.2    1797   203.2    1857   203.2
    1865   203.2    1905   202.8    1957  202.87    1977  202.89    1985   202.9
    1997   203.2    2005   203.4    2025   204.5    2077   204.7    2097  204.77
    2105   204.8    2157  204.02    2165   203.9    2177  203.63    2205     203
    2257  202.85    2297  202.74    2317  202.68    2345   202.6    2397  203.77
    2437  204.67    2465   205.3    2477  205.25    2617  204.62    2645   204.5
    2677  204.98    2705   205.4    2757  205.31    2797  205.25    2817  205.21
    2825   205.2    2877   204.1    2905   203.5    2917  203.54    2957  203.67
    2965   203.7    3017  204.57    3025   204.7    3037  204.74    3057   204.8
  3100.5  204.94    3117  204.99    3157  205.12    3197  205.25    3245   205.4
    3325   203.5    3437  203.38    3477  203.33    3505   203.3    3517  203.48
    3545   203.9    3597   203.9    3605   203.9    3617   203.6    3625   203.4
    3657  201.12    3677   199.7    3705   197.7    3737  196.42    3765   195.3
    3785     195    3797  195.23    3817   195.6    3837  195.98    3857  196.35
    3865   196.5    3905   197.9    3965   199.5    3977  199.58    4045     200
    4077  200.69    4097  201.13    4105   201.3    4137  201.41    4157  201.47
    4165   201.5  4180.9   201.2    4197   200.4  4200.9   200.2  4223.6  198.55
  4240.9   197.3  4260.9   196.5  4283.6  196.33  4300.9   196.2  4320.9   196.4
  4323.6  196.51  4340.9   197.2  4343.6  197.21  4363.6  197.31  4380.9   197.4
  4420.9   196.7  4423.6   196.6  4460.9   195.2  4463.6  195.16  4503.6  194.61
  4540.9   194.1  4580.9   194.1  4620.9   194.4  4785.5  193.57 4785.61  194.29
  4803.6  194.08    4836   193.7  4836.1   193.7  4890.6  194.07    4891  194.07
  4950.2  194.87  4951.8  194.84  4968.8  194.52 4968.91  194.51    4969  194.51
  4975.9  194.38  4987.7  188.55  4992.1  187.85  4993.7  186.77  4993.8   186.7
  4994.2  186.39  4994.3  185.75    5000  185.25  5004.6   185.9  5006.2   186.7
  5007.3  186.99  5008.6   186.9    5015  186.44  5017.9  187.41  5029.4   188.2
  5034.4  191.04  5040.6  191.31  5044.9   191.5  5046.5  191.56 5046.59  191.57
  5046.7  191.57  5066.3  192.42  5120.7  194.78  5174.6  195.07  5175.1  195.07
    5225  195.41  5226.9  195.66  5320.9   196.3  5359.3  197.45  5400.9   198.7
  5420.9   199.9  5460.9   200.4  5480.9   200.4  5520.9   201.1  5539.3  202.02
  5540.9   202.1  5580.9   203.2  5639.3  206.06  5680.9   208.1  5780.9   211.7
  5819.3  212.72  5980.9     217  6007.3   217.2  6019.3   217.2  6063.6   217.2
BR U #Mann= 4
    1585     .15  3100.5     .08  4987.7    .075  5029.4     .07
BR U Banks=4987.7,5029.4
BR D #Sta/Elev= 170
    1585  211.57    1597  211.33    1605  211.17    1625  210.37    1637  209.47
    1645  208.87    1657  208.27    1665  207.87    1677  207.45    1697  206.75
    1717  206.05    1757  204.65    1785  203.67    1797  203.67    1857  203.67
    1865  203.67    1905  203.27    1957  203.34    1977  203.36    1985  203.37
    1997  203.67    2005  203.87    2025  204.97    2077  205.17    2097  205.24
    2105  205.27    2157  204.49    2165  204.37    2177   204.1    2205  203.47
    2257  203.32    2297  203.21    2317  203.15    2345  203.07    2397  204.24
    2437  205.14    2465  205.77    2477  205.72    2617  205.09    2645  204.97
    2677  205.45    2705  205.87    2757  205.78    2797  205.72    2817  205.68
    2825  205.67    2877  204.57    2905  203.97    2917  204.01    2957  204.14
    2965  204.17    3017  205.04    3025  205.17    3037  205.21    3057  205.27
  3100.5  205.41    3117  205.46    3157  205.59    3197  205.72    3245  205.87
    3325  203.97    3437  203.85    3477   203.8    3505  203.77    3517  203.95
    3545  204.37    3597  204.37    3605  204.37    3617  204.07    3625  203.87
    3657  201.59    3677  200.17    3705  198.17    3737  196.89    3765  195.77
    3785  195.47    3797   195.7    3817  196.07    3837  196.45    3857  196.82
    3865  196.97    3905  198.37    3965  199.97    3977  200.05    4045  200.47
    4077  201.16    4097   201.6    4105  201.77    4137  201.88    4157  201.94
    4165  201.97  4180.9  201.67    4197  200.87  4200.9  200.67  4223.6  199.02
  4240.9  197.77  4260.9  196.97  4283.6   196.8  4300.9  196.67  4320.9  196.87
  4323.6  196.98  4340.9  197.67  4343.6  197.68  4363.6  197.78  4380.9  197.87
  4420.9  197.17  4423.6  197.07  4460.9  195.67  4463.6  195.63  4503.6  195.08
  4540.9  194.57  4580.9  194.57  4620.9  194.87  4785.5  194.04 4785.61  194.76
  4803.6  194.55    4836  194.17  4836.1  194.17  4890.6  194.54    4891  194.54
  4950.2  195.34  4951.8  195.31  4968.8  194.99 4968.91  194.98    4969  194.98
  4975.9  194.85  4987.7  189.02  4992.1  188.32  4993.7  187.24  4993.8  187.17
  4994.2  186.86  4994.3  186.22    5000  185.72  5004.6  186.37  5006.2  187.17
  5007.3  187.46  5008.6  187.37    5015  186.91  5017.9  187.88  5029.4  188.67
  5034.4  191.51  5040.6  191.78  5044.9  191.97  5046.5  192.03 5046.59  192.04
  5046.7  192.04  5066.3  192.89  5120.7  195.25  5174.6  195.54  5175.1  195.54
    5225  195.88  5226.9  196.13  5320.9  196.77  5359.3  197.92  5400.9  199.17
  5420.9  200.37  5460.9  200.87  5480.9  200.87  5520.9  201.57  5539.3  202.49
  5540.9  202.57  5580.9  203.67  5639.3  206.53  5680.9  208.57  5780.9  212.17
  5819.3  213.19  5980.9  217.47  6007.3  217.67  6019.3  217.67  6063.6  217.67
BR D #Mann= 4
    1585     .15  3100.5     .08  4987.7    .075  5029.4     .07
BR D Banks=4987.7,5029.4
BC Design=,, 0 ,, 0 ,,,,,,
BC HTab HWMax=217.2

Type RM Length L Ch R = 1 ,281293.9,63.8,63.8,63.8
BEGIN DESCRIPTION:
Downstream Section of Wood Bridge DS of Nichols Murrell
END DESCRIPTION:
XS GIS Cut Line= 5
    2979511.7118   13960885.4319    2980960.6104   13958663.7472
    2981000.4105   13958504.5464    2981057.4678   13957788.9204
    2981123.9422   13956846.2833
#Sta/Elev= 30
    1585  211.49    1785  203.59    1985  203.29    2105  205.19    2345  202.99
    2465  205.69    2825  205.59    2905  203.89  3100.5  205.33    3605  204.29
    3705  198.09    3785  195.39    3965  199.89    4165  201.89  4260.9  196.89
  4380.9  197.79  4540.9  194.49  4950.2  195.26  4975.9  194.77  4987.7  188.94
    5000  185.64  5029.4  188.59  5034.4  191.43  5120.7  195.17  5320.9  196.69
  5420.9  200.29  5520.9  201.49  5780.9  212.09  5980.9  217.39  6063.6  217.59
#Mann= 5 ,-1 , 0
    1585     .15       0  3100.5     .08       0  4987.7     .08       0
  5029.4     .07       0  6063.6      .2       0
#XS Ineff= 2 , 0
       0  4975.9     195  5046.8       0     195
Permanent Ineff=
       F       F
Bank Sta=4987.7,5029.4
XS Rating Curve= 0
Exp/Cntr=.5,.3

Type RM Length L Ch R = 1 ,281230.1,745.58,814.7,885.06
BEGIN DESCRIPTION:
Cross Section XS212
END DESCRIPTION:
XS GIS Cut Line= 3
    2979549.0138   13960874.9474    2980980.8888   13958665.5034
    2981275.7753   13956899.3379
#Sta/Elev= 30
    1630   217.3  1750.1     208  1850.1     204  1970.1   202.4  2270.1     203
  2330.1   201.8  2450.1   205.2  2530.1   205.2  2950.1   200.7  3141.4  204.27
  3490.1   201.9  3650.1   203.6  3750.1   196.9  3810.1   194.8  4233.7  200.57
    4443   195.2    4863   192.8    4903   195.7    4977  195.75  4993.1  186.01
  5003.1  185.16  5022.6  193.45  5042.8   193.5    5106  193.67  5195.7  199.36
    5343   194.2    5583   198.1    5783   209.3    5943   216.3  6053.6     219
#Mann= 7 ,-1 , 0
    1630     .15       0  3141.4     .08       0  4233.7     .15       0
    4977     .08       0  5022.6     .15       0  5042.8     .07       0
  6053.6      .2       0
Bank Sta=4977,5022.6
XS Rating Curve= 0
Exp/Cntr=.3,.1

Type RM Length L Ch R = 1 ,280415.4,458.4,458.4,458.4
BEGIN DESCRIPTION:
Cross Section XS211.5
END DESCRIPTION:
XS GIS Cut Line= 3
    2980672.2775   13961482.3172    2982046.2206   13957638.0521
    2981907.4384    13957041.289
#Sta/Elev= 30
  1418.4   211.8  1658.4   210.2  1978.4   204.5  2138.4   203.5  2258.4   204.9
  2578.4   200.6  2798.4   203.1  2898.4   201.5  3118.4   201.4  3338.4   196.9
  3498.4   197.5  4158.4   193.7  4238.4     192  4618.4   194.2  4758.4   193.8
  4838.4   191.2  4923.5  193.36  4966.8  194.74  4983.7  193.17  4991.6  185.77
  4998.6   183.6  5005.9  183.65  5022.2  191.66  5358.4   203.2  5498.4   210.3
  5600.8   210.2  5740.8   205.4  5800.8   205.1  6000.8   214.6  6113.5   213.2
#Mann= 5 , 1 , 0
  1418.4     .15       0  4923.5     .07       0  4983.7     .08       0
  5022.2     .07       0  6113.5      .2       0
Bank Sta=4983.7,5022.2
XS Rating Curve= 0
Exp/Cntr=.3,.1

Type RM Length L Ch R = 1 ,279957.0,1028.39,983,893.64
BEGIN DESCRIPTION:
Cross Section XS211
Ineffective at Sta 4025 based on topo downstream of the cross section
END DESCRIPTION:
XS GIS Cut Line= 5
    2981347.4144   13961559.9445    2982060.4066   13959226.5937
    2982344.0094    13957666.778    2982136.8777   13956999.3534
     2982060.126    13956750.162
#Sta/Elev= 30
  1682.4   207.1  2162.4   205.3  2242.4   202.5  2402.4   201.7  2562.4   198.7
  2902.4   201.7  3282.4   199.1  3522.4   200.1  3782.4   197.1  4022.4   203.7
  4462.3   197.6  4602.3   191.9  4942.3   192.8  4966.8  194.22  4981.2  192.88
  4983.7  192.65  4991.6  185.25  4998.6  183.08  5005.9  183.13  5022.2  191.14
  5131.8  195.14  5162.3   193.5  5342.3   194.5  5682.3   214.3  5747.6   213.9
  6047.6     202  6147.6   201.9  6287.6   204.8  6466.5     203  6667.2   205.4
#Mann= 4 ,-1 , 0
  1682.4     .15       0  4981.2     .07       0  4983.7     .08       0
  5022.2     .07       0
#XS Ineff= 2 , 0
       0    4025     204               0
Permanent Ineff=
       F       F
Bank Sta=4983.7,5022.2
XS Rating Curve= 0
Exp/Cntr=.3,.1

Type RM Length L Ch R = 1 ,278974.0,1122.13,2400,1209.91
BEGIN DESCRIPTION:
Cross Section XS210
Ineffective at Sta 3535 based on topo downstream of the cross section
END DESCRIPTION:
XS GIS Cut Line= 3
    2982430.7074   13961654.6011    2983131.0159   13959201.0426
    2983268.1109   13956619.0873
#Sta/Elev= 30
  1631.9   205.8  1751.9   205.7  1871.9   202.1  3131.9     201  3291.9   199.3
  3531.9   201.8  3849.7  198.06  3878.4  198.01  3971.9   196.5  4071.9   190.8
  4151.9     189  4523.4   189.8  4763.4   194.2  4843.4   191.1  4940.6  190.39
  4951.4  192.03    4980  191.17  4986.5  184.15  4990.1  183.46  5013.4  184.18
  5024.2  189.29  5059.3  191.65  5154.8  192.81  5223.4   196.5  5483.4   196.9
  5643.4   194.6  5843.4   194.3  6423.4   197.8  6563.4   203.8    6769   216.2
#Mann= 6 ,-1 , 0
  1631.9     .15       0  3849.7     .15       0  3878.4     .15       0
    4980     .08       0  5024.2     .15       0    6769      .2       0
#XS Ineff= 2 , 0
       0    3535     202               0
Permanent Ineff=
       F       F
Bank Sta=4980,5024.2
XS Rating Curve= 0
Exp/Cntr=.3,.1

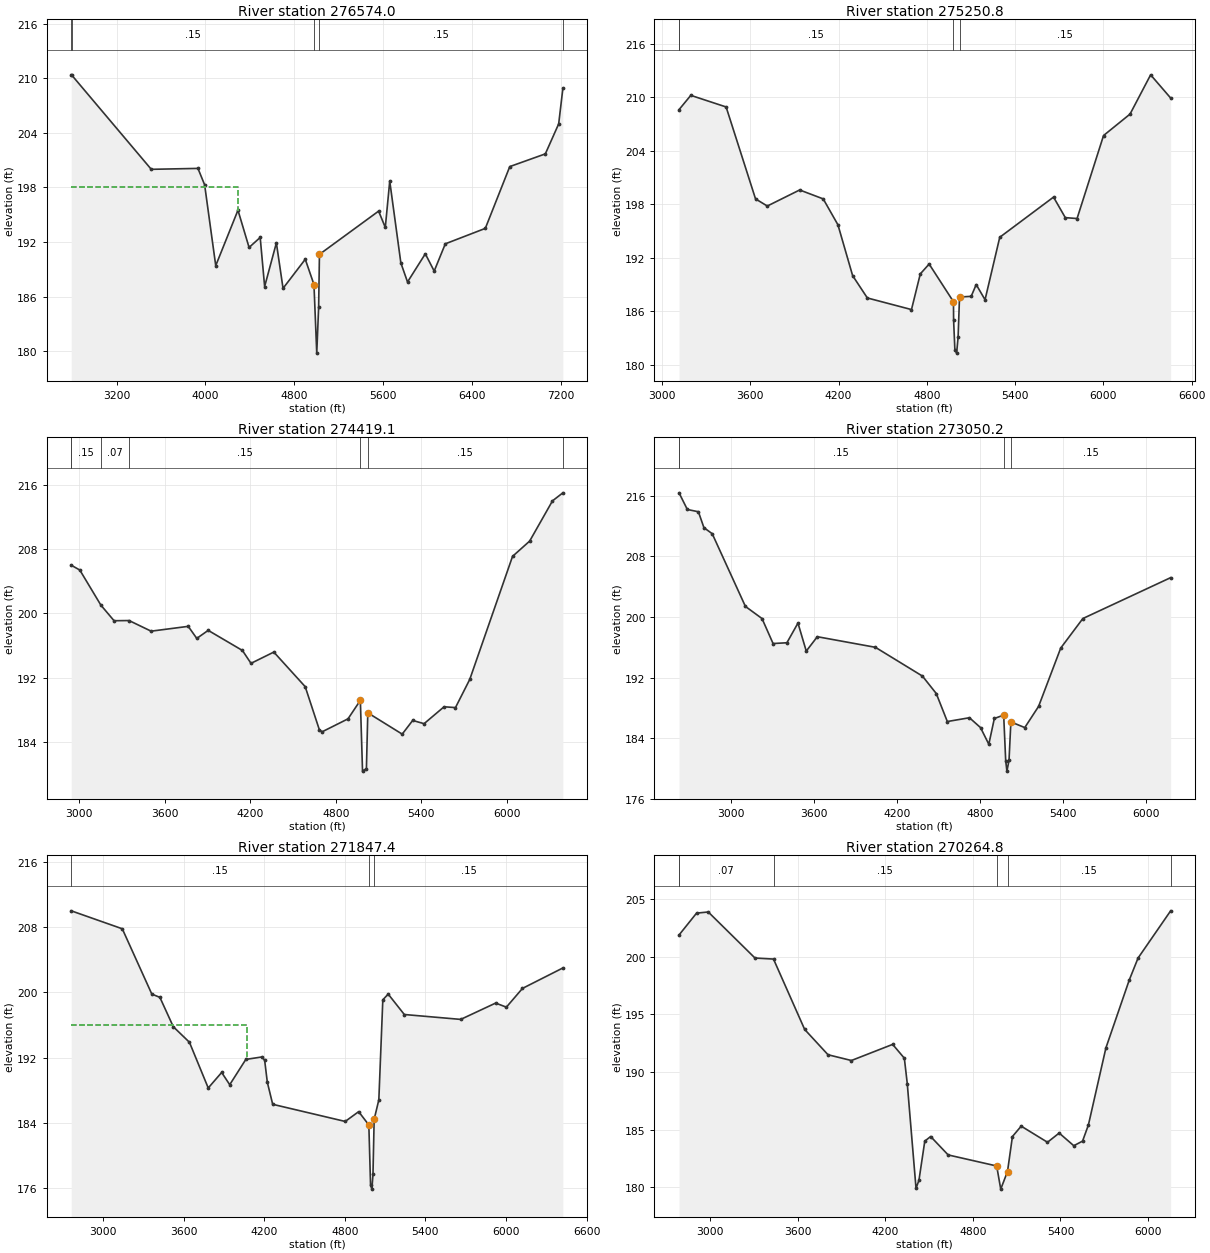
Type RM Length L Ch R = 1 ,276574.0,1343.69,1323.2,594.19
BEGIN DESCRIPTION:
Cross Section XS209
Ineffective at Sta 4295 based on topo upstream of the cross section
END DESCRIPTION:
XS GIS Cut Line= 3
    2984029.9569   13961463.4785    2984003.4065   13959658.0545
    2984604.7868   13957110.3443
#Sta/Elev= 30
  2792.3   210.4  2795.9  210.38  3512.3     200  3932.3   200.1  3992.3   198.3
  4092.3   189.4  4292.3   195.5  4392.3   191.4  4492.3   192.5  4532.3   187.1
  4637.9   191.9  4697.9   186.9  4897.9   190.1  4976.1  187.32  5001.2  179.77
  5018.2  184.84  5025.5  190.64  5557.9   195.4  5617.9   193.6  5657.9   198.7
  5757.9   189.7  5817.9   187.6  5977.9   190.7  6057.9   188.8  6157.9   191.8
  6517.9   193.5  6737.9   200.3  7057.9   201.7  7177.9     205  7215.6   208.9
#Mann= 5 ,-1 , 0
  2792.3      .1       0  2795.9     .15       0  4976.1     .08       0
  5025.5     .15       0  7215.6      .2       0
#XS Ineff= 2 , 0
       0    4295     198               0
Permanent Ineff=
       F       F
Bank Sta=4976.1,5025.5
XS Rating Curve= 0
Exp/Cntr=.3,.1

Type RM Length L Ch R = 1 ,275250.8,841.24,831.7,457.56
BEGIN DESCRIPTION:
Cross Section XS208
END DESCRIPTION:
XS GIS Cut Line= 3
    2985742.4547   13960706.7934    2984919.3937   13958596.0403
    2984959.2192    13957520.751
#Sta/Elev= 30
  3115.6   208.6  3195.6   210.2  3435.6   208.9  3635.6   198.6  3715.6   197.8
  3935.6   199.6  4095.6   198.6  4195.6   195.7  4295.6     190  4395.6   187.5
  4695.6   186.2  4755.6   190.2  4815.6   191.3    4981  187.08  4981.9  185.02
  4990.5  181.71  5002.4  181.32  5012.5  183.11  5022.1  187.61  5101.3  187.68
  5135.6     189  5195.6   187.3  5295.6   194.3  5661.1   198.8  5741.1   196.5
  5821.1   196.4  6001.1   205.7  6181.1   208.1  6321.1   212.5  6457.2   209.9
#Mann= 4 , 1 , 0
  3115.6      .2       0  3115.6     .15       0    4981     .08       0
  5022.1     .15       0
Bank Sta=4981,5022.1
XS Rating Curve= 0
Exp/Cntr=.3,.1

Type RM Length L Ch R = 1 ,274419.1,779.79,1368.9,922.34
BEGIN DESCRIPTION:
Cross Section XS207
END DESCRIPTION:
XS GIS Cut Line= 3
    2987037.3321   13960276.8207    2985470.2383   13958467.8265
    2985184.8972   13957454.3751
#Sta/Elev= 30
  2945.8     206  3005.8   205.4  3153.4  201.04  3245.8   199.1  3351.1  199.12
  3505.8   197.8  3765.8   198.4  3825.8   196.9  3905.8   197.9  4145.8   195.4
  4205.8   193.8  4365.8   195.2  4585.8   190.9  4685.8   185.5  4705.8   185.3
  4885.8   186.9  4972.4   189.2  4987.7   180.4  5014.9  180.72  5024.6  187.65
  5265.8     185  5339.2   186.7  5419.2   186.3  5559.2   188.4  5639.2   188.3
  5739.2   191.8  6039.2   207.1  6159.2     209  6319.2     214    6392     215
#Mann= 7 , 1 , 0
  2945.8      .2       0  2945.8     .15       0  3153.4     .07       0
  3351.1     .15       0  4972.4     .08       0  5024.6     .15       0
    6392      .2       0
Bank Sta=4972.4,5024.6
XS Rating Curve= 0
Exp/Cntr=.3,.1

Type RM Length L Ch R = 1 ,273050.2,853.01,1202.8,1184.16
BEGIN DESCRIPTION:
Cross Section XS206
END DESCRIPTION:
XS GIS Cut Line= 3
    2987441.6773   13960215.6119    2986061.0589   13957467.6503
    2985702.6291   13957149.0461
#Sta/Elev= 30
  2625.9   216.4  2685.9   214.2  2765.9   213.9  2805.9   211.8  2865.9     211
  3105.9   201.4  3225.9   199.8  3305.9   196.5  3405.9   196.6  3485.9   199.2
  3545.9   195.5  3625.9   197.4  4045.9     196  4385.9   192.2  4485.9   189.9
  4565.9   186.2  4725.9   186.7  4805.9   185.4  4865.9   183.2  4905.9   186.6
  4973.4  187.05    4988  181.03  4996.8  179.65    5012  181.06  5025.5  186.15
  5125.9   185.4  5225.9   188.2  5385.9   195.9  5545.9   199.8  6180.8   205.2
#Mann= 4 , 1 , 0
  2625.9      .2       0  2625.9     .15       0  4973.4     .08       0
  5025.5     .15       0
Bank Sta=4973.4,5025.5
XS Rating Curve= 0
Exp/Cntr=.3,.1

Type RM Length L Ch R = 1 ,271847.4,1627.49,1582.6,1191.97
BEGIN DESCRIPTION:
Cross Section XS205
Ineffective at Sta 4075 based on topo upstream of the cross section
END DESCRIPTION:
XS GIS Cut Line= 2
    2987640.8049   13960016.4842    2987229.2744   13956379.0858
#Sta/Elev= 30
  2763.3     210  3143.3   207.8  3363.3   199.8  3423.3   199.4  3523.3   195.8
  3643.3   193.9  3783.3   188.3  3883.3   190.2  3943.3   188.7  4063.3   191.8
  4183.3   192.1  4203.3   191.7  4223.3     189  4263.3   186.3  4803.3   184.2
  4903.3   185.4  4979.2  183.77  4991.9  176.43  5001.8  175.91    5010  177.72
  5018.7  184.45  5053.6  186.85  5083.3   199.1  5123.3   199.8  5243.3   197.3
  5663.3   196.7  5923.3   198.7  6003.3   198.2  6123.3   200.5  6423.9     203
#Mann= 3 ,-1 , 0
  2763.3     .15       0  4979.2     .08       0  5018.7     .15       0
#XS Ineff= 2 , 0
       0    4075     196               0
Permanent Ineff=
       F       F
Bank Sta=4979.2,5018.7
XS Rating Curve= 0
Exp/Cntr=.3,.1

Type RM Length L Ch R = 1 ,270264.8,994.27,1286,1387.26
BEGIN DESCRIPTION:
Cross Section XS204
END DESCRIPTION:
XS GIS Cut Line= 3
     2989614.097   13959603.7066    2989170.8561   13958443.0226
    2988131.9864   13956591.4887
#Sta/Elev= 30
  2788.9   201.9  2908.9   203.8  2988.9   203.9  3308.9   199.9  3435.6  199.81
  3648.9   193.7  3808.9   191.5  3968.9     191  4251.3   192.4  4331.3   191.2
  4351.3     189  4411.3   179.9  4431.3   180.6  4471.3     184  4511.3   184.4
  4631.3   182.8  4963.5  181.84  4991.2  179.83  5037.5  181.36  5071.3   184.4
  5131.3   185.3  5311.3   183.9  5391.3   184.7  5491.3   183.6  5551.3     184
  5591.3   185.4  5711.3   192.1  5871.3     198  5931.3   199.9  6154.4     204
#Mann= 6 , 1 , 0
  2788.9      .2       0  2788.9     .07       0  3435.6     .15       0
  4963.5     .08       0  5037.5     .15       0  6154.4      .2       0
Bank Sta=4963.5,5037.5
XS Rating Curve= 0
Exp/Cntr=.3,.1

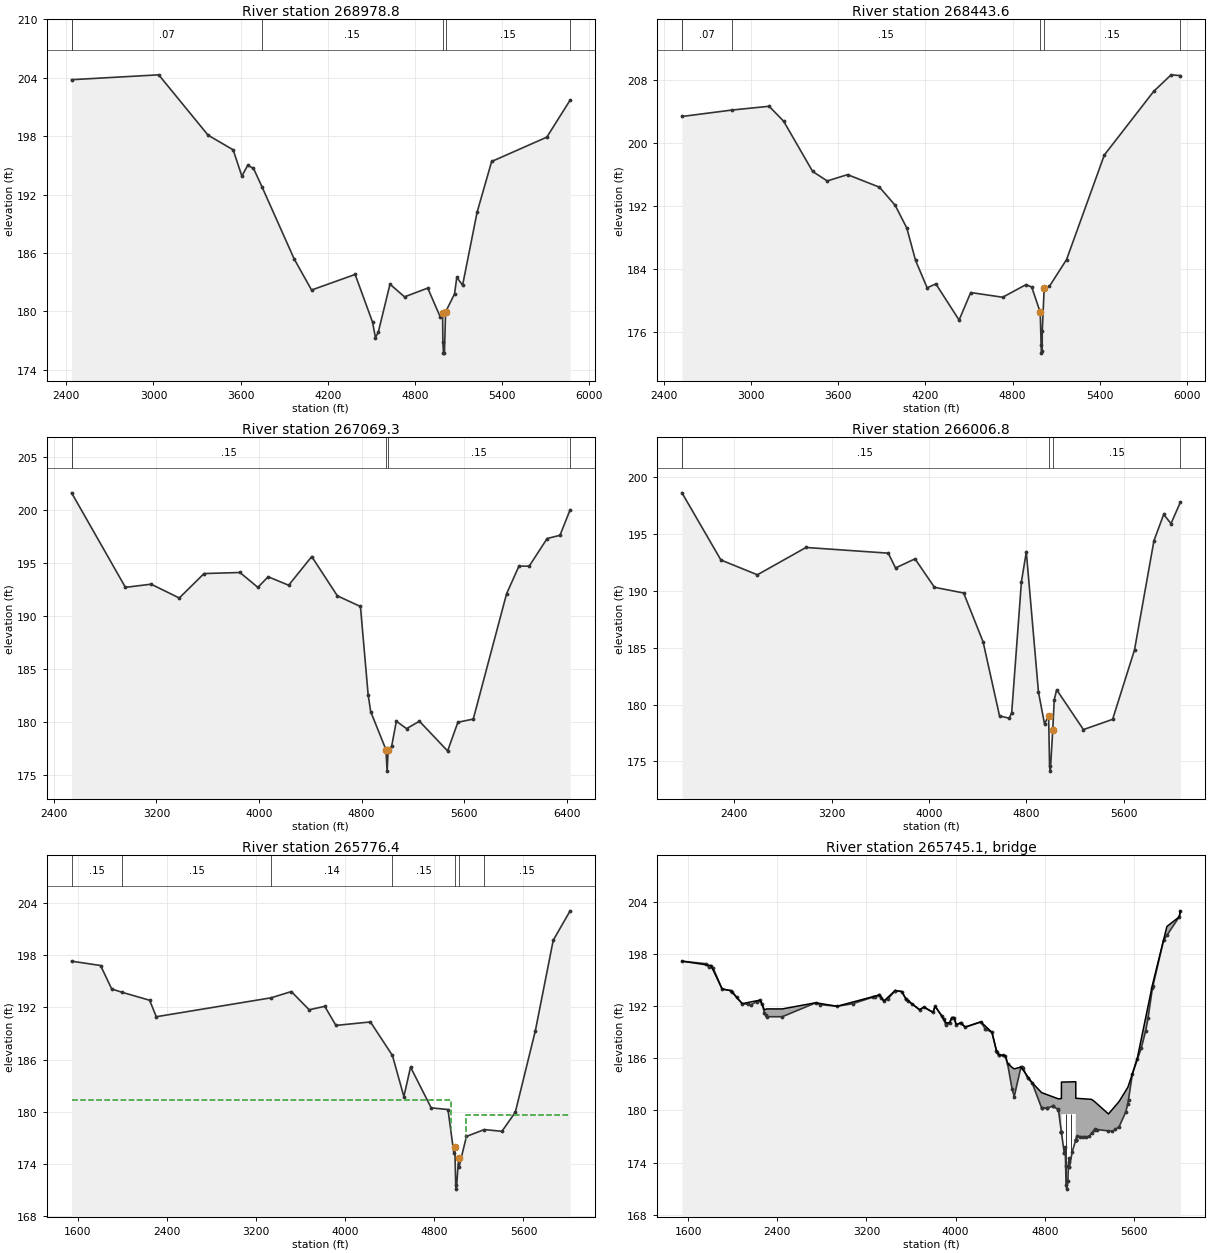
Type RM Length L Ch R = 1 ,268978.8,454.56,535.2,538.63
BEGIN DESCRIPTION:
Cross Section XS203
END DESCRIPTION:
XS GIS Cut Line= 4
    2989857.7594   13959565.1282    2989937.4105   13958596.0403
    2989671.9069   13956179.9582    2989685.1821   13956153.4078
#Sta/Elev= 30
  2436.5   203.8  3036.5   204.3  3376.5   198.1  3548.9   196.6  3608.9   193.9
  3648.9     195  3688.9   194.7    3747  192.82  3968.9   185.4  4088.9   182.2
  4388.9   183.8  4508.9   178.9  4528.9   177.3  4548.9   177.9  4628.9   182.8
  4728.9   181.5  4888.9   182.4  4975.8  179.41  4991.2  179.86  4993.1  176.84
  4997.3  175.72  5003.9  175.75  5011.8  179.95  5073.4   181.8  5088.9   183.5
  5128.9   182.7  5228.9   190.2  5328.9   195.4  5708.9   197.9  5869.2   201.7
#Mann= 6 , 1 , 0
  2436.5      .2       0  2436.5     .07       0    3747     .15       0
  4991.2     .08       0  5011.8     .15       0  5869.2      .2       0
Bank Sta=4991.2,5011.8
XS Rating Curve= 0
Exp/Cntr=.3,.1

Type RM Length L Ch R = 1 ,268443.6,1126.05,1374.3,981.06
BEGIN DESCRIPTION:
Cross Section XS202
END DESCRIPTION:
XS GIS Cut Line= 3
    2990030.3367   13959551.8531    2990269.2899   13958184.5099
    2990269.2899   13956140.1327
#Sta/Elev= 30
    2524   203.4  2868.6  204.22    3124   204.7    3224   202.8    3424   196.4
    3524   195.2    3664     196    3884   194.4  3992.1   192.1  4072.1   189.2
  4132.1   185.1  4212.1   181.6  4272.1   182.1  4432.1   177.5  4512.1     181
  4732.1   180.4  4892.1     182  4932.1   181.7  4990.8  178.48  4996.7  174.32
  4999.3  173.29  5003.9  173.52  5004.7  176.08  5017.8  181.53  5053.3  181.77
  5172.1   185.2  5432.1   198.5  5772.1   206.6  5892.1   208.7  5956.4   208.6
#Mann= 6 , 1 , 0
    2524      .2       0    2524     .07       0  2868.6     .15       0
  4990.8     .08       0  5017.8     .15       0  5956.4      .2       0
Bank Sta=4990.8,5017.8
XS Rating Curve= 0
Exp/Cntr=.3,.1

Type RM Length L Ch R = 1 ,267069.3,428.19,1062.5,730.42
BEGIN DESCRIPTION:
Cross Section XS201
END DESCRIPTION:
XS GIS Cut Line= 4
    2990959.5991   13959817.3566    2991437.5054   13958901.3694
    2991195.6005    13956456.856     2991162.583    13956059.126
#Sta/Elev= 30
  2538.4   201.6  2958.4   192.7  3158.4     193  3378.4   191.7  3571.6     194
  3851.6   194.1  3991.6   192.7  4071.6   193.7  4231.6   192.9  4411.6   195.6
  4611.6   191.9  4791.6   190.9  4851.6   182.6  4871.6     181  4990.3  177.43
  4999.6   175.4    5008  177.43  5034.9  177.73  5071.6   180.1  5151.6   179.4
  5251.6   180.1  5471.6   177.3  5551.6     180  5671.6   180.3  5931.6   192.1
    6028   194.7    6108   194.7    6248   197.3    6348   197.6  6427.1     200
#Mann= 5 , 1 , 0
  2538.4      .2       0  2538.4     .15       0  4990.3     .08       0
    5008     .15       0  6427.1      .2       0
Bank Sta=4990.3,5008
XS Rating Curve= 0
Exp/Cntr=.3,.1

Type RM Length L Ch R = 1 ,266006.8,169.42,230.45,136.07
BEGIN DESCRIPTION:
Cross Section XS200.5
END DESCRIPTION:
XS GIS Cut Line= 5
    2991046.0691   13959869.4429    2991643.7295   13959023.2114
    2991833.8304   13957520.0873    2991819.9522     13957110.68
    2991826.8913   13955972.6666
#Sta/Elev= 30
  1969.4   198.6  2289.4   192.7  2589.4   191.4  2989.4   193.8  3665.4   193.3
  3725.4     192  3885.4   192.8  4045.4   190.3  4285.4   189.8  4445.4   185.5
  4580.5     179  4660.5   178.8  4680.5   179.3  4760.5   190.8  4800.5   193.4
  4900.5   181.1  4950.1   178.3    4984  179.01  4991.7  174.58    4998  174.15
  5017.8  177.75  5030.1   180.4  5050.1   181.3  5270.1   177.8  5510.1   178.7
  5690.1   184.8  5850.1   194.4  5930.1   196.7  5990.1   195.9  6068.2   197.8
#Mann= 5 , 1 , 0
  1969.4      .2       0  1969.4     .15       0    4984     .08       0
  5017.8     .15       0  6068.2      .2       0
Bank Sta=4984,5017.8
XS Rating Curve= 0
Exp/Cntr=.5,.3

Type RM Length L Ch R = 1 ,265776.4,62.5,62.5,62.5
BEGIN DESCRIPTION:
Upstream Section of Roberts Cemetary
END DESCRIPTION:
XS GIS Cut Line= 4
    2991026.1939   13960122.4607    2991852.0574   13959002.1646
    2991994.8567   13958002.5695    2992047.9574   13955931.6419
#Sta/Elev= 30
  1545.1  197.33  1805.1  196.83  1905.1  194.13  1996.9  193.75  2245.1  192.83
  2305.1  190.93  3335.1  193.11  3516.9  193.83  3676.9  191.73  3816.9  192.13
  3916.9  189.93  4226.6  190.33  4423.9  186.47  4526.6  181.73  4586.6  185.13
  4771.8  180.43  4922.4  180.24  4975.1  175.22    4984  175.93  4991.7   171.5
    4998  171.07  5017.8  174.67  5022.2  173.64  5087.9  177.14  5247.8  177.93
  5406.6  177.73  5526.6  179.93  5706.6  189.33  5866.6  199.73  6018.3  203.13
#Mann= 7 ,-1 , 0
  1545.1     .15       0  1996.9     .15       0  3335.1     .14       0
  4423.9     .15       0    4984     .08       0  5017.8     .15       0
  5247.8     .15       0
#XS Ineff= 2 , 0
       0    4950   181.3    5080       0   179.6
Permanent Ineff=
       F       F
Bank Sta=4984,5017.8
XS Rating Curve= 0
Exp/Cntr=.5,.3

Type RM Length L Ch R = 3 ,265745.1,,,
BEGIN DESCRIPTION:
ROBERTS CEMETERY
Structure ID: J100-00-00-13
Square nose piers
END DESCRIPTION:
Node Name=Roberts Cemetery
Bridge Culvert--1,0,-1,-1, 0
Deck Dist Width WeirC Skew NumUp NumDn MinLoCord MaxHiCord MaxSubmerge Is_Ogee
10,42.5,2.6,0, 60, 60, , , .95, 0, 1,1,,
  1545.1  1805.1  1905.1  1985.1  2085.1  2245.1  2285.1  2305.1  2445.1  2745.1
  2936.9  3316.8  3356.9  3456.9  3516.9  3556.8  3676.9  3716.9  3796.9  3816.9
  3916.9  3946.6  3966.6  3986.6  4006.6  4046.6  4086.6  4226.6  4326.6  4366.6
  4386.6  4446.6  4466.6  4506.6  4526.6  4586.6  4686.6  4771.8  4922.4 4949.79
  4949.9    4950 5078.59 5078.69  5078.8  5078.9  5220.6  5249.6  5371.9  5466.6
  5526.6  5546.6  5586.6  5631.9  5706.6  5766.6  5866.6  5896.6  6006.6  6018.3
   197.2   196.7     194   193.8  192.31  192.71   191.6   191.7   191.7  192.41
  192.01  193.31  192.61  193.81  193.71  192.81  191.61  191.91  191.31  192.01
  190.09  190.11  190.71  190.71   189.9  190.11  189.61  190.21  189.01  186.91
  186.41  186.31  185.41  184.97  184.79  185.01  183.21  182.06  181.34  181.37
  181.37  183.27  183.31  183.31  183.31  181.41  181.28     181   179.6  181.02
  182.27  182.69  184.23   186.1  190.74  194.47  199.66   201.2   202.3     203
   197.2   196.7     194   193.8   192.3   192.7   191.2   190.8   190.8   192.4
     192   193.3   192.6   193.8   193.7   192.8   191.6   191.9   191.3     192
   189.8   190.1   190.7   190.7   189.8   190.1   189.6   190.2     189   186.9
   186.4   186.3   185.4   182.5   181.6     185   183.2   180.3  180.11   177.5
  179.57  179.57  179.61  176.61  176.62  176.62  177.39  177.83  177.65   178.1
   179.8   180.8   184.2   185.9   189.2   194.1   199.6  200.18   202.3     203
  1545.1  1805.1  1905.1  1985.1  2085.1  2245.1  2265.1  2285.1  2305.1  2445.1
  2745.1  2936.9  3316.8  3356.9  3456.9  3516.9  3556.8  3676.9  3716.9  3796.9
  3816.9  3916.9  3966.6  3986.6  4006.6  4046.6  4086.6  4226.6  4326.6  4366.6
  4386.6  4446.6  4466.6  4506.6  4526.6  4586.6  4686.6  4771.8  4922.4 4949.79
  4949.9    4950 5078.59 5078.69  5078.8  5078.9  5220.6  5249.6  5371.9  5466.6
  5526.6  5551.9  5586.6  5631.9  5706.6  5766.6  5866.6  5896.6  6006.6  6018.3
  197.68  197.18  194.48  194.28  192.78  193.18  192.78  191.68   191.7   191.7
  192.88  192.48  193.78  193.08  194.28  194.18  193.28  192.08  192.38  191.78
  192.48  190.28  191.18  191.18  190.28  190.58  190.08  190.68  189.48  187.38
  186.88  186.78  185.88  184.97  184.79  185.48  183.68  182.06  181.34  181.37
  181.37  183.27  183.31  183.31  183.31  181.41  181.28     181   179.6  181.02
  182.27   182.8  184.68  186.38  190.74  194.58  200.08   201.2  202.78  203.48
  197.68  197.18  194.48  194.28  192.78  193.18  192.78  191.68  191.28  191.28
  192.88  192.48  193.78  193.08  194.28  194.18  193.28  192.08  192.38  191.78
  192.48  190.28  191.18  191.18  190.28  190.58  190.08  190.68  189.48  187.38
  186.88  186.78  185.88  182.98  182.08  185.48  183.68  180.78  180.59  177.98
  180.05  180.05  180.09  177.09   177.1   177.1  177.87  178.31  178.13  178.58
  180.28  181.73  184.68  186.38  189.68  194.58  200.08  200.66  202.78  203.48
Pier Skew, UpSta & Num, DnSta & Num=  ,4992.9, 2 ,4992.9, 2 , 0 , 0 , 0 ,,
     1.5     1.5
  170.24   180.6
     1.5     1.5
  170.72  181.08
Pier Skew, UpSta & Num, DnSta & Num=  ,5036.2, 2 ,5036.2, 2 , 0 , 0 , 0 ,,
     1.5     1.5
  173.44  180.62
     1.5     1.5
  173.92   181.1
Abutment Skew #Up #Dn= , 2 , 2
  4949.7  4975.1
  179.57  175.09
  4949.7  4975.1
  180.05  175.57
Abutment Skew #Up #Dn= , 2 , 2
  5022.2 5078.79
  173.51  179.61
  5022.2 5078.79
  173.99  180.09
BR Coef= 1 , 1 , 1 ,1.25, 0 ,,,.8,0,2,0,
WSPro=,,,, 1 ,,,, 0 ,,,, 0 ,,,,-1 ,-1 ,-1 , 0 , 0 , 0 , 0 , 0
BR U #Sta/Elev= 128
  1545.1   197.2  1765.1   196.9  1785.1   196.5  1805.1   196.7  1825.1   196.4
  1905.1     194  1985.1   193.8  1996.9  193.62  2036.9  193.02  2085.1   192.3
  2136.9  192.24  2165.1   192.2  2216.9  192.52  2245.1   192.7  2265.1   192.3
  2285.1   191.2  2296.9  190.96  2305.1   190.8  2445.1   190.8  2745.1   192.4
  2785.1   192.2  2936.9     192  3076.9   192.3  3256.9  193.05  3276.9  193.13
  3316.8   193.3  3316.9   193.3  3335.1  192.98  3356.9   192.6  3396.9   192.9
  3456.8   193.8  3456.9   193.8  3516.9   193.7  3556.8   192.8  3556.9   192.8
  3576.9   192.6  3611.9  192.25  3676.9   191.6  3716.9   191.9  3796.9   191.3
  3816.9     192  3876.9   190.9  3891.9  190.49  3911.9  189.94  3916.9   189.8
  3946.6   190.1  3966.6   190.7  3986.6   190.7  4006.6   189.8  4046.6   190.1
  4051.9  190.03  4086.6   189.6  4226.6   190.2  4266.6   189.4  4271.9  189.36
  4326.6     189  4366.6   186.9  4371.9  186.77  4386.6   186.4  4391.9  186.39
  4423.9  186.34  4446.6   186.3  4466.6   185.4  4506.6   182.5  4526.6   181.6
  4586.6     185  4591.9  184.97  4606.6   184.9  4646.6   183.7  4686.6   183.2
  4771.2  180.32  4771.8   180.3  4820.1  180.26  4821.6  180.27  4869.9   180.5
    4870   180.5  4917.4  180.15  4922.4  180.11 4949.71  177.51 4949.79   177.5
  4949.9  177.49    4950  177.48 4950.11  177.47    4975   175.1  4975.1  175.09
    4984   175.8  4987.8  173.61  4991.7  171.37    4998  170.94  5007.8  171.86
  5012.1  173.57  5014.9  174.05  5017.8  174.54  5022.1  173.53  5022.2  173.51
  5046.7  175.23 5078.59  176.61 5078.69  176.61  5078.8  176.62  5078.9  176.62
 5079.01  176.63  5087.9  177.01  5119.2  176.99  5140.3  176.97  5169.8     177
    5197  177.03  5220.6  177.39  5247.8   177.8  5249.6  177.83  5269.7   177.8
  5371.9  177.65  5406.6   177.6  5431.9  177.81  5466.6   178.1  5526.6   179.8
  5546.6   180.8  5551.9  181.25  5586.6   184.2  5631.9   185.9  5666.6   187.2
  5706.6   189.2  5726.6   190.6  5766.6   194.1  5771.9  194.39  5866.6   199.6
  5896.6  200.18  6006.6   202.3  6018.3     203
BR U #Mann= 7
  1545.1     .15  3335.1     .14  4423.9     .15    4984    .075  5017.8     .15
  5247.8     .15  5896.6      .2
BR U Banks=4984,5017.8
BR D #Sta/Elev= 128
  1545.1  197.68  1765.1  197.38  1785.1  196.98  1805.1  197.18  1825.1  196.88
  1905.1  194.48  1985.1  194.28  1996.9   194.1  2036.9   193.5  2085.1  192.78
  2136.9  192.72  2165.1  192.68  2216.9     193  2245.1  193.18  2265.1  192.78
  2285.1  191.68  2296.9  191.44  2305.1  191.28  2445.1  191.28  2745.1  192.88
  2785.1  192.68  2936.9  192.48  3076.9  192.78  3256.9  193.53  3276.9  193.61
  3316.8  193.78  3316.9  193.78  3335.1  193.46  3356.9  193.08  3396.9  193.38
  3456.8  194.28  3456.9  194.28  3516.9  194.18  3556.8  193.28  3556.9  193.28
  3576.9  193.08  3611.9  192.73  3676.9  192.08  3716.9  192.38  3796.9  191.78
  3816.9  192.48  3876.9  191.38  3891.9  190.97  3911.9  190.42  3916.9  190.28
  3946.6  190.58  3966.6  191.18  3986.6  191.18  4006.6  190.28  4046.6  190.58
  4051.9  190.51  4086.6  190.08  4226.6  190.68  4266.6  189.88  4271.9  189.84
  4326.6  189.48  4366.6  187.38  4371.9  187.25  4386.6  186.88  4391.9  186.87
  4423.9  186.82  4446.6  186.78  4466.6  185.88  4506.6  182.98  4526.6  182.08
  4586.6  185.48  4591.9  185.45  4606.6  185.38  4646.6  184.18  4686.6  183.68
  4771.2   180.8  4771.8  180.78  4820.1  180.74  4821.6  180.75  4869.9  180.98
    4870  180.98  4917.4  180.63  4922.4  180.59 4949.71  177.99 4949.79  177.98
  4949.9  177.97    4950  177.96 4950.11  177.95    4975  175.58  4975.1  175.57
    4984  176.28  4987.8  174.09  4991.7  171.85    4998  171.42  5007.8  172.34
  5012.1  174.05  5014.9  174.53  5017.8  175.02  5022.1  174.01  5022.2  173.99
  5046.7  175.71 5078.59  177.09 5078.69  177.09  5078.8   177.1  5078.9   177.1
 5079.01  177.11  5087.9  177.49  5119.2  177.47  5140.3  177.45  5169.8  177.48
    5197  177.51  5220.6  177.87  5247.8  178.28  5249.6  178.31  5269.7  178.28
  5371.9  178.13  5406.6  178.08  5431.9  178.29  5466.6  178.58  5526.6  180.28
  5546.6  181.28  5551.9  181.73  5586.6  184.68  5631.9  186.38  5666.6  187.68
  5706.6  189.68  5726.6  191.08  5766.6  194.58  5771.9  194.87  5866.6  200.08
  5896.6  200.66  6006.6  202.78  6018.3  203.48
BR D #Mann= 7
  1545.1     .15  3335.1     .14  4423.9     .15    4984    .075  5017.8     .15
  5247.8     .15  5896.6      .2
BR D Banks=4984,5017.8
BC Design=,, 0 ,, 0 ,,,,,,
BC HTab HWMax=203.13