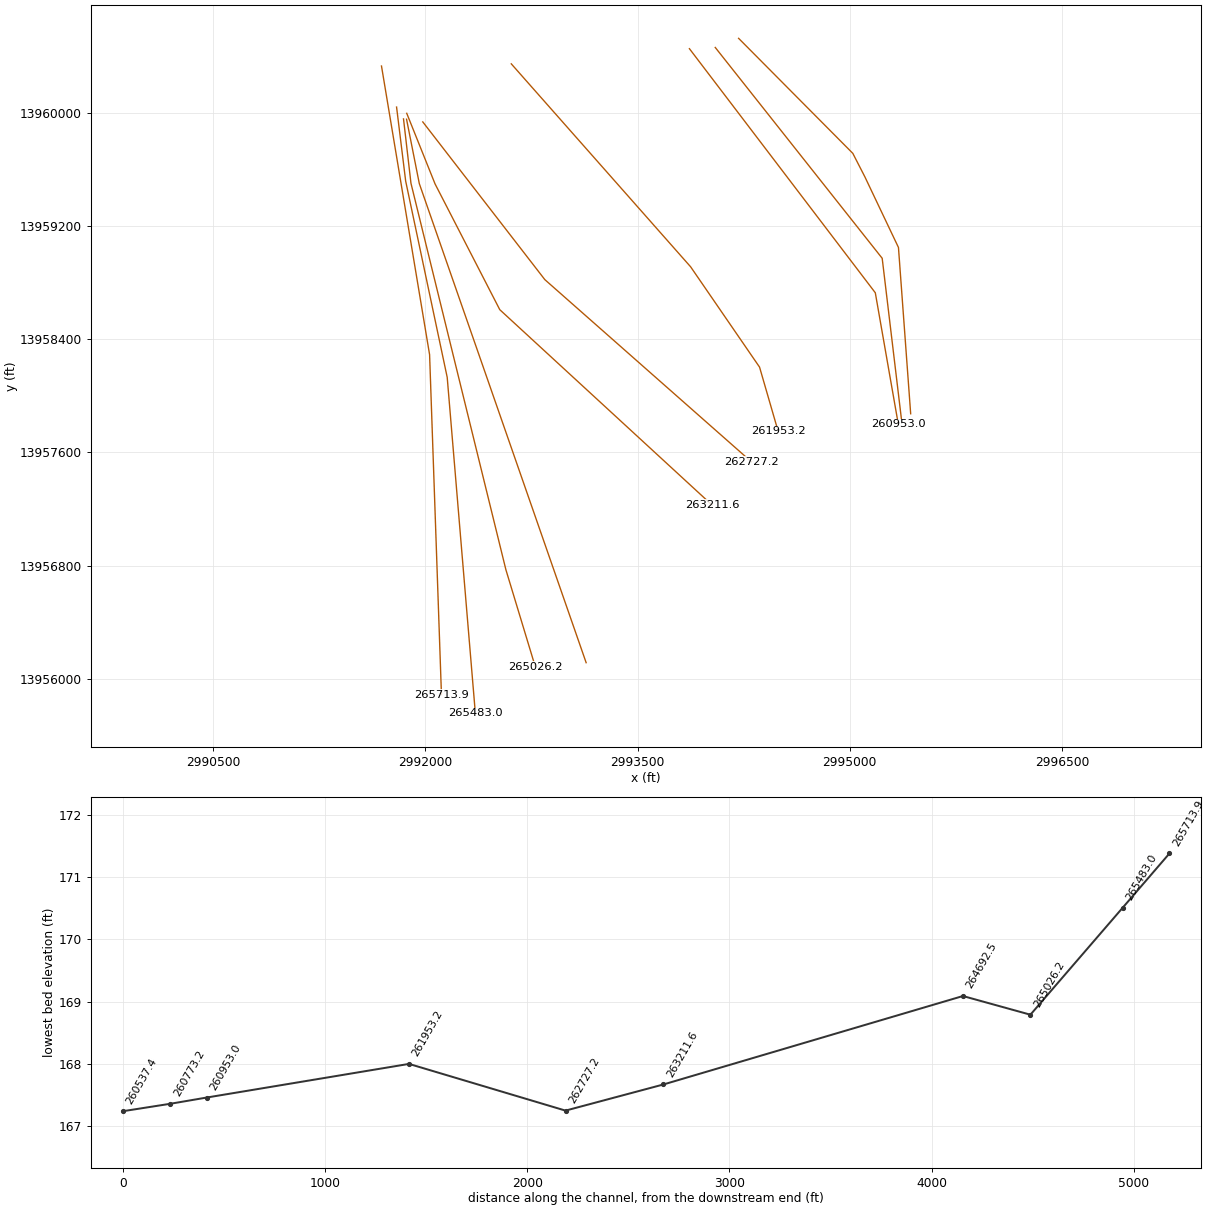
HEC-RAS study J100-00-00.prj: J100-00-00

--- J100-00-00.g01 (geometry) --- (continued)

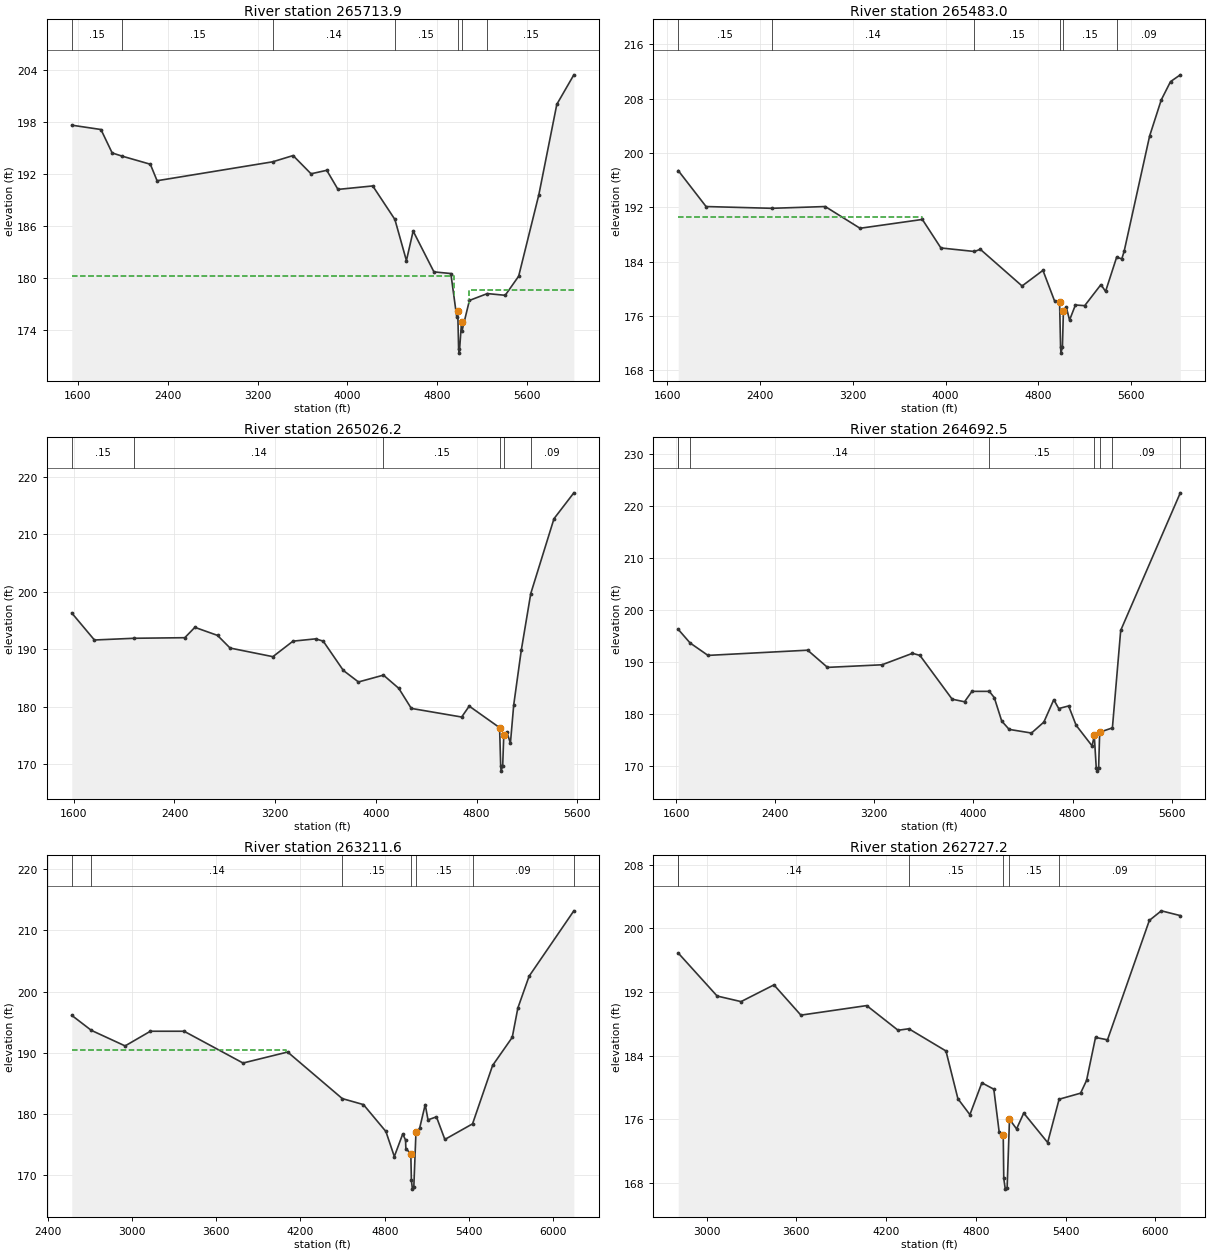
Type RM Length L Ch R = 1 ,265713.9,230.85,230.85,230.85
BEGIN DESCRIPTION:
Downstream Section of Roberts Cemetary
END DESCRIPTION:
XS GIS Cut Line= 3
    2991689.7866   13960331.9868    2992029.9272   13958291.1428
    2992113.7618   13955887.8853
#Sta/Elev= 30
  1545.1  197.64  1805.1  197.14  1905.1  194.44  1996.9  194.06  2245.1  193.14
  2305.1  191.24  3335.1  193.42  3516.9  194.14  3676.9  192.04  3816.9  192.44
  3916.9  190.24  4226.6  190.64  4423.9  186.78  4526.6  182.04  4586.6  185.44
  4771.8  180.74  4922.4  180.55  4975.1  175.53    4984  176.24  4991.7  171.81
    4998  171.38  5017.8  174.98  5022.2  173.95  5087.9  177.45  5247.8  178.24
  5406.6  178.04  5526.6  180.24  5706.6  189.64  5866.6  200.04  6018.3  203.44
#Mann= 7 ,-1 , 0
  1545.1     .15       0  1996.9     .15       0  3335.1     .14       0
  4423.9     .15       0    4984     .08       0  5017.8     .15       0
  5247.8     .15       0
#XS Ineff= 2 , 0
       0    4950   180.3    5080       0   178.6
Permanent Ineff=
       F       F
Bank Sta=4984,5017.8
XS Rating Curve= 0
Exp/Cntr=.5,.3

Type RM Length L Ch R = 1 ,265483.0,76.6,456.8,385.13
BEGIN DESCRIPTION:
Cross Section XS200
Ineffective at Sta 3800 based on topo upstream of the cross section
END DESCRIPTION:
XS GIS Cut Line= 4
    2991796.4447   13960041.7017    2991860.8734   13959517.9038
     2992154.365   13958131.4092    2992353.4926   13955755.1525
#Sta/Elev= 30
  1695.1   197.4  1935.1   192.1  2502.6  191.84  2962.8   192.1  3262.8   188.9
  3800.1   190.2  3960.1     186  4249.3  185.48  4300.1   185.8  4660.1   180.4
  4840.1   182.7  4940.1   178.2  4983.5  178.07  4992.1  171.42  4995.4  170.51
    5008  171.41  5016.6  176.76  5041.2  177.31  5069.4  175.37  5120.1   177.6
  5200.1   177.5  5340.1   180.6  5380.1   179.6  5475.5  184.63  5520.1   184.4
  5540.1   185.5  5760.1   202.5  5860.1   207.8  5940.1   210.5  6024.6   211.5
#Mann= 6 ,-1 , 0
  1695.1     .15       0  2502.6     .14       0  4249.3     .15       0
  4983.5     .08       0  5016.6     .15       0  5475.5     .09       0
#XS Ineff= 2 , 0
       0    3800   190.5               0
Permanent Ineff=
       F       F
Bank Sta=4983.5,5016.6
XS Rating Curve= 0
Exp/Cntr=.3,.1

Type RM Length L Ch R = 1 ,265026.2,164.7,333.7,337.51
BEGIN DESCRIPTION:
Cross Section XS199.5
Ineffective at Sta 3600 based on topo upstream of the cross section
END DESCRIPTION:
XS GIS Cut Line= 4
    2991845.5319   13959957.9747    2991898.1768   13959502.9782
    2992569.3757   13956770.6638    2992777.5489   13956083.6923
#Sta/Elev= 30
    1584   196.3    1764   191.6  2078.4   191.9    2482     192    2562   193.8
    2742   192.4    2842   190.2    3182   188.7    3342   191.4    3522   191.8
    3582   191.4    3742   186.3    3862   184.3  4060.6  185.49    4182   183.2
    4282   179.7    4682   178.2    4742   180.1  4983.5  176.35  4992.1   169.7
  4995.4  168.79    5008  169.69  5016.6  175.04  5041.2  175.59  5069.4  173.65
  5095.6   180.3  5155.6   189.8  5231.1  199.68  5415.6   212.7  5573.4   217.2
#Mann= 6 ,-1 , 0
    1584     .15       0  2078.4     .14       0  4060.6     .15       0
  4983.5     .08       0  5016.6     .15       0  5231.1     .09       0
#XS Ineff= 2 , 0
       0    3600   190.5               0
Permanent Ineff=
       F       F
Bank Sta=4983.5,5016.6
XS Rating Curve= 0
Exp/Cntr=.3,.1

Type RM Length L Ch R = 1 ,264692.5,232.79,1480.9,1216.02
BEGIN DESCRIPTION:
Cross Section XS199
END DESCRIPTION:
XS GIS Cut Line= 4
    2991867.0336     13959956.02    2991957.1878   13959500.6587
    2992406.5933   13958211.0602     2993136.728   13956113.5823
#Sta/Elev= 30
  1617.8   196.3  1713.3  193.69  1857.8   191.3    2662   192.3    2822     189
    3262   189.5  3507.7   191.7  3567.7   191.3  3827.7   182.9  3927.7   182.4
  3987.7   184.4  4127.6   184.4  4167.7   183.2  4227.7   178.7  4287.7   177.1
  4467.7   176.4  4567.7   178.5  4647.7   182.8  4687.7   181.1  4767.7   181.6
  4827.7   177.9  4956.9  173.93  4974.5  175.93  4990.4  169.71  4999.3  169.09
  5009.6  169.76  5018.1  176.56  5120.7  177.39  5187.7   196.1  5668.6   222.5
#Mann= 8 , 1 , 0
  1617.8      .2       0  1617.8     .15       0  1713.3     .14       0
  4127.6     .15       0  4974.5     .08       0  5018.1     .15       0
  5120.7     .09       0  5668.6      .2       0
Bank Sta=4974.5,5018.1
XS Rating Curve= 0
Exp/Cntr=.3,.1

Type RM Length L Ch R = 1 ,263211.6,361.1,484.4,414.8
BEGIN DESCRIPTION:
Cross Section XS198
Ineffective at Sta 4100 based on topo upstream of the cross section
END DESCRIPTION:
XS GIS Cut Line= 4
      2991868.34    13959997.589    2992068.4454   13959498.6612
    2992526.0699   13958609.3155     2994026.165    13957228.697
#Sta/Elev= 30
  2570.9   196.1  2709.9  193.65  2950.9   191.1  3130.9   193.5  3370.9   193.5
  3790.9   188.3  4108.6   190.1    4498  182.48  4648.6   181.5  4808.6   177.1
  4868.6     173  4928.6   176.7  4948.6   175.7  4950.8  174.28    4986  173.49
  4990.2  169.14  4997.5  167.67  5007.3  167.96  5022.7  176.96  5048.6   177.6
  5088.6   181.5  5108.6     179  5168.6   179.5  5228.6   175.8  5425.8  178.35
  5568.6   187.9  5708.6   192.5  5748.6   197.3  5828.6   202.5  6147.4   213.2
#Mann= 7 ,-1 , 0
  2570.9     .15       0  2709.9     .14       0    4498     .15       0
    4986     .08       0  5022.7     .15       0  5425.8     .09       0
  6147.4      .2       0
#XS Ineff= 2 , 0
       0    4100   190.5               0
Permanent Ineff=
       F       F
Bank Sta=4986,5022.7
XS Rating Curve= 0
Exp/Cntr=.3,.1

Type RM Length L Ch R = 1 ,262727.2,846.44,774,596.38
BEGIN DESCRIPTION:
Cross Section XS197
END DESCRIPTION:
XS GIS Cut Line= 3
    2991981.7877   13959936.8332    2992844.6742   13958821.7183
    2994304.9436   13957534.0262
#Sta/Elev= 30
  2810.7   196.9  3070.7   191.5  3230.7   190.8  3450.7   192.9  3630.7   189.1
  4070.7   190.3  4280.7   187.2  4352.4  187.39  4600.7   184.6  4680.7   178.6
  4760.7   176.6  4840.7   180.6  4920.7   179.8  4956.6  174.41  4983.6   174.1
  4987.2  168.59  4997.4  167.25  5009.5  167.34  5025.5  176.03  5072.8  174.81
  5120.7   176.8  5280.7   173.1  5357.3  178.54  5500.7   179.3  5540.7   180.9
  5600.7   186.3  5680.7     186  5960.7     201  6040.7   202.2  6167.6   201.6
#Mann= 6 , 1 , 0
  2810.7      .2       0  2810.7     .14       0  4352.4     .15       0
  4983.6     .08       0  5025.5     .15       0  5357.3     .09       0
Bank Sta=4983.6,5025.5
XS Rating Curve= 0
Exp/Cntr=.3,.1

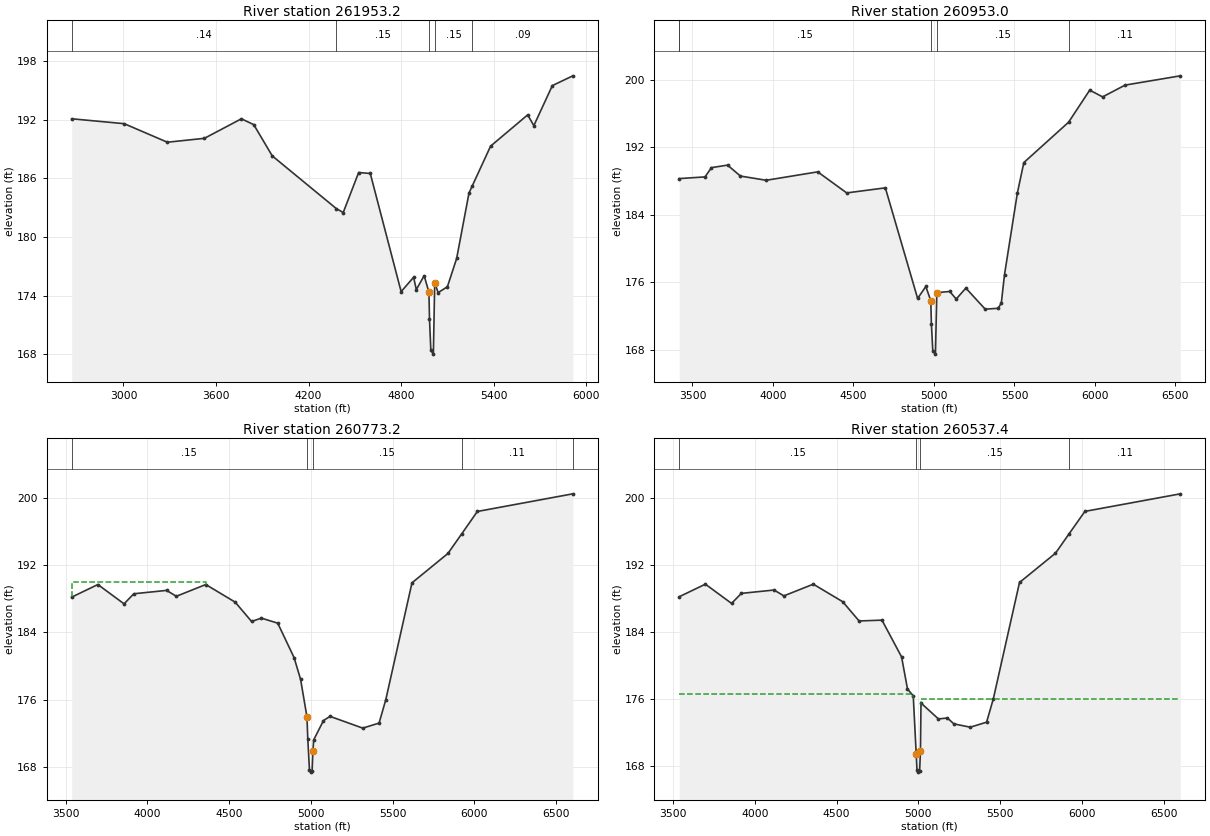
Type RM Length L Ch R = 1 ,261953.2,1009.78,1000.2,984.86
BEGIN DESCRIPTION:
Cross Section XS196 - No topographic relief beyond limits of cross section
END DESCRIPTION:
XS GIS Cut Line= 4
    2992607.3919   13960347.4316    2993875.6208   13958912.1292
    2994362.7625   13958203.1363    2994494.3061   13957748.9961
#Sta/Elev= 30
  2664.8   192.1  3004.8   191.6  3284.8   189.7  3524.8   190.1  3764.8   192.1
  3844.8   191.5  3964.8   188.3  4380.3   182.9  4424.8   182.5  4524.8   186.6
  4600.1   186.5  4800.1   174.4    4881  175.87  4898.5  174.61  4949.5  176.03
  4980.4  174.33    4984  171.61  4992.8  168.38  5009.1     168  5017.8   175.3
  5040.1   174.3  5100.1   174.9  5160.1   177.8  5240.1   184.5  5260.1  185.19
  5380.1   189.3  5620.4   192.5  5660.4   191.4  5780.4   195.5  5913.2   196.5
#Mann= 5 ,-1 , 0
  2664.8     .14       0  4380.3     .15       0  4980.4     .08       0
  5017.8     .15       0  5260.1     .09       0
Bank Sta=4980.4,5017.8
XS Rating Curve= 0
Exp/Cntr=.3,.1

Type RM Length L Ch R = 1 ,260953.0,169.79,179.8,154.04
BEGIN DESCRIPTION:
Cross Section XS195 - No topographic relief beyond limits of cross section
END DESCRIPTION:
XS GIS Cut Line= 3
    2993866.8628   13960454.5651    2995181.1052   13958728.7921
    2995343.5863   13957800.0497
#Sta/Elev= 30
  3418.1   188.3  3578.1   188.5  3618.1   189.6  3718.1   189.9  3798.1   188.6
  3958.1   188.1  4278.1   189.1  4458.1   186.6  4698.1   187.2  4898.5  174.07
  4949.5  175.49  4980.4  173.79    4984  171.07  4992.8  167.84  5009.1  167.46
  5017.8  174.76  5098.1   174.9  5138.1     174  5198.1   175.3  5318.1   172.8
  5398.1   172.9  5418.1   173.5  5438.1   176.9  5518.1   186.6  5558.1   190.2
  5836.3     195  5967.3   198.8  6047.3     198  6187.3   199.4  6530.2   200.5
#Mann= 5 , 1 , 0
  3418.1      .2       0  3418.1     .15       0  4980.4     .08       0
  5017.8     .15       0  5836.3     .11       0
Bank Sta=4980.4,5017.8
XS Rating Curve= 0
Exp/Cntr=.3,.1

Type RM Length L Ch R = 1 ,260773.2,244.5,235.8,163.7
BEGIN DESCRIPTION:
Cross Section XS194.6
Ineffective at Sta 4360 based on topo upstream of the cross section
END DESCRIPTION:
XS GIS Cut Line= 3
    2994049.5442    13960463.124    2995229.7627    13958972.642
    2995368.0296    13957816.972
#Sta/Elev= 30
  3537.6   188.2  3697.6   189.7  3857.6   187.4  3917.6   188.6  4117.6     189
  4177.6   188.3  4357.6   189.7  4537.6   187.6  4637.6   185.3  4697.6   185.7
  4797.6   185.1  4897.6     181  4937.6   178.4  4976.4  173.94  4981.5  171.35
  4991.7  167.63    4999  167.36  5007.9   167.5    5013  169.91  5017.6   171.2
  5077.6   173.5  5117.6     174  5317.6   172.6  5417.6   173.2  5458.8     176
  5618.8   189.9  5838.8   193.4  5922.8  195.73  6018.8   198.4  6602.7   200.5
#Mann= 5 ,-1 , 0
  3537.6     .15       0  4976.4     .08       0    5013     .15       0
  5922.8     .11       0  6602.7      .2       0
#XS Ineff= 2 , 0
       0    4360     190               0
Permanent Ineff=
       F       F
Bank Sta=4976.4,5013
XS Rating Curve= 0
Exp/Cntr=.5,.3

Type RM Length L Ch R = 1 ,260537.4,63,63,63
BEGIN DESCRIPTION:
Upstream Section of Cardinal Road
END DESCRIPTION:
XS GIS Cut Line= 5
    2994214.6796   13960527.7113    2995022.1518   13959714.4299
     2995107.336   13959548.4964    2995344.8043   13959049.2041
    2995431.2052   13957873.4747
#Sta/Elev= 30
  3537.6  188.21  3697.6  189.71  3857.6  187.41  3917.6  188.61  4117.6  189.01
  4177.6  188.31  4357.6  189.71  4537.6  187.61  4637.6  185.31  4777.6  185.41
  4897.6  181.01  4933.7  177.18  4968.9  176.36  4987.2  169.35  4991.7  167.51
    4999  167.24  5007.9  167.38    5013  169.79  5016.3   175.5    5123   173.6
  5177.6  173.71  5217.6  173.01  5317.6  172.61  5417.6  173.21  5458.8  176.01
  5618.8  189.91  5838.8  193.41  5922.5  195.74  6018.8  198.41  6602.7  200.51
#Mann= 4 ,-1 , 0
  3537.6     .15       0  4987.2     .08       0    5013     .15       0
  5922.5     .11       0
#XS Ineff= 2 , 0
       0    4970   176.6    5016       0     176
Permanent Ineff=
       F       F
Bank Sta=4987.2,5013
XS Rating Curve= 0
Exp/Cntr=.5,.3