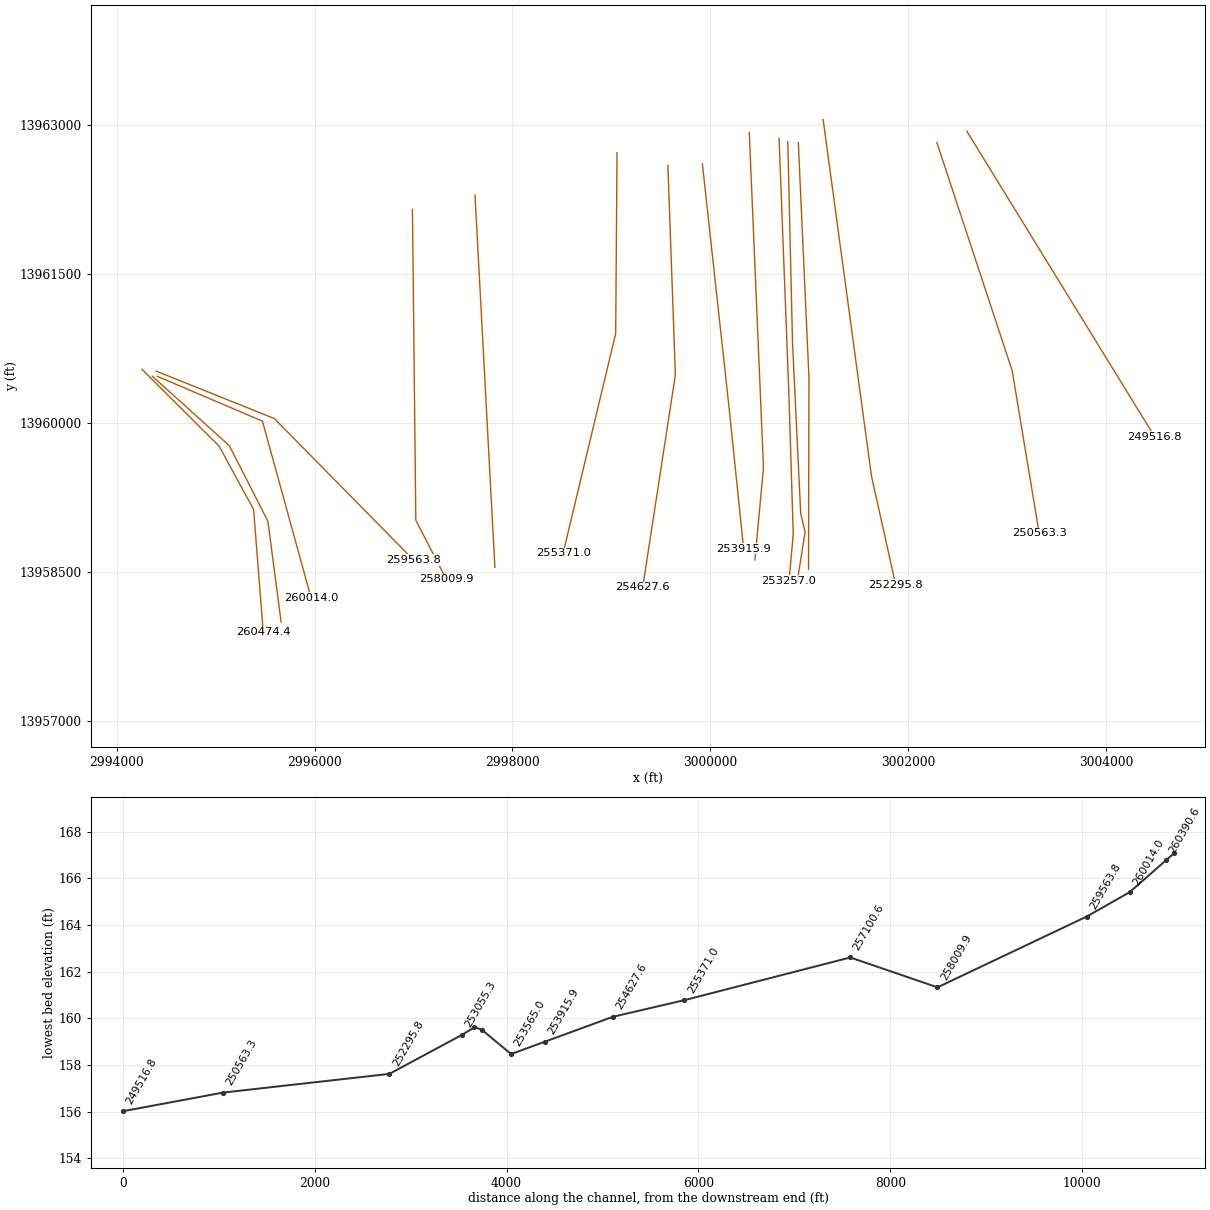
HEC-RAS study J100-00-00.prj: J100-00-00

--- J100-00-00.g01 (geometry) --- (continued)

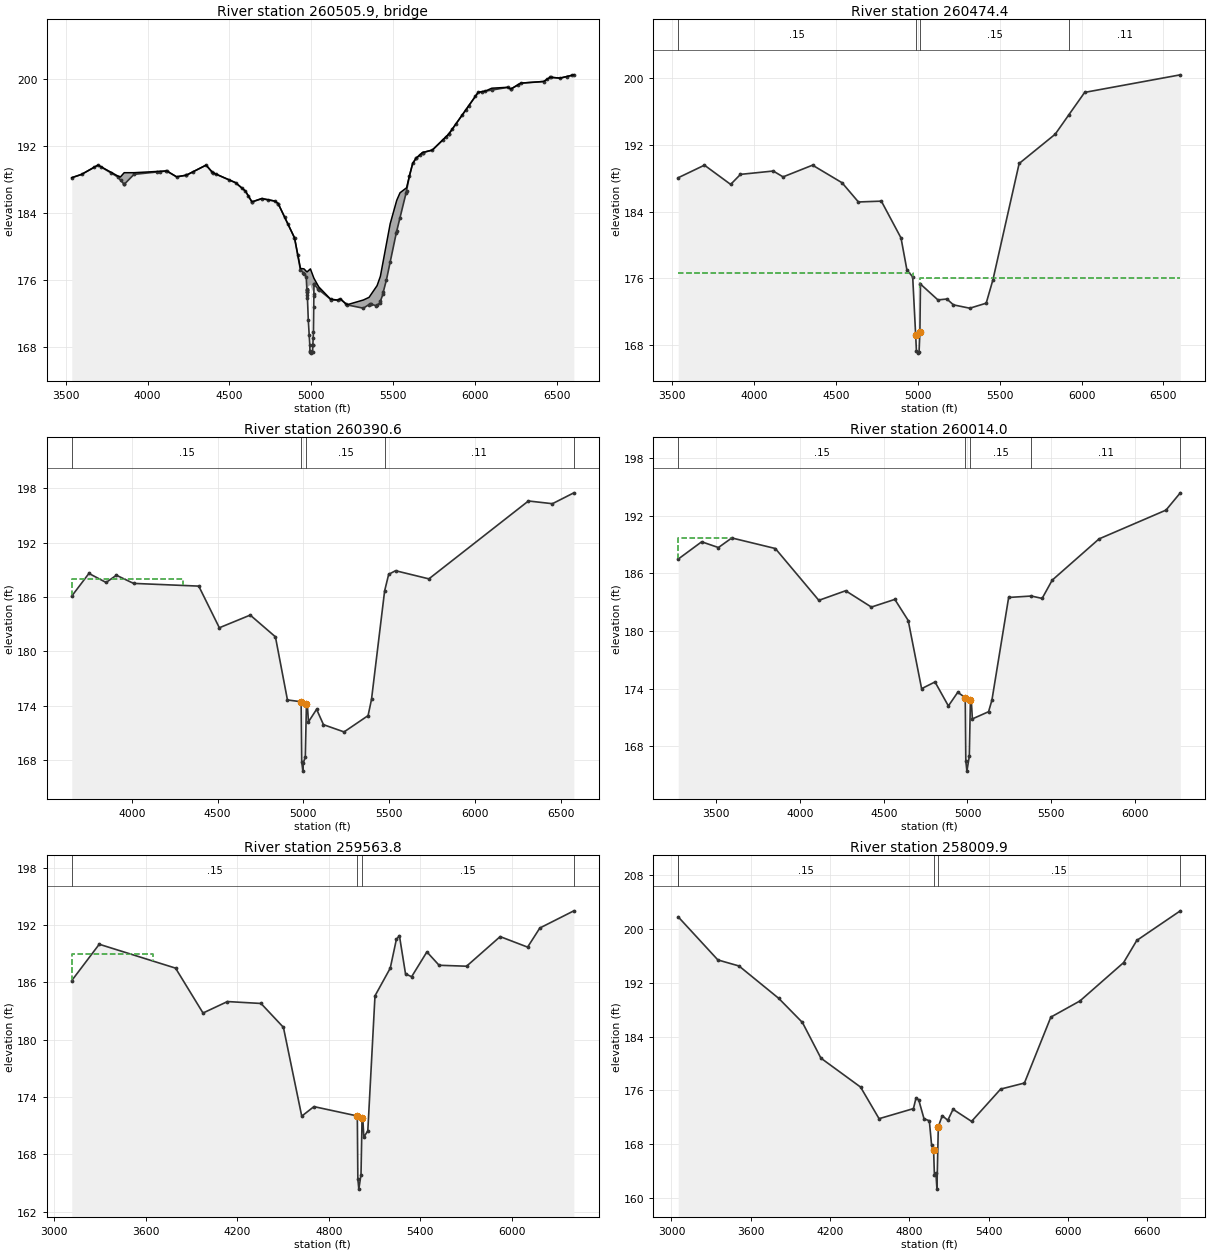
Type RM Length L Ch R = 3 ,260505.9,,,
BEGIN DESCRIPTION:
CARDINAL ROAD
Structure ID: J100-00-00-12 - No topographic relief beyond limits of cross section
No piers
END DESCRIPTION:
Node Name=Cardinal Road
Bridge Culvert--1,0,-1,-1, 0
Deck Dist Width WeirC Skew NumUp NumDn MinLoCord MaxHiCord MaxSubmerge Is_Ogee
10,43,2.6,0, 60, 60, , , .95, 0, 1,1,,
  3537.6  3597.6  3697.6  3817.6  3835.1  3857.6  3917.6  4117.6  4177.6  4237.6
  4357.6  4397.6  4537.6  4597.6  4637.6  4697.6  4777.6  4797.6  4897.6  4933.7
  4955.4  4968.9 4973.71  4973.8  4994.5  5015.6  5016.3  5045.4  5117.8  5160.8
  5177.6  5217.6  5317.6  5352.5  5401.5  5417.6  5421.5  5437.6  5438.8  5458.8
  5481.5  5521.5  5541.5  5581.5  5598.8  5618.8  5638.8  5678.8  5738.8  5838.8
  6018.8  6061.5  6101.5  6198.8  6218.8  6278.8  6418.8  6458.8  6518.8  6602.7
   188.2   188.6  189.71  188.42   188.3   188.8   188.8  189.01  188.31  188.51
  189.71  188.81  187.61  186.61  185.31  185.71  185.41  185.11  181.01  177.36
   177.3  177.02  176.94  176.94   177.3   176.2  176.17  175.15  173.68  173.58
  173.71  173.01  173.58   173.9   175.3  176.19   176.4  178.09  178.22  180.32
   182.7   185.5   186.4     187  188.41  189.91  190.51  191.21  191.51  193.41
  198.41  198.55   198.9  199.01  198.81  199.51  199.71  200.21  200.11   200.5
   188.2   188.6   189.7   188.3  187.91   187.4   188.6     189   188.3   188.5
   189.7   188.8   187.6   186.6   185.3   185.7   185.4   185.1     181  177.17
  176.73  176.35  174.57  175.04   175.4  174.28  175.49  174.82  173.67  173.57
   173.7     173   172.6  173.04  172.96   173.2  173.41   174.3   174.5     176
  178.12  181.82  183.42  186.67   188.4   189.9   190.5   191.2   191.5   193.4
   198.4  198.54  198.68     199   198.8   199.5   199.7   200.2   200.1   200.5
  3537.6  3597.6  3697.6  3817.6  3835.1  3857.6  3917.6  4117.6  4177.6  4237.6
  4357.6  4397.6  4537.6  4597.6  4637.6  4697.6  4777.6  4797.6  4897.6  4933.7
  4955.4  4968.9 4973.71  4973.8  4994.5  5015.6  5016.3  5045.4  5117.8  5160.8
  5177.6  5217.6  5317.6  5352.5  5401.5  5417.6  5421.5  5437.6  5438.8  5458.8
  5481.5  5521.5  5541.5  5581.5  5598.8  5618.8  5638.8  5678.8  5738.8  5838.8
  6018.8  6061.5  6101.5  6198.8  6218.8  6278.8  6418.8  6458.8  6518.8  6602.7
   188.2   188.6  189.71  188.42   188.3   188.8   188.8  189.01  188.31  188.51
  189.71  188.81  187.61  186.61  185.31  185.71  185.41  185.11  181.01  177.36
   177.3  177.02  176.94  176.94   177.3   176.2  176.17  175.15  173.68  173.58
  173.71  173.01  173.58   173.9   175.3  176.19   176.4  178.09  178.22  180.32
   182.7   185.5   186.4     187  188.41  189.91  190.51  191.21  191.51  193.41
  198.41  198.55   198.9  199.01  198.81  199.51  199.71  200.21  200.11   200.5
  188.08  188.48  189.58  188.18  187.79  187.28  188.48  188.88  188.18  188.38
  189.58  188.68  187.48  186.48  185.18  185.58  185.28  184.98  180.88  177.05
  176.61  176.23  174.45  174.92  175.28  174.16  175.37   174.7  173.55  173.45
  173.58  172.88  172.48  172.92  172.84  173.08  173.29  174.18  174.38  175.88
     178   181.7   183.3  186.55  188.28  189.78  190.38  191.08  191.38  193.28
  198.28  198.42  198.56  198.88  198.68  199.38  199.58  200.08  199.98  200.38
Abutment Skew #Up #Dn= , 2 , 2
  4973.6  4975.1
  175.04  174.18
  4973.6  4975.1
  174.92  174.06
Abutment Skew #Up #Dn= , 2 , 2
  5011.4 5015.69
  169.08   174.3
  5011.4 5015.69
  168.96  174.18
BR Coef= 1 , 1 , 0 ,1.25, 0 ,,,.8,0,2,0,
WSPro=,,,, 1 ,,,, 0 ,,,, 0 ,,,,-1 ,-1 ,-1 , 0 , 0 , 0 , 0 , 0
BR U #Sta/Elev= 127
  3537.6   188.2  3597.6   188.6  3675.1  189.45  3697.6   189.7  3715.1   189.5
  3775.1   188.8  3817.6   188.3  3835.1  187.91  3855.1  187.46  3857.6   187.4
  3917.6   188.6  4055.1  188.88  4075.1  188.92  4115.1     189  4117.6     189
  4177.6   188.3  4235.1  188.49  4237.6   188.5  4275.1  188.88  4357.6   189.7
  4395.1  188.86  4397.6   188.8  4415.1  188.65  4495.1  187.96  4537.6   187.6
  4575.1  186.98  4597.6   186.6  4615.1  186.03  4637.3  185.31  4637.6   185.3
  4697.6   185.7  4737.3  185.55  4777.6   185.4  4797.3   185.1  4797.6   185.1
  4837.3  183.47  4857.3  182.65  4897.3  181.01  4897.6     181  4917.3  178.91
  4933.7  177.17  4952.1  176.82  4955.4  176.73  4968.9  176.35  4972.8  174.86
    4973  174.78  4973.1  174.74 4973.71  174.57  4973.8  174.54  4975.1  174.18
  4976.4  173.81  4981.5  171.22  4987.2  169.34  4990.7  168.22  4991.7   167.5
  4994.5   167.4    4999  167.23  5007.9  167.37  5009.3  168.25  5009.4  168.21
  5011.4  169.08    5013  169.78  5014.7  172.72 5015.49  174.09  5015.6  174.28
  5016.3  175.49  5016.7  175.48    5042  174.87  5045.4  174.82  5117.8  173.67
    5123  173.59  5160.8  173.57  5177.6   173.7  5212.5  173.09  5217.6     173
  5317.6   172.6  5352.5  173.04  5357.6   173.1  5361.5  173.08  5397.6   172.9
  5401.5  172.96  5417.6   173.2  5421.5  173.41  5437.6   174.3  5438.8   174.5
  5458.8     176  5481.5  178.12  5518.8   181.6  5521.5  181.82  5541.5  183.42
  5578.8   186.4  5581.5  186.67  5598.8   188.4  5618.8   189.9  5638.8   190.5
  5641.5  190.55  5661.5   190.9  5678.8   191.2  5681.5  191.21  5738.8   191.5
  5801.5  192.69  5821.5  193.07  5838.8   193.4  5841.5  193.48  5861.5  194.03
  5881.5  194.59  5922.5  195.73  5941.5  196.25  5961.5  196.81  6001.5  197.92
  6018.8   198.4  6041.5  198.48  6061.5  198.54  6101.5  198.68  6198.8     199
  6218.8   198.8  6221.5  198.83  6261.5   199.3  6278.8   199.5  6418.8   199.7
  6441.5  199.98  6458.8   200.2  6461.5   200.2  6518.8   200.1  6561.5   200.3
  6593.1  200.45  6602.7   200.5
BR U #Mann= 5
  3537.6     .15  4987.2    .075    5013     .15  5922.5     .11  6593.1      .2
BR U Banks=4987.2,5013
BR D #Sta/Elev= 127
  3537.6  188.08  3597.6  188.48  3675.1  189.33  3697.6  189.58  3715.1  189.38
  3775.1  188.68  3817.6  188.18  3835.1  187.79  3855.1  187.34  3857.6  187.28
  3917.6  188.48  4055.1  188.76  4075.1   188.8  4115.1  188.88  4117.6  188.88
  4177.6  188.18  4235.1  188.37  4237.6  188.38  4275.1  188.76  4357.6  189.58
  4395.1  188.74  4397.6  188.68  4415.1  188.53  4495.1  187.84  4537.6  187.48
  4575.1  186.86  4597.6  186.48  4615.1  185.91  4637.3  185.19  4637.6  185.18
  4697.6  185.58  4737.3  185.43  4777.6  185.28  4797.3  184.98  4797.6  184.98
  4837.3  183.35  4857.3  182.53  4897.3  180.89  4897.6  180.88  4917.3  178.79
  4933.7  177.05  4952.1   176.7  4955.4  176.61  4968.9  176.23  4972.8  174.74
    4973  174.66  4973.1  174.62 4973.71  174.45  4973.8  174.42  4975.1  174.06
  4976.4  173.69  4981.5   171.1  4987.2  169.22  4990.7   168.1  4991.7  167.38
  4994.5  167.28    4999  167.11  5007.9  167.25  5009.3  168.13  5009.4  168.09
  5011.4  168.96    5013  169.66  5014.7   172.6 5015.49  173.97  5015.6  174.16
  5016.3  175.37  5016.7  175.36    5042  174.75  5045.4   174.7  5117.8  173.55
    5123  173.47  5160.8  173.45  5177.6  173.58  5212.5  172.97  5217.6  172.88
  5317.6  172.48  5352.5  172.92  5357.6  172.98  5361.5  172.96  5397.6  172.78
  5401.5  172.84  5417.6  173.08  5421.5  173.29  5437.6  174.18  5438.8  174.38
  5458.8  175.88  5481.5     178  5518.8  181.48  5521.5   181.7  5541.5   183.3
  5578.8  186.28  5581.5  186.55  5598.8  188.28  5618.8  189.78  5638.8  190.38
  5641.5  190.43  5661.5  190.78  5678.8  191.08  5681.5  191.09  5738.8  191.38
  5801.5  192.57  5821.5  192.95  5838.8  193.28  5841.5  193.36  5861.5  193.91
  5881.5  194.47  5922.5  195.61  5941.5  196.13  5961.5  196.69  6001.5   197.8
  6018.8  198.28  6041.5  198.36  6061.5  198.42  6101.5  198.56  6198.8  198.88
  6218.8  198.68  6221.5  198.71  6261.5  199.18  6278.8  199.38  6418.8  199.58
  6441.5  199.86  6458.8  200.08  6461.5  200.08  6518.8  199.98  6561.5  200.18
  6593.1  200.33  6602.7  200.38
BR D #Mann= 5
  3537.6     .15  4987.2    .075    5013     .15  5922.5     .11  6593.1      .2
BR D Banks=4987.2,5013
BC Design=,, 0 ,, 0 ,,,,,,
BC HTab HWMax=200.51

Type RM Length L Ch R = 1 ,260474.4,83.8,83.8,83.8
BEGIN DESCRIPTION:
Downstream Section of Cardinal Road
END DESCRIPTION:
XS GIS Cut Line= 5
    2994254.9617   13960539.0967    2995035.8647   13959764.0652
    2995215.1608   13959434.5332    2995383.4614    13959128.736
    2995481.1144   13957892.0347
#Sta/Elev= 30
  3537.6  188.04  3697.6  189.54  3857.6  187.24  3917.6  188.44  4117.6  188.84
  4177.6  188.14  4357.6  189.54  4537.6  187.44  4637.6  185.14  4777.6  185.24
  4897.6  180.84  4933.7  177.01  4968.9  176.19  4987.2  169.18  4991.7  167.34
    4999  167.07  5007.9  167.21    5013  169.62  5016.3  175.33    5123  173.43
  5177.6  173.54  5217.6  172.84  5317.6  172.44  5417.6  173.04  5458.8  175.84
  5618.8  189.74  5838.8  193.24  5922.5  195.57  6018.8  198.24  6602.7  200.34
#Mann= 4 ,-1 , 0
  3537.6     .15       0  4987.2     .08       0    5013     .15       0
  5922.5     .11       0
#XS Ineff= 2 , 0
       0    4970   176.6    5016       0     176
Permanent Ineff=
       F       F
Bank Sta=4987.2,5013
XS Rating Curve= 0
Exp/Cntr=.5,.3

Type RM Length L Ch R = 1 ,260390.6,343.08,376.6,253.85
BEGIN DESCRIPTION:
Cross Section XS194.5 - No topographic relief beyond limits of cross section
Ineffective at Sta 4300 based on topo upstream of the cross section
END DESCRIPTION:
XS GIS Cut Line= 4
    2994359.8078   13960469.2076    2995138.5087   13959769.5936
    2995527.8591   13959009.1436    2995661.6983   13957993.1823
#Sta/Elev= 30
  3650.1   186.1  3750.1   188.6  3850.1   187.6  3910.1   188.4  4010.1   187.5
  4390.1   187.2  4510.1   182.6  4690.1     184  4836.9   181.6    4907  174.63
  4986.8  174.43  4990.2  167.83  4996.7  166.77  4998.7  167.66    5011   168.3
  5017.7  174.18    5023  174.08  5029.4  172.21  5076.9   173.6  5116.9   171.9
  5236.9   171.1  5376.9   172.9  5396.9   174.7  5473.3  186.67  5496.9   188.5
  5536.9   188.9  5731.3     188  6311.3   196.6  6451.3   196.3    6576   197.5
#Mann= 5 ,-1 , 0
  3650.1     .15       0  4986.8     .08       0  5017.7     .15       0
  5473.3     .11       0    6576      .2       0
#XS Ineff= 2 , 0
       0    4300     188               0
Permanent Ineff=
       F       F
Bank Sta=4986.8,5017.7
XS Rating Curve= 0
Exp/Cntr=.3,.1

Type RM Length L Ch R = 1 ,260014.0,78.08,450.2,492.08
BEGIN DESCRIPTION:
Cross Section XS194 - No topographic relief beyond limits of cross section
END DESCRIPTION:
XS GIS Cut Line= 3
     2994411.145   13960467.8402    2995473.1591   13960016.4842
    2995964.3407   13958237.6106
#Sta/Elev= 30
  3272.2   187.5  3412.2   189.3  3512.2   188.7  3592.2   189.7  3852.2   188.6
  4112.2   183.2  4272.2   184.2  4426.1   182.5  4566.1   183.3  4646.1   181.1
  4726.1     174  4806.1   174.7  4886.1   172.2    4942  173.62  4986.8  173.07
  4990.2  166.47  4996.7  165.41    5011  166.94  5017.7  172.82    5023  172.72
  5029.4  170.85  5126.1   171.6  5146.1   172.8  5246.1   183.5  5381.7  183.65
  5446.1   183.4  5506.1   185.3  5786.1   189.6  6186.1   192.6  6271.6   194.4
#Mann= 5 ,-1 , 0
  3272.2     .15       0  4986.8     .08       0  5017.7     .15       0
  5381.7     .11       0  6271.6      .2       0
#XS Ineff= 2 , 0
       0    3592   189.7               0
Permanent Ineff=
       F       F
Bank Sta=4986.8,5017.7
XS Rating Curve= 0
Exp/Cntr=.3,.1

Type RM Length L Ch R = 1 ,259563.8,1865.2,1553.9,1140.88
BEGIN DESCRIPTION:
Cross Section XS193 - No topographic relief beyond limits of cross section
Ineffective at Sta 3650 based on topo upstream of the cross section
END DESCRIPTION:
XS GIS Cut Line= 3
    2994397.8698    13960520.941    2995592.6357   13960043.0346
    2997000.4571    13958618.389
#Sta/Elev= 30
  3115.8   186.2  3295.8     190  3795.8   187.5  3975.8   182.8  4135.8     184
  4355.8   183.8  4502.6   181.3  4622.6     172  4702.6     173  4986.8  172.02
  4990.2  165.42  4996.7  164.36    5011  165.89  5017.7  171.77    5023  171.67
  5029.4   169.8  5055.6  170.47  5102.6   184.6  5202.6   187.5  5242.6   190.5
  5262.6   190.9  5302.6   186.9  5342.6   186.6  5442.6   189.2  5522.6   187.8
  5702.6   187.7  5922.6   190.8  6102.6   189.7  6182.6   191.7  6405.5   193.5
#Mann= 4 ,-1 , 0
  3115.8     .15       0  4986.8     .08       0  5017.7     .15       0
  6405.5      .2       0
#XS Ineff= 2 , 0
       0    3650     189               0
Permanent Ineff=
       F       F
Bank Sta=4986.8,5017.7
XS Rating Curve= 0
Exp/Cntr=.3,.1

Type RM Length L Ch R = 1 ,258009.9,696.36,909.3,769.65
BEGIN DESCRIPTION:
Cross Section XS192
END DESCRIPTION:
XS GIS Cut Line= 3
    2996989.0326   13962148.5845    2997023.3063   13959018.2493
      2997331.77   13958424.1711
#Sta/Elev= 30
  3051.5   201.8  3351.5   195.4  3511.5   194.5  3811.5   189.7  3991.5   186.1
  4131.5   180.8  4431.5   176.5  4571.5   171.8  4831.5   173.3  4851.5   174.9
  4871.5   174.6  4911.5   171.8  4951.8  171.49  4969.2  167.83  4984.2  167.13
  4990.4  163.39  5001.7  163.71  5009.5  161.33  5019.8  170.62  5049.7  172.25
  5091.8  171.56  5131.5   173.2  5271.5   171.4  5491.5   176.2  5671.5   177.1
  5871.5   186.9  6091.5   189.3    6422     195    6522   198.3  6851.4   202.7
#Mann= 5 , 1 , 0
  3051.5      .2       0  3051.5     .15       0  4984.2     .08       0
  5019.8     .15       0  6851.4      .2       0
Bank Sta=4984.2,5019.8
XS Rating Curve= 0
Exp/Cntr=.3,.1

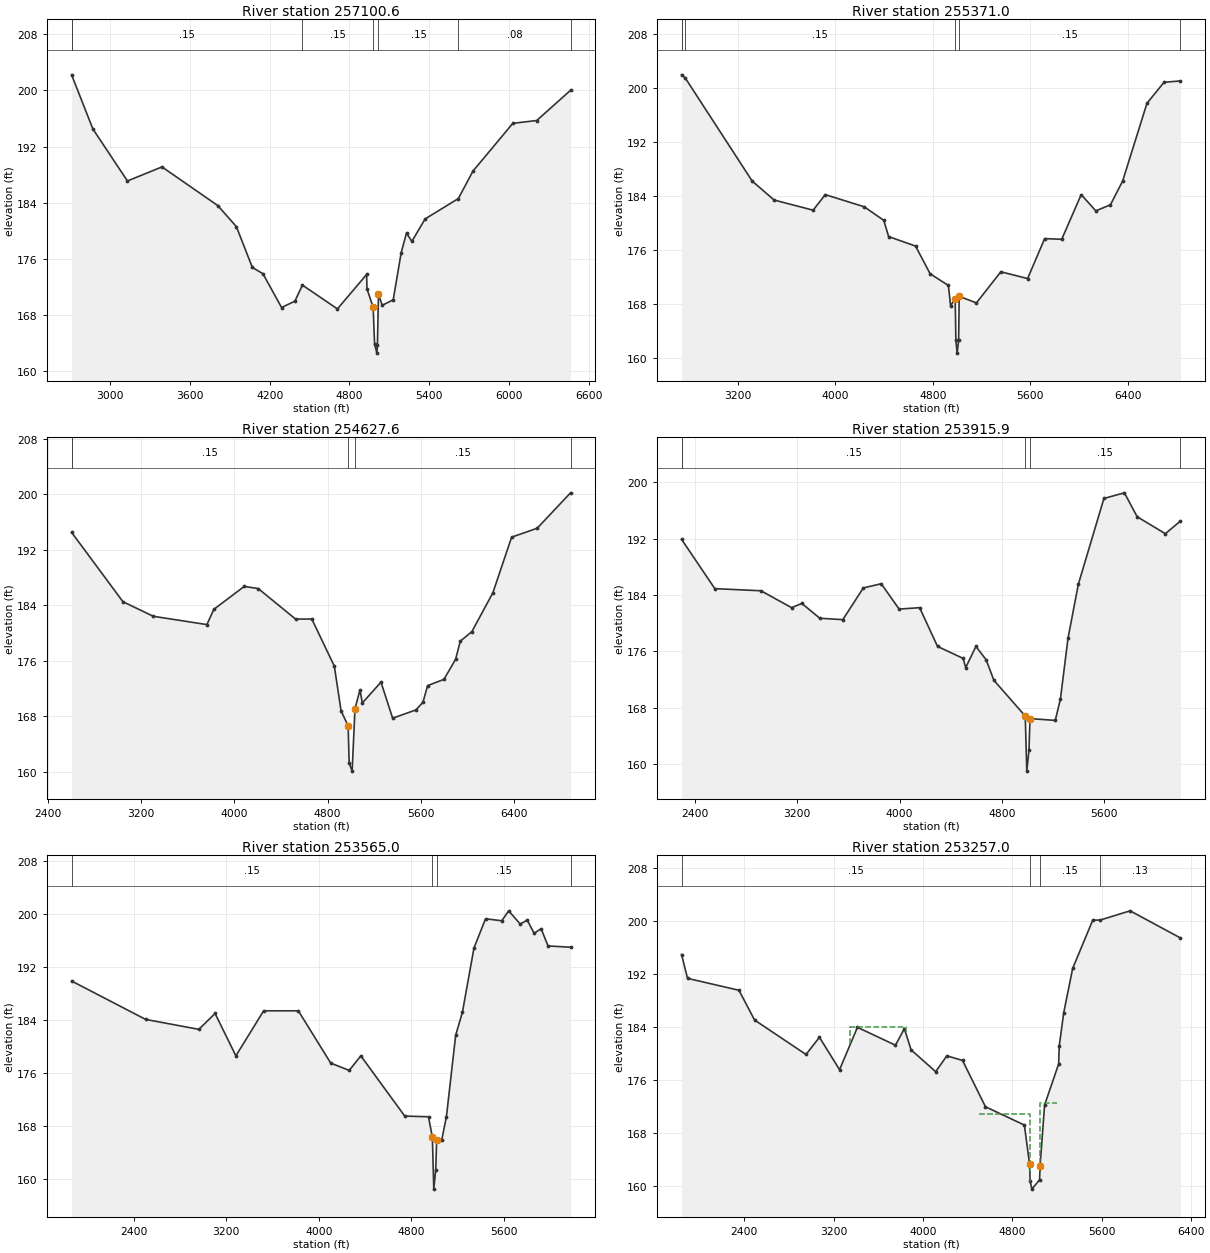
Type RM Length L Ch R = 1 ,257100.6,1384.78,1729.6,1102.29
BEGIN DESCRIPTION:
Cross Section XS191
END DESCRIPTION:
XS GIS Cut Line= 2
    2997621.4992   13962292.2361    2997822.5858   13958543.4071
#Sta/Elev= 30
  2709.5   202.2  2869.5   194.5  3129.5   187.1  3389.5   189.1  3809.5   183.6
  3949.5   180.6  4069.5   174.8  4149.5   173.9  4289.5   169.1  4389.5     170
  4446.1  172.29  4709.5   168.9  4929.5   173.8    4932  171.76  4978.5  169.12
  4989.3  163.84  5006.9  162.61  5010.6  163.75  5018.5  170.98  5046.9  169.41
  5129.5   170.2  5189.5   176.9  5229.5   179.7  5269.5   178.5  5369.5   181.7
  5619.6   184.6  5729.5   188.5  6029.5   195.3  6209.5   195.7  6463.7     200
#Mann= 7 , 1 , 0
  2709.5      .2       0  2709.5     .15       0  4446.1     .15       0
  4978.5     .08       0  5018.5     .15       0  5619.6     .08       0
  6463.7      .2       0
Bank Sta=4978.5,5018.5
XS Rating Curve= 0
Exp/Cntr=.3,.1

Type RM Length L Ch R = 1 ,255371.0,622.37,743.4,752.88
BEGIN DESCRIPTION:
Cross Section XS190
END DESCRIPTION:
XS GIS Cut Line= 3
    2999056.8817   13962719.8135    2999043.4688   13960898.9932
    2998512.0256   13958687.0404
#Sta/Elev= 30
  2736.6   201.9  2766.1  201.46  3316.6   186.2  3496.6   183.4  3816.6   181.9
  3916.6   184.2  4236.6   182.4  4396.6   180.4  4436.6     178  4657.5   176.6
  4777.5   172.5  4927.2  170.78  4945.2  167.78    4983  168.81  4988.6  162.67
  4998.9  160.78  5011.4  162.65  5015.8  169.17  5157.5   168.2  5357.5   172.8
  5577.5   171.8  5717.5   177.7  5857.5   177.6  6017.5   184.2  6137.5   181.8
  6257.5   182.7  6357.5   186.2  6557.5   197.7  6697.5   200.8  6832.4     201
#Mann= 6 , 1 , 0
  2736.6      .2       0  2736.6      .1       0  2766.1     .15       0
    4983     .08       0  5015.8     .15       0  6832.4      .2       0
Bank Sta=4983,5015.8
XS Rating Curve= 0
Exp/Cntr=.3,.1

Type RM Length L Ch R = 1 ,254627.6,493.32,711.7,771.27
BEGIN DESCRIPTION:
Cross Section XS189
END DESCRIPTION:
Node Name=Limits of FIRM
XS GIS Cut Line= 3
    2999570.9878   13962594.1431    2999646.7287   13960482.4566
    2999316.3721   13958342.3205
#Sta/Elev= 30
    2605   194.5    3045   184.5    3305   182.4    3765   181.2    3825   183.4
    4085   186.7    4205   186.4    4525     182    4665     182    4858   175.2
  4915.7  168.77  4976.2  166.58  4985.4   161.2  5010.6  160.07  5035.1  169.06
    5078   171.8    5098   169.9    5258   172.9    5358   167.7    5558   168.9
    5618     170    5658   172.4    5798   173.3    5898   176.2    5938   178.8
    6038   180.2    6218   185.8    6378   193.8    6598   195.1  6883.5   200.2
#Mann= 5 , 1 , 0
    2605      .2       0    2605     .15       0  4976.2     .08       0
  5035.1     .15       0  6883.5      .2       0
Bank Sta=4976.2,5035.1
XS Rating Curve= 0
Exp/Cntr=.3,.1

Type RM Length L Ch R = 1 ,253915.9,381.31,350.9,275.14
BEGIN DESCRIPTION:
Cross Section XS188
END DESCRIPTION:
XS GIS Cut Line= 3
    2999919.6319   13962608.2294    3000192.5352   13960123.3734
    3000336.4348   13958732.6348
#Sta/Elev= 30
  2296.5   191.9  2556.5   184.9  2916.5   184.6  3156.5   182.2  3236.5   182.8
  3376.5   180.7  3556.5   180.5  3716.5     185  3856.5   185.6  3996.5     182
  4156.5   182.2  4296.5   176.7  4496.5     175  4516.5   173.7  4596.5   176.7
  4676.5   174.8  4736.5   171.9  4981.7  166.82  4993.8     159  5010.8  161.95
  5018.8  166.46  5216.3   166.2  5256.3   169.2  5316.3   177.9  5396.3   185.5
  5596.3   197.7  5756.3   198.5  5856.3   195.1  6076.3   192.7  6194.5   194.5
#Mann= 5 , 1 , 0
  2296.5      .2       0  2296.5     .15       0  4981.7     .08       0
  5018.8     .15       0  6194.5      .2       0
Bank Sta=4981.7,5018.8
XS Rating Curve= 0
Exp/Cntr=.3,.1

Type RM Length L Ch R = 1 ,253565.0,168.53,308,145.49
BEGIN DESCRIPTION:
Cross Section XS187
END DESCRIPTION:
XS GIS Cut Line= 3
    3000393.6218   13962924.2226    3000537.2551   13959548.8402
    3000450.6806    13958618.389
#Sta/Elev= 30
    1863   189.9  2503.1   184.1  2963.1   182.6  3103.1     185  3283.1   178.6
  3523.1   185.4  3823.1   185.4  4103.1   177.5  4263.1   176.4  4363.1   178.6
  4743.1   169.5  4948.2   169.4  4981.7  166.29  4993.8  158.47  5010.8  161.42
  5018.8  165.93  5062.3  165.89  5103.1   169.4  5183.1   181.7  5241.5   185.2
  5341.5   194.9  5441.5   199.3  5581.5     199  5641.5   200.5  5741.5   198.5
  5801.5   199.1  5861.5   197.1  5921.5   197.8  5981.5   195.2    6176     195
#Mann= 4 ,-1 , 0
    1863     .15       0  4981.7     .08       0  5018.8     .15       0
    6176      .2       0
Bank Sta=4981.7,5018.8
XS Rating Curve= 0
Exp/Cntr=.5,.3

Type RM Length L Ch R = 1 ,253257.0,74,74,74
BEGIN DESCRIPTION:
Upstream Section of Sanders Cemetery Rd (Mueschke)
Ineffective at Sta 3350 based on topo upstream of the cross section
END DESCRIPTION:
XS GIS Cut Line= 4
    3000694.7119   13962866.6504    3000794.8827   13960269.8902
    3000837.9727   13958876.6472    3000795.4266   13958408.1056
#Sta/Elev= 30
  1839.5  194.96    1893  191.36    2353  189.56    2493  185.06    2953  179.86
    3073  182.46    3253  177.56    3413  183.96    3753  181.26    3833  183.76
    3893  180.56    4113  177.26    4213  179.66    4353  178.96  4558.4  171.96
  4906.4   169.2  4952.8   163.3  4957.4   160.8    4973  159.52  5042.2  160.93
  5047.2  163.06  5087.3  172.23  5213.1  178.43  5218.4  181.16  5258.4  186.16
  5338.4  192.86  5518.4  200.16  5583.2  200.16  5852.3  201.56  6302.8  197.46
#Mann= 4 ,-1 , 0
  1839.5     .15       0  4952.8     .08       0  5047.2     .15       0
  5583.2     .13       0
#XS Ineff= 3 ,-1
    3350    3850     184    4500    4960   170.9    5045    5200   172.5
Permanent Ineff=
       F       F       F
Bank Sta=4952.8,5047.2
XS Rating Curve= 0
Exp/Cntr=.5,.3

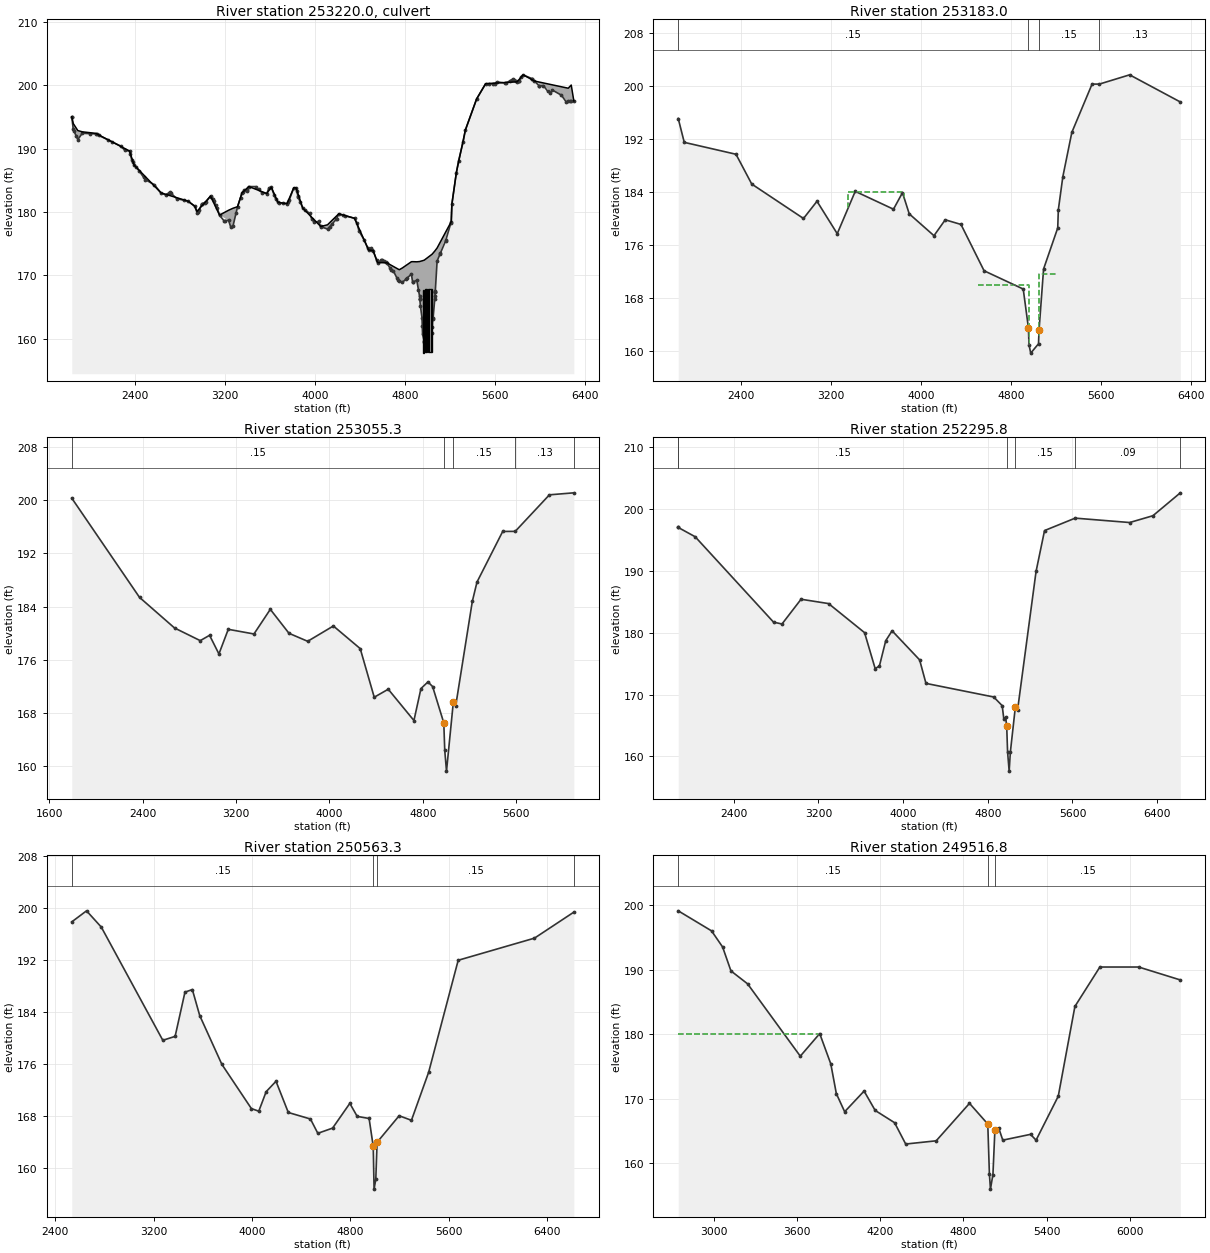
Type RM Length L Ch R = 2 ,253220.0,,,
BEGIN DESCRIPTION:
SANDERS CEMETERY RD. (MUESCHKE)
Structure ID: J100-00-00-11
END DESCRIPTION:
Node Name=Sanders Cemetery
Bridge Culvert--1,0,-1,-1, 0
Deck Dist Width WeirC Skew NumUp NumDn MinLoCord MaxHiCord MaxSubmerge Is_Ogee
10,54,2.6,0, 60, 60, , , .95, 0, 1,1,,
  1839.5    1853    1893    1933    2053    2353    2393    2633    2873    2933
    2953    3073    3153    3233    3253    3273    3313    3353    3413    3573
    3613    3673    3753    3813    3833    3893    4053    4113    4213    4353
  4478.4  4518.4  4558.4  4638.4  4750.7  4778.4  4858.4  4869.9  4906.4  4931.4
  4952.8  4957.4    4973  5042.2  5047.2  5051.5  5066.9  5087.3  5213.1  5218.4
  5258.4  5338.4  5438.4  5518.4  5798.4  5852.3  5952.8  6252.8  6279.6  6302.8
     195  193.93  192.83  192.63  192.39  189.61  187.41  183.01  181.71  180.91
  180.09  182.51  179.51  180.27  180.43  180.59  180.83  183.01  184.01  182.91
  183.91  181.51  181.31  183.81  183.81  180.61  177.71  177.98  179.71  179.01
  174.01  173.91  172.01  172.01   170.9  171.18  172.16  172.17  172.15  172.19
   172.3  172.32  172.41  173.34  173.45  173.53  173.85  174.33  178.48  181.21
  186.21  192.91  197.81  200.21  200.51  201.61  200.63   199.5     200   197.5
     195     193   191.4   192.4   192.3   189.6   187.4     183   181.7   180.9
   179.9   182.5   179.5   178.7   177.6   177.8   180.8     183     184   182.9
   183.9   181.5   181.3   183.8   183.8   180.6   177.7   177.3   179.7     179
     174   173.9     172     172  169.18   168.9   170.2  168.93  169.24  166.73
  163.34  160.84  159.56  160.97   163.1  163.25  166.26  172.27  178.47   181.2
   186.2   192.9   197.8   200.2   200.5   201.6  200.62  197.43  197.47   197.5
  1839.5    1853    1893    1933    2053    2353    2393    2633    2873    2933
    2953    3073    3153    3233    3253    3273    3313    3353    3413    3573
    3613    3673    3753    3813    3833    3893    4053    4113    4213    4353
  4478.4  4518.4  4558.4  4638.4  4750.7  4778.4  4858.4  4869.9  4906.4  4931.4
  4952.8  4957.4    4973  5042.2  5047.2  5051.5  5066.9  5087.3  5213.1  5218.4
  5258.4  5338.4  5438.4  5518.4  5798.4  5852.3  5992.3  6252.8  6279.6  6302.8
  195.08  193.93  192.83  192.63  192.39  189.68  187.48  183.08  181.78  180.98
  180.09  182.58  179.58  180.27  180.43  180.59  180.88  183.08  184.08  182.98
  183.98  181.58  181.38  183.88  183.88  180.68  177.78  177.98  179.78  179.08
  174.08  173.98  172.08  172.08   170.9  171.18  172.16  172.17  172.15  172.19
   172.3  172.32  172.41  173.34  173.45  173.53  173.85  174.33  178.55  181.28
  186.28  192.98  197.88  200.28  200.58  201.68   200.5   199.5     200  197.58
  195.08  193.08  191.48  192.48  192.38  189.68  187.48  183.08  181.78  180.98
  179.98  182.58  179.58  178.78  177.68  177.88  180.88  183.08  184.08  182.98
  183.98  181.58  181.38  183.88  183.88  180.68  177.78  177.38  179.78  179.08
  174.08  173.98  172.08  172.08  169.26  168.98  170.28  169.01  169.32  166.81
  163.42  160.92  159.64  161.05  163.18  163.33  166.34  172.35  178.55  181.28
  186.28  192.98  197.88  200.28  200.58  201.68  199.98  197.51  197.55  197.58
BR Coef= 1 , 1 , 0 ,1.25, 0 ,,,.8,-1,2,0,
WSPro=,,,, 1 ,,,, 0 ,,,, 0 ,,,,-1 ,-1 ,-1 , 0 , 0 , 0 , 0 , 0
Culvert=2,10,11,54,.015,.4,1,8,1,157.76,4967.7,157.73,4967.7,Culvert #1  , 0 ,10
Culvert Bottom n=.015
Culvert=2,10,11,54,.015,.4,1,8,1,157.87,4981.7,157.78,4981.7,Culvert #2  , 0 ,10
Culvert Bottom n=.015
Culvert=2,10,11,54,.015,.4,1,8,1,157.86,4995.2,157.69,4995.2,Culvert #3  , 0 ,10
Culvert Bottom n=.015
Culvert=2,10,11,54,.015,.4,1,8,1,157.91,5009.2,157.73,5009.2,Culvert #4  , 0 ,10
Culvert Bottom n=.015
Culvert=2,10,11,54,.015,.4,1,8,1,157.88,5024.4,157.7,5024.4,Culvert #5  , 0 ,10
Culvert Bottom n=.015
Culvert=2,10,11,54,.015,.4,1,8,1,157.86,5038.4,157.65,5038.4,Culvert #6  , 0 ,10
Culvert Bottom n=.015
BR U #Sta/Elev= 195
  1839.5     195  1839.6  194.99    1853     193  1859.6  192.74  1879.6  191.94
    1893   191.4    1933   192.4  1999.6  192.34    2053   192.3  2059.6  192.24
  2079.6  192.07  2159.6  191.38  2199.6  191.03    2273   190.4    2313   189.7
    2353   189.6  2359.6  189.14    2373   188.2  2379.6  187.94    2393   187.4
    2413   187.1  2439.6  186.44  2479.6  185.44    2493   185.1    2573   184.3
    2633     183    2673   182.7  2699.6  182.97    2713   183.1  2719.6  182.99
    2773   182.1  2839.6  181.83    2873   181.7    2933   180.9    2953   179.9
  2959.6  180.03    2973   180.3    2993   181.2  2999.6  181.27  3019.6  181.47
    3033   181.6    3073   182.5  3079.6  182.34    3093     182  3099.6  181.77
  3119.6  181.07    3133   180.6    3153   179.5    3193   178.6  3199.6  178.62
    3233   178.7    3253   177.6    3273   177.8  3299.6   179.8    3313   180.8
  3339.6  182.26    3353     183  3359.6  183.13    3373   183.4    3393   183.3
  3399.6  183.53    3413     184    3473     184  3499.6  183.56    3533     183
    3573   182.9    3593   183.8    3613   183.9  3639.6  182.64    3653     182
    3673   181.5  3679.6  181.48  3719.6  181.38    3753   181.3  3759.6   181.5
    3773   181.9    3813   183.8    3833   183.8  3839.6  183.31  3850.7  182.47
    3853   182.3  3870.7  181.55    3893   180.6  3910.7  180.36    3953   179.8
    3973   178.9    3993   178.4    4033   178.5  4050.7  177.79    4053   177.7
    4113   177.3  4130.7  177.65  4150.7  178.05  4190.7  178.85    4193   178.9
    4213   179.7  4250.7  179.51  4270.7  179.41    4353     179    4373   178.3
    4393     177  4438.4   175.6  4470.7  174.31  4478.4     174  4498.4   174.3
  4510.7  174.05  4518.4   173.9  4550.7  172.37  4558.4     172  4590.7   172.4
  4598.4   172.5  4610.7  172.35  4630.7   172.1  4638.4     172  4670.7  171.11
  4678.4   170.9  4698.4   170.7  4730.7  169.57  4738.4   169.3  4750.7  169.18
  4778.4   168.9  4810.7  169.42  4822.3  169.61  4858.4   170.2  4869.9  168.93
  4871.4  168.94  4906.4  169.24  4921.6  167.71  4931.4  166.73 4933.49   166.3
  4933.6  166.27 4933.71  166.25    4939  165.15  4952.8  163.34  4955.4  162.01
  4957.4  160.84  4970.9  159.73    4973  159.56  4992.7  160.45  5019.9   160.6
  5021.4  160.61  5042.2  160.97  5044.7  161.87  5047.2   163.1  5051.5  163.25
  5066.9  166.26  5068.5  166.73 5070.89  167.44    5071  167.47 5071.11   167.5
  5087.3  172.27  5115.3  173.45  5116.2  173.49  5162.8  175.46  5165.6  175.63
  5210.7  178.33  5213.1  178.47  5218.4   181.2  5258.4   186.2  5278.4   188.1
  5318.4     191  5338.4   192.9  5438.4   197.8  5518.4   200.2  5550.7   200.2
  5583.2   200.2  5598.4   200.2  5618.4   200.5  5692.8  200.31  5698.4   200.3
  5732.8  200.64  5752.8  200.84  5758.4   200.9  5772.8  200.76  5792.8  200.56
  5798.4   200.5  5812.8  200.57  5818.4   200.6  5832.3   201.3  5852.3   201.6
  5932.3     201  5932.8  200.99  5952.8  200.62  5992.3   199.9  5992.8   199.9
  6032.3   199.9  6072.3     199  6092.3   198.8  6112.3   199.2  6192.3   198.4
  6232.3   197.4  6252.8  197.43  6272.8  197.46  6279.6  197.47  6302.8   197.5
BR U #Mann= 4
  1839.5     .15  4952.8     .08  5047.2     .15  5583.2     .13
BR U Banks=4952.8,5047.2
BR D #Sta/Elev= 195
  1839.5  195.08  1839.6  195.07    1853  193.08  1859.6  192.82  1879.6  192.02
    1893  191.48    1933  192.48  1999.6  192.42    2053  192.38  2059.6  192.32
  2079.6  192.15  2159.6  191.46  2199.6  191.11    2273  190.48    2313  189.78
    2353  189.68  2359.6  189.22    2373  188.28  2379.6  188.02    2393  187.48
    2413  187.18  2439.6  186.52  2479.6  185.52    2493  185.18    2573  184.38
    2633  183.08    2673  182.78  2699.6  183.05    2713  183.18  2719.6  183.07
    2773  182.18  2839.6  181.91    2873  181.78    2933  180.98    2953  179.98
  2959.6  180.11    2973  180.38    2993  181.28  2999.6  181.35  3019.6  181.55
    3033  181.68    3073  182.58  3079.6  182.42    3093  182.08  3099.6  181.85
  3119.6  181.15    3133  180.68    3153  179.58    3193  178.68  3199.6   178.7
    3233  178.78    3253  177.68    3273  177.88  3299.6  179.88    3313  180.88
  3339.6  182.34    3353  183.08  3359.6  183.21    3373  183.48    3393  183.38
  3399.6  183.61    3413  184.08    3473  184.08  3499.6  183.64    3533  183.08
    3573  182.98    3593  183.88    3613  183.98  3639.6  182.72    3653  182.08
    3673  181.58  3679.6  181.56  3719.6  181.46    3753  181.38  3759.6  181.58
    3773  181.98    3813  183.88    3833  183.88  3839.6  183.39  3850.7  182.55
    3853  182.38  3870.7  181.63    3893  180.68  3910.7  180.44    3953  179.88
    3973  178.98    3993  178.48    4033  178.58  4050.7  177.87    4053  177.78
    4113  177.38  4130.7  177.73  4150.7  178.13  4190.7  178.93    4193  178.98
    4213  179.78  4250.7  179.59  4270.7  179.49    4353  179.08    4373  178.38
    4393  177.08  4438.4  175.68  4470.7  174.39  4478.4  174.08  4498.4  174.38
  4510.7  174.13  4518.4  173.98  4550.7  172.45  4558.4  172.08  4590.7  172.48
  4598.4  172.58  4610.7  172.43  4630.7  172.18  4638.4  172.08  4670.7  171.19
  4678.4  170.98  4698.4  170.78  4730.7  169.65  4738.4  169.38  4750.7  169.26
  4778.4  168.98  4810.7   169.5  4822.3  169.69  4858.4  170.28  4869.9  169.01
  4871.4  169.02  4906.4  169.32  4921.6  167.79  4931.4  166.81 4933.49  166.38
  4933.6  166.35 4933.71  166.33    4939  165.23  4952.8  163.42  4955.4  162.09
  4957.4  160.92  4970.9  159.81    4973  159.64  4992.7  160.53  5019.9  160.68
  5021.4  160.69  5042.2  161.05  5044.7  161.95  5047.2  163.18  5051.5  163.33
  5066.9  166.34  5068.5  166.81 5070.89  167.52    5071  167.55 5071.11  167.58
  5087.3  172.35  5115.3  173.53  5116.2  173.57  5162.8  175.54  5165.6  175.71
  5210.7  178.41  5213.1  178.55  5218.4  181.28  5258.4  186.28  5278.4  188.18
  5318.4  191.08  5338.4  192.98  5438.4  197.88  5518.4  200.28  5550.7  200.28
  5583.2  200.28  5598.4  200.28  5618.4  200.58  5692.8  200.39  5698.4  200.38
  5732.8  200.72  5752.8  200.92  5758.4  200.98  5772.8  200.84  5792.8  200.64
  5798.4  200.58  5812.8  200.65  5818.4  200.68  5832.3  201.38  5852.3  201.68
  5932.3  201.08  5932.8  201.07  5952.8   200.7  5992.3  199.98  5992.8  199.98
  6032.3  199.98  6072.3  199.08  6092.3  198.88  6112.3  199.28  6192.3  198.48
  6232.3  197.48  6252.8  197.51  6272.8  197.54  6279.6  197.55  6302.8  197.58
BR D #Mann= 4
  1839.5     .15  4952.8     .08  5047.2     .15  5583.2     .13
BR D Banks=4952.8,5047.2
BC Design=,, 0 ,, 0 ,,,,,,
BC HTab HWMax=201.56

Type RM Length L Ch R = 1 ,253183.0,127.7,127.7,127.7
BEGIN DESCRIPTION:
Downstream Section of Sanders Cemetery Rd (Mueschke)
Ineffective at Sta 3350 based on topo upstream of the cross section
END DESCRIPTION:
XS GIS Cut Line= 5
     3000783.151   13962832.5865    3000830.3344   13960816.1702
    3000913.3033   13959087.6606    3000958.0785   13958898.6097
    3000875.6343   13958383.3335
#Sta/Elev= 30
  1839.5  195.06    1893  191.46    2353  189.66    2493  185.16    2953  179.96
    3073  182.56    3253  177.66    3413  184.06    3753  181.36    3833  183.86
    3893  180.66    4113  177.36    4213  179.76    4353  179.06  4558.4  172.06
  4906.4   169.3  4952.8   163.4  4957.4   160.9    4973  159.62  5042.2  161.03
  5047.2  163.16  5087.3  172.33  5213.1  178.53  5218.4  181.26  5258.4  186.26
  5338.4  192.96  5518.4  200.26  5583.2  200.26  5852.3  201.66  6302.8  197.56
#Mann= 4 ,-1 , 0
  1839.5     .15       0  4952.8     .08       0  5047.2     .15       0
  5583.2     .13       0
#XS Ineff= 3 ,-1
    3350    3850     184    4500    4960   169.9    5045    5200   171.5
Permanent Ineff=
       F       F       F
Bank Sta=4952.8,5047.2
XS Rating Curve= 0
Exp/Cntr=.5,.3

Type RM Length L Ch R = 1 ,253055.3,479.35,759.5,696.88
BEGIN DESCRIPTION:
Cross Section XS186
Ineffective at Sta 3500 based on topo upstream of the cross section
END DESCRIPTION:
XS GIS Cut Line= 3
    3000889.4776   13962821.0718    3000996.8816   13960453.7299
    3000992.6226   13958524.4785
#Sta/Elev= 30
  1793.3   200.3  2373.3   185.4  2673.3   180.8  2893.3   178.9  2973.3   179.7
  3053.3   176.9  3133.3   180.6  3353.3   179.9  3493.3   183.6  3653.3     180
  3813.3   178.8  4033.3   181.1  4263.1   177.7  4383.1   170.4  4503.1   171.6
  4723.1   166.9  4783.1   171.7  4843.1   172.7  4883.1     172  4978.8  166.54
  4986.9  162.43  5001.9   159.3  5060.6   169.7    5081  169.14  5223.1   184.8
  5263.1   187.7  5483.1   195.3  5590.3  195.31  5883.1   200.8  6092.3   201.1
#Mann= 5 ,-1 , 0
  1793.3     .15       0  4978.8     .08       0  5060.6     .15       0
  5590.3     .13       0  6092.3      .2       0
#XS Ineff= 2 , 0
       0    3500     183               0
Permanent Ineff=
       F       F
Bank Sta=4978.8,5060.6
XS Rating Curve= 0
Exp/Cntr=.3,.1

Type RM Length L Ch R = 1 ,252295.8,1440.26,1732.5,1639.68
BEGIN DESCRIPTION:
Cross Section XS185
END DESCRIPTION:
XS GIS Cut Line= 3
    3001140.5149   13963053.4926    3001628.8681   13959462.6602
    3001873.0447   13958371.0472
#Sta/Elev= 30
    1876     197  1876.1     197  2036.1   195.5  2776.1   181.7  2856.1   181.4
  3036.1   185.4  3296.1   184.7  3636.1     180  3736.1   174.2  3776.1   174.6
  3836.1   178.7  3896.1   180.3  4156.1   175.6  4216.1   171.8  4856.1   169.6
  4936.1   168.2  4951.7  166.02  4968.5  166.34  4978.8  164.86  4986.9  160.75
  5001.9  157.62  5013.2  160.69  5060.6  168.02    5081  167.46  5256.1   189.9
  5336.1   196.5  5625.5  198.51    6140   197.8    6360   198.9  6618.6   202.6
#Mann= 6 , 1 , 0
    1876      .2       0  1876.1     .15       0  4978.8     .08       0
  5060.6     .15       0  5625.5     .09       0  6618.6      .2       0
Bank Sta=4978.8,5060.6
XS Rating Curve= 0
Exp/Cntr=.3,.1

Type RM Length L Ch R = 1 ,250563.3,727.04,1046.5,1069.96
BEGIN DESCRIPTION:
Cross Section XS184
Ineffective at Sta 3500 based on topo downstream of the cross section
END DESCRIPTION:
XS GIS Cut Line= 3
    3002289.5813   13962823.6793    3003050.8378   13960525.5466
     3003323.741    13958888.127
#Sta/Elev= 30
  2535.6   197.9  2655.6   199.6  2775.6   197.1  3275.6   179.7  3375.6   180.3
  3455.6   187.1  3515.6   187.5  3575.6   183.5  3755.6     176  3995.6   169.2
  4055.6   168.8  4115.6   171.8  4195.6   173.4  4295.6   168.6  4475.6   167.6
  4535.6   165.4  4655.6   166.2  4795.6     170  4855.6     168  4952.3  167.68
  4985.9   163.4  4992.8  156.82  5006.7  158.33  5017.3  164.02  5196.5   168.1
  5296.5   167.4  5436.5   174.8  5676.5     192  6296.5   195.4  6616.5   199.4
#Mann= 4 ,-1 , 0
  2535.6     .15       0  4985.9     .08       0  5017.3     .15       0
  6616.5      .2       0
#XS Ineff= 2 , 0
       0    3500   180.5               0
Permanent Ineff=
       F       F
Bank Sta=4985.9,5017.3
XS Rating Curve= 0
Exp/Cntr=.3,.1

Type RM Length L Ch R = 1 ,249516.8,1260.96,1621.2,1123.06
BEGIN DESCRIPTION:
Cross Section XS183
Ineffective at Sta 3750 based on topo upstream of the cross section
END DESCRIPTION:
XS GIS Cut Line= 2
    3002591.2112   13962938.5859    3004492.2912   13959858.0037
#Sta/Elev= 30
  2743.7   199.1  2983.7     196  3063.7   193.5  3123.7   189.8  3243.7   187.8
  3623.7   176.6  3763.7   180.1  3843.7   175.4  3883.7   170.8  3943.7     168
  4083.7   171.2  4163.7   168.2  4303.7   166.3  4383.7     163  4603.7   163.5
  4843.7   169.3  4975.5   166.1  4987.3  158.33  4994.8  156.02  5012.7  158.28
    5027  165.22 5054.21  165.49  5083.7   163.6  5283.7   164.5  5323.7   163.6
  5483.7   170.4  5603.7   184.3  5783.7   190.4  6063.7   190.4  6363.7   188.4
#Mann= 3 ,-1 , 0
  2743.7     .15       0  4975.5     .08       0    5027     .15       0
#XS Ineff= 2 , 0
       0    3750     180               0
Permanent Ineff=
       F       F
Bank Sta=4975.5,5027
XS Rating Curve= 0
Exp/Cntr=.3,.1