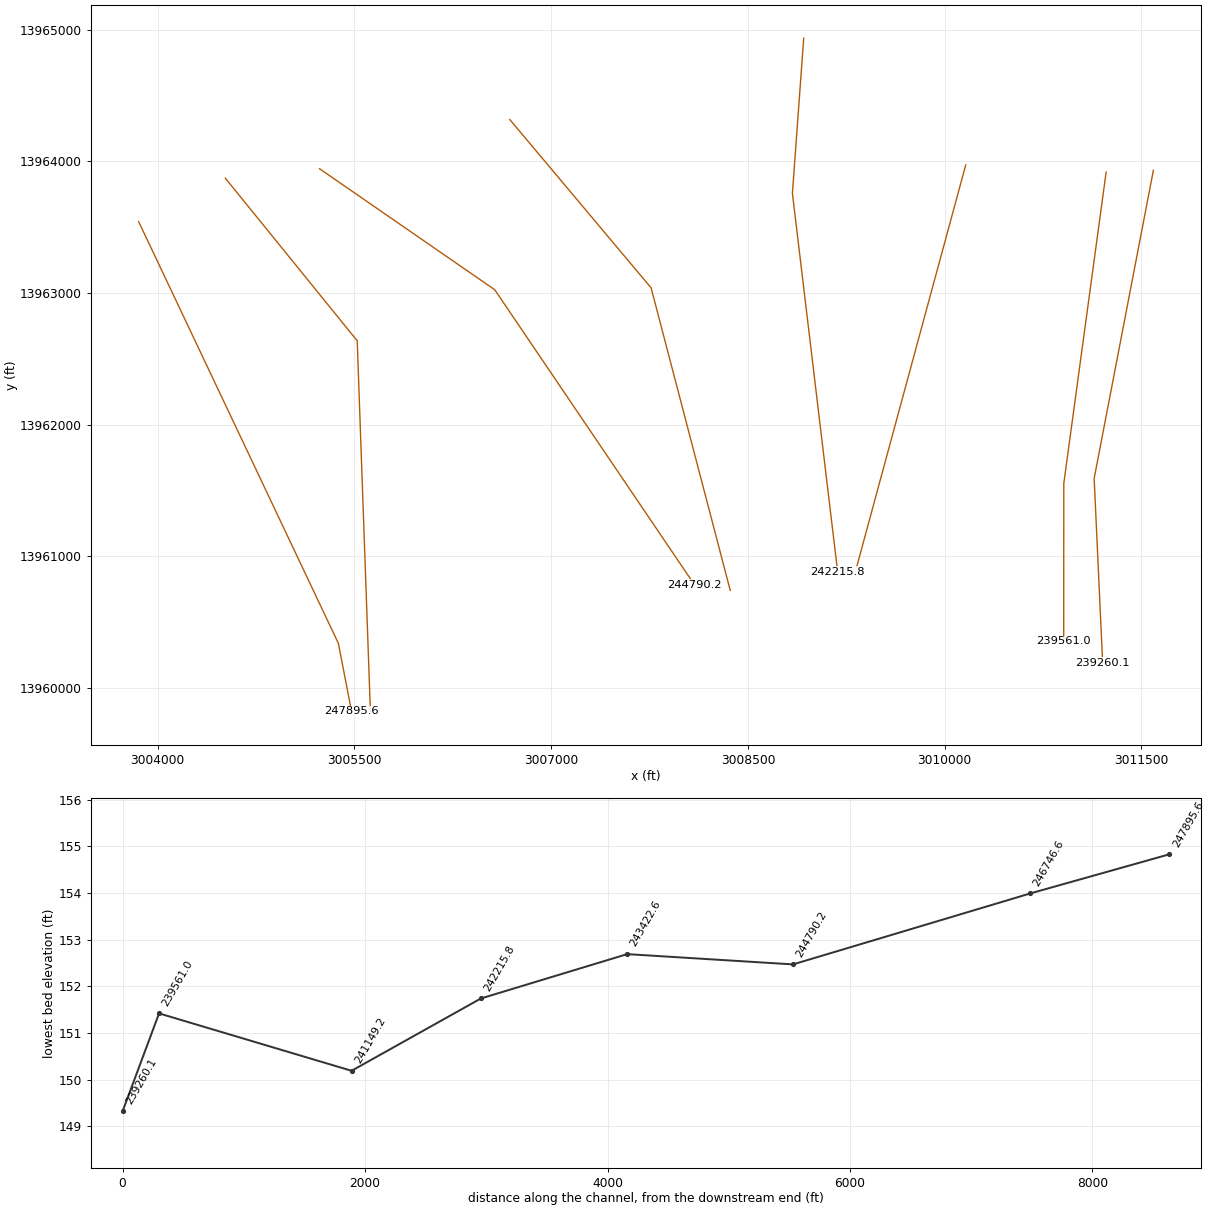
HEC-RAS study J100-00-00.prj: J100-00-00

--- J100-00-00.g01 (geometry) --- (continued)

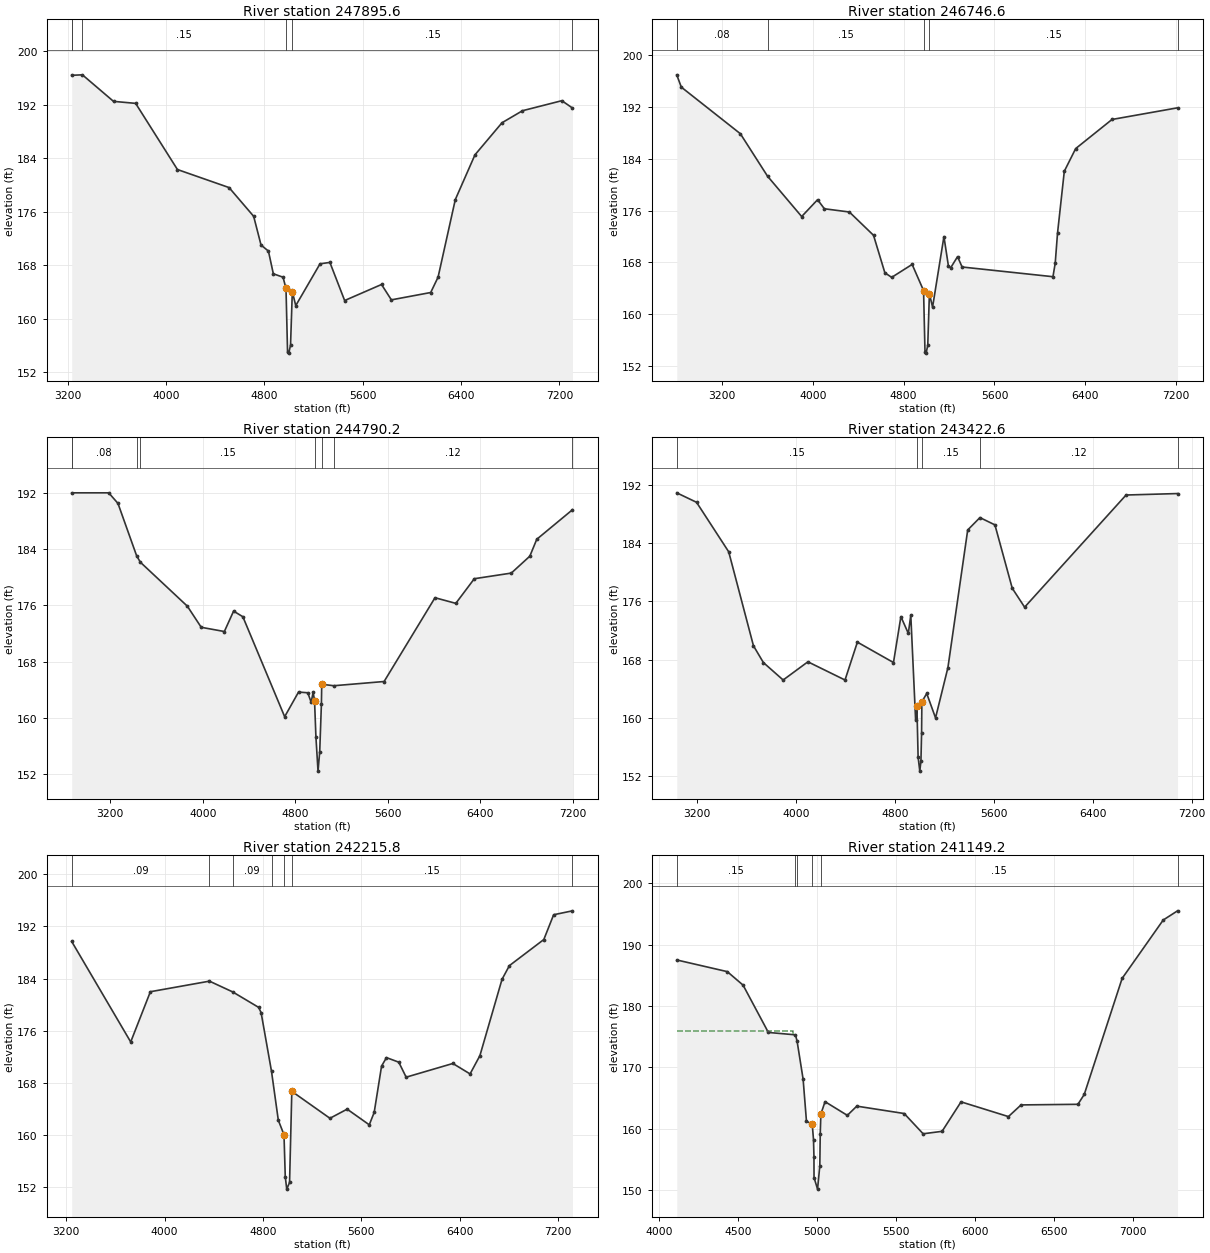
Type RM Length L Ch R = 1 ,247895.6,1129.99,1149,646.39
BEGIN DESCRIPTION:
Cross Section XS182
END DESCRIPTION:
XS GIS Cut Line= 3
    3003855.1842   13963541.8458    3005377.6971   13960338.8233
    3005478.2404   13959821.7434
#Sta/Elev= 30
  3232.6   196.4  3319.7  196.47  3572.6   192.5  3752.6   192.2  4092.6   182.3
  4512.6   179.6  4712.6   175.3  4772.6     171  4832.6   170.1  4872.6   166.7
  4951.6  166.19  4975.6   164.5  4988.3  154.96  4997.9  154.83  5012.5  156.03
    5027  164.02  5054.9  161.94  5252.6   168.2  5332.6   168.4  5452.6   162.7
  5752.6   165.1  5832.6   162.8  6152.6   163.9  6212.6   166.2  6352.6   177.8
  6512.6   184.5  6732.6   189.3  6899.1   191.1  7219.1   192.6  7305.8   191.5
#Mann= 6 , 1 , 0
  3232.6      .2       0  3232.6     .08       0  3319.7     .15       0
  4975.6     .08       0    5027     .15       0  7305.8      .2       0
Bank Sta=4975.6,5027
XS Rating Curve= 0
Exp/Cntr=.3,.1

Type RM Length L Ch R = 1 ,246746.6,1045.15,1956.4,1964.1
BEGIN DESCRIPTION:
Cross Section XS181
END DESCRIPTION:
XS GIS Cut Line= 3
    3004515.8974   13963872.2024    3005521.3304    13962636.956
    3005621.8737   13959821.7434
#Sta/Elev= 30
  2802.3     197  2842.3   195.1  3362.3   187.9  3601.5  181.34  3902.3   175.1
  4042.3   177.7  4102.3   176.3  4322.3   175.8    4535   172.2    4635   166.4
    4695   165.7    4875   167.7  4975.6  163.66  4988.3  154.12  4997.9  153.99
  5012.5  155.19    5027  163.18  5054.9   161.1    5155     172    5195   167.4
    5215   167.2    5275   168.9    5315   167.3    6115   165.8    6135   167.9
    6155   172.5    6215   182.1    6315   185.6    6635   190.1    7212   191.9
#Mann= 6 , 1 , 0
  2802.3      .2       0  2802.3     .08       0  3601.5     .15       0
  4975.6     .08       0    5027     .15       0    7212      .2       0
Bank Sta=4975.6,5027
XS Rating Curve= 0
Exp/Cntr=.3,.1

Type RM Length L Ch R = 1 ,244790.2,1143.39,1367.6,807.51
BEGIN DESCRIPTION:
Cross Section XS180
END DESCRIPTION:
XS GIS Cut Line= 3
    3005234.0638    13963944.019    3006569.8535   13963024.7659
    3008092.3664   13960784.0865
#Sta/Elev= 30
  2867.3     192  3187.3     192  3267.3   190.5  3428.7  183.06  3460.7  182.15
  3867.3   175.9  3987.3   172.9  4187.3   172.3  4267.3   175.2  4347.3   174.4
  4708.8   160.2  4828.8   163.7  4908.8   163.6  4938.2  162.24    4955  163.69
  4967.2  162.48  4979.2  157.31  4997.3  152.47    5012  155.24  5026.6  162.03
  5029.3  164.81  5133.7   164.6  5568.8   165.2  6008.8   177.1  6188.8   176.3
  6348.8   179.8  6668.8   180.6  6828.8     183  6888.8   185.4  7197.8   189.6
#Mann= 8 , 1 , 0
  2867.3      .2       0  2867.3     .08       0  3428.7     .15       0
  3460.7     .15       0  4967.2     .08       0  5029.3     .15       0
  5133.7     .12       0  7197.8      .2       0
Bank Sta=4967.2,5029.3
XS Rating Curve= 0
Exp/Cntr=.3,.1

Type RM Length L Ch R = 1 ,243422.6,1408.18,1206.8,1138.77
BEGIN DESCRIPTION:
Cross Section XS179
Ineffective at Sta 5600 based on topo downstream of the cross section
END DESCRIPTION:
XS GIS Cut Line= 3
    3006684.7601   13964317.4656    3007762.0098   13963039.1293
    3008365.2697   13960740.9965
#Sta/Elev= 30
  3037.8   190.9  3197.8   189.6  3457.8   182.8  3657.8   169.9  3737.8   167.6
  3897.8   165.2  4097.8   167.7  4397.8   165.2  4497.8   170.4  4789.5   167.6
  4849.5   173.9  4909.5   171.6  4929.5   174.1  4968.5  159.73  4978.9   161.6
  4988.6  154.62  5002.3  152.69  5011.5  154.07  5016.7  157.95    5019  162.21
  5058.3  163.35  5129.5     160  5229.5   166.9  5389.5   185.8  5488.3   187.5
  5609.5   186.5  5749.5   177.8  5849.5   175.2  6669.5   190.6  7085.5   190.8
#Mann= 5 ,-1 , 0
  3037.8     .15       0  4978.9     .08       0    5019     .15       0
  5488.3     .12       0  7085.5      .2       0
#XS Ineff= 2 , 0
       0                    5600       0     178
Permanent Ineff=
       F       F
Bank Sta=4978.9,5019
XS Rating Curve= 0
Exp/Cntr=.3,.1

Type RM Length L Ch R = 1 ,242215.8,1212.62,1066.6,785.81
BEGIN DESCRIPTION:
Cross Section XS178
Ineffective at Sta 4000 based on topo downstream of the cross section
END DESCRIPTION:
XS GIS Cut Line= 3
    3008925.4395   13964935.0888    3008839.2596   13963757.2957
    3009183.9795   13960884.6298
#Sta/Elev= 30
    3245   189.7    3725   174.3    3885     182  4365.7  183.62  4554.8  181.97
  4765.9   179.6  4785.9   178.8  4870.5   169.8  4925.9   162.3  4972.1  160.08
  4982.4  153.66  4994.4  151.74  5017.4  152.76  5035.7  166.73  5345.9   162.6
  5485.9     164  5665.9   161.6  5705.9   163.5  5765.9   170.6  5805.9   171.9
  5905.9   171.2  5965.9   168.9  6345.9     171  6485.9   169.4  6565.9   172.2
  6745.9   183.9  6805.9     186  7085.9     190  7165.9   193.8  7319.2   194.4
#Mann= 7 ,-1 , 0
    3245     .09       0  4365.7     .15       0  4554.8     .09       0
  4870.5     .15       0  4972.1     .08       0  5035.7     .15       0
  7319.2      .2       0
#XS Ineff= 2 , 0
       0    4000     178               0
Permanent Ineff=
       F       F
Bank Sta=4972.1,5035.7
XS Rating Curve= 0
Exp/Cntr=.3,.1

Type RM Length L Ch R = 1 ,241149.2,1285.8,1588.2,1418.47
BEGIN DESCRIPTION:
Cross Section XS177
Ineffective at Sta 4850 based on topo downstream of the cross section
END DESCRIPTION:
XS GIS Cut Line= 2
    3010160.6859   13963972.7457    3009327.6128   13960913.3565
#Sta/Elev= 30
  4112.8   187.5  4432.8   185.6  4532.8   183.4  4692.8   175.7  4864.5  175.31
    4875  174.24  4912.9  168.09  4934.1  161.24  4970.6  160.76  4978.7  158.24
  4981.5   155.5    4982  152.08  5004.3  150.19  5018.6  153.99  5021.3  159.17
  5025.3  162.41  5051.7  164.43  5192.8   162.2  5252.8   163.7  5552.8   162.5
  5672.8   159.2  5792.8   159.6  5912.8   164.4  6212.8     162  6292.8   163.9
  6652.8     164  6692.8   165.6  6932.8   184.5  7192.8     194  7283.6   195.5
#Mann= 6 ,-1 , 0
  4112.8     .15       0  4864.5     .09       0    4875     .15       0
  4970.6     .08       0  5025.3     .15       0  7283.6      .2       0
#XS Ineff= 2 , 0
       0    4850     176               0
Permanent Ineff=
       F       F
Bank Sta=4970.6,5025.3
XS Rating Curve= 0
Exp/Cntr=.3,.1

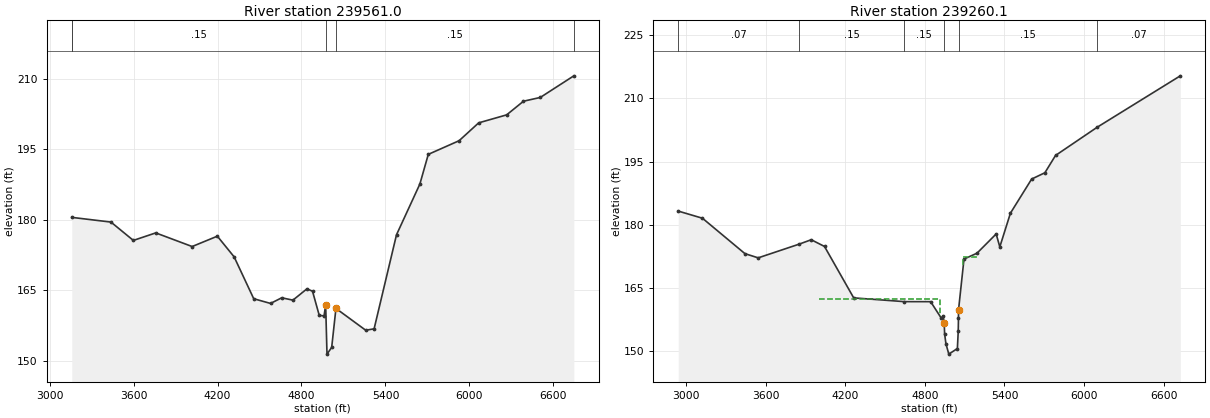
Type RM Length L Ch R = 1 ,239561.0,239.09,300.9,181.33
BEGIN DESCRIPTION:
Cross Section XS176
END DESCRIPTION:
XS GIS Cut Line= 3
    3011231.1223   13963918.2328     3010908.247   13961553.0735
     3010907.579   13960353.1866
#Sta/Elev= 30
  3158.8   180.5  3438.8   179.5  3598.8   175.6  3758.8   177.2  4018.8   174.3
  4198.8   176.5  4318.8   172.1  4458.8   163.2  4578.8   162.2  4658.8   163.4
  4738.8   162.9  4838.8   165.3  4878.8   164.8  4926.9  159.65  4961.2  159.56
  4972.7  161.88  4982.2  151.42  5015.7  152.85  5046.2  161.14  5258.8   156.5
  5318.8   156.8  5478.8   176.8  5645.9   187.6  5705.9   193.9  5925.9   196.8
  6065.9   200.6  6265.9   202.3  6385.9   205.2  6505.9     206  6745.8   210.6
#Mann= 5 , 1 , 0
  3158.8      .2       0  3158.8     .15       0  4972.7     .08       0
  5046.2     .15       0  6745.8      .2       0
Bank Sta=4972.7,5046.2
XS Rating Curve= 0
Exp/Cntr=.5,.3

Type RM Length L Ch R = 1 ,239260.1,61,61,61
BEGIN DESCRIPTION:
Upstream Section of Cypress Rose Hill Decker
Ineffective at Sta 3940 based on topo upstream of the cross section
END DESCRIPTION:
XS GIS Cut Line= 3
    3011591.2231   13963931.7962    3011139.8008   13961591.5281
    3011204.3665   13960192.3501
#Sta/Elev= 30
  2940.6  183.27  3123.3  181.57  3443.3  173.17  3543.3  172.17  3850.9  175.41
  3943.3  176.47  4043.3  174.87  4263.3  162.67  4643.8  161.78  4843.3  161.77
  4923.3  157.87  4937.9  158.34  4945.7  156.63  4948.7  154.12  4958.5   151.8
  4980.3  149.32  5044.9  150.65  5051.3  154.75  5053.1  157.89  5053.5   159.8
  5094.7  171.88  5192.6  173.27  5337.2  177.84  5364.7  174.77  5444.7  182.77
  5604.7  190.87  5704.7  192.37  5784.7  196.47  6098.8  203.17  6725.4  215.37
#Mann= 6 ,-1 , 0
  2940.6     .07       0  3850.9     .15       0  4643.8     .15       0
  4945.7     .08       0  5053.5     .15       0  6098.8     .07       0
#XS Ineff= 3 ,-1
    2950    3940     176    4000    4915   162.4    5090    5200   172.4
Permanent Ineff=
       F       F       F
Bank Sta=4945.7,5053.5
XS Rating Curve= 0
Exp/Cntr=.5,.3