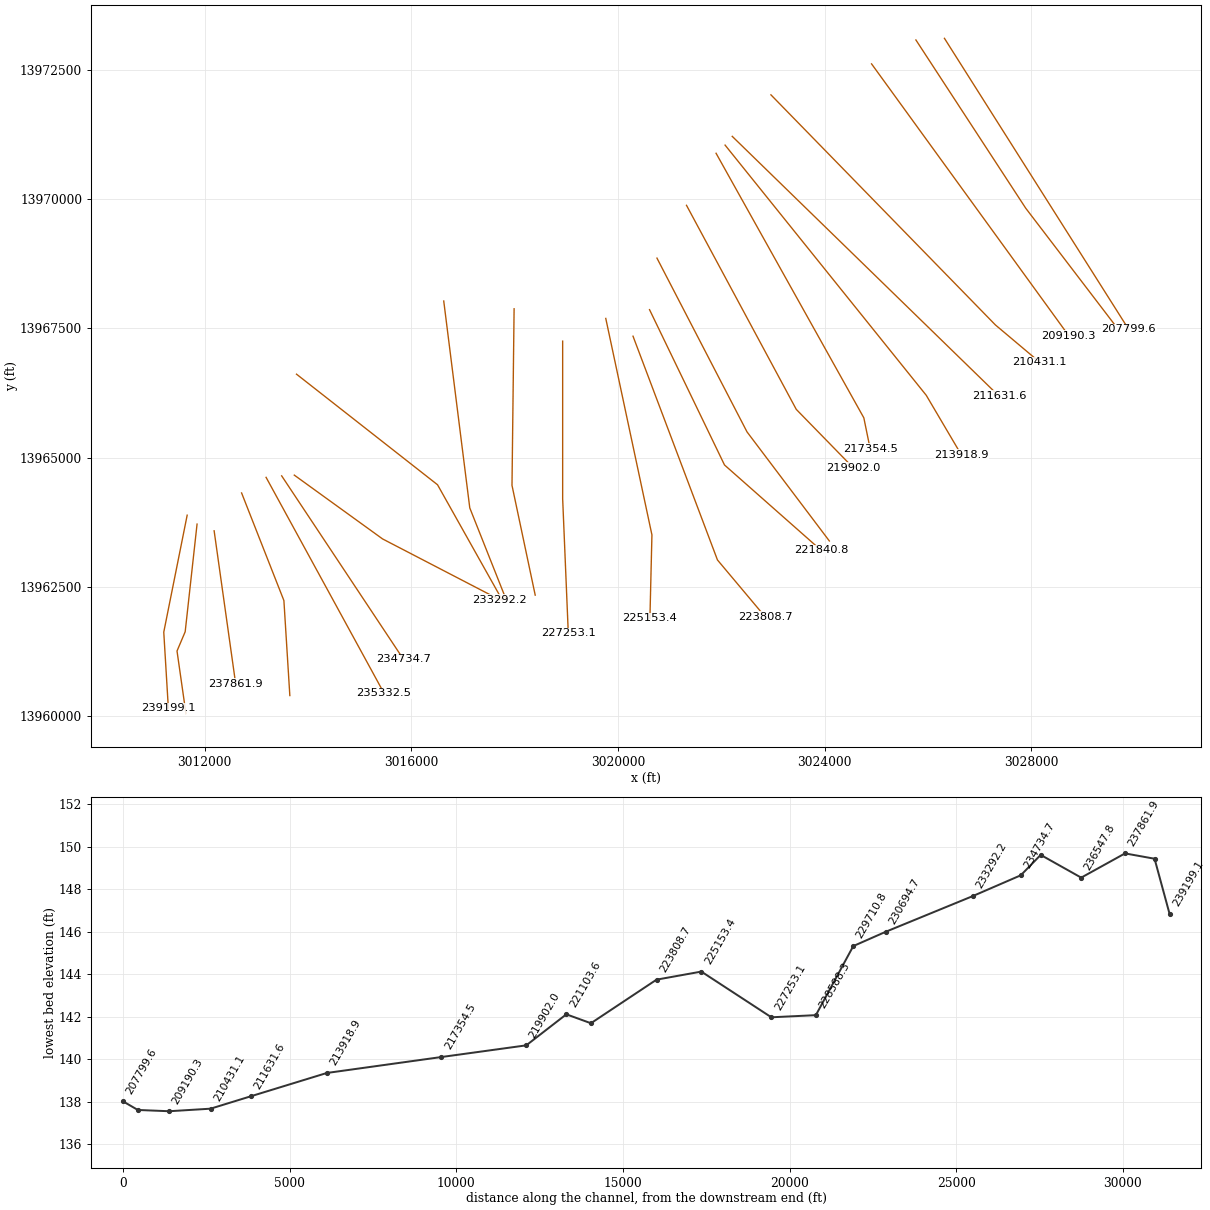
HEC-RAS study J100-00-00.prj: J100-00-00

--- J100-00-00.g01 (geometry) --- (continued)

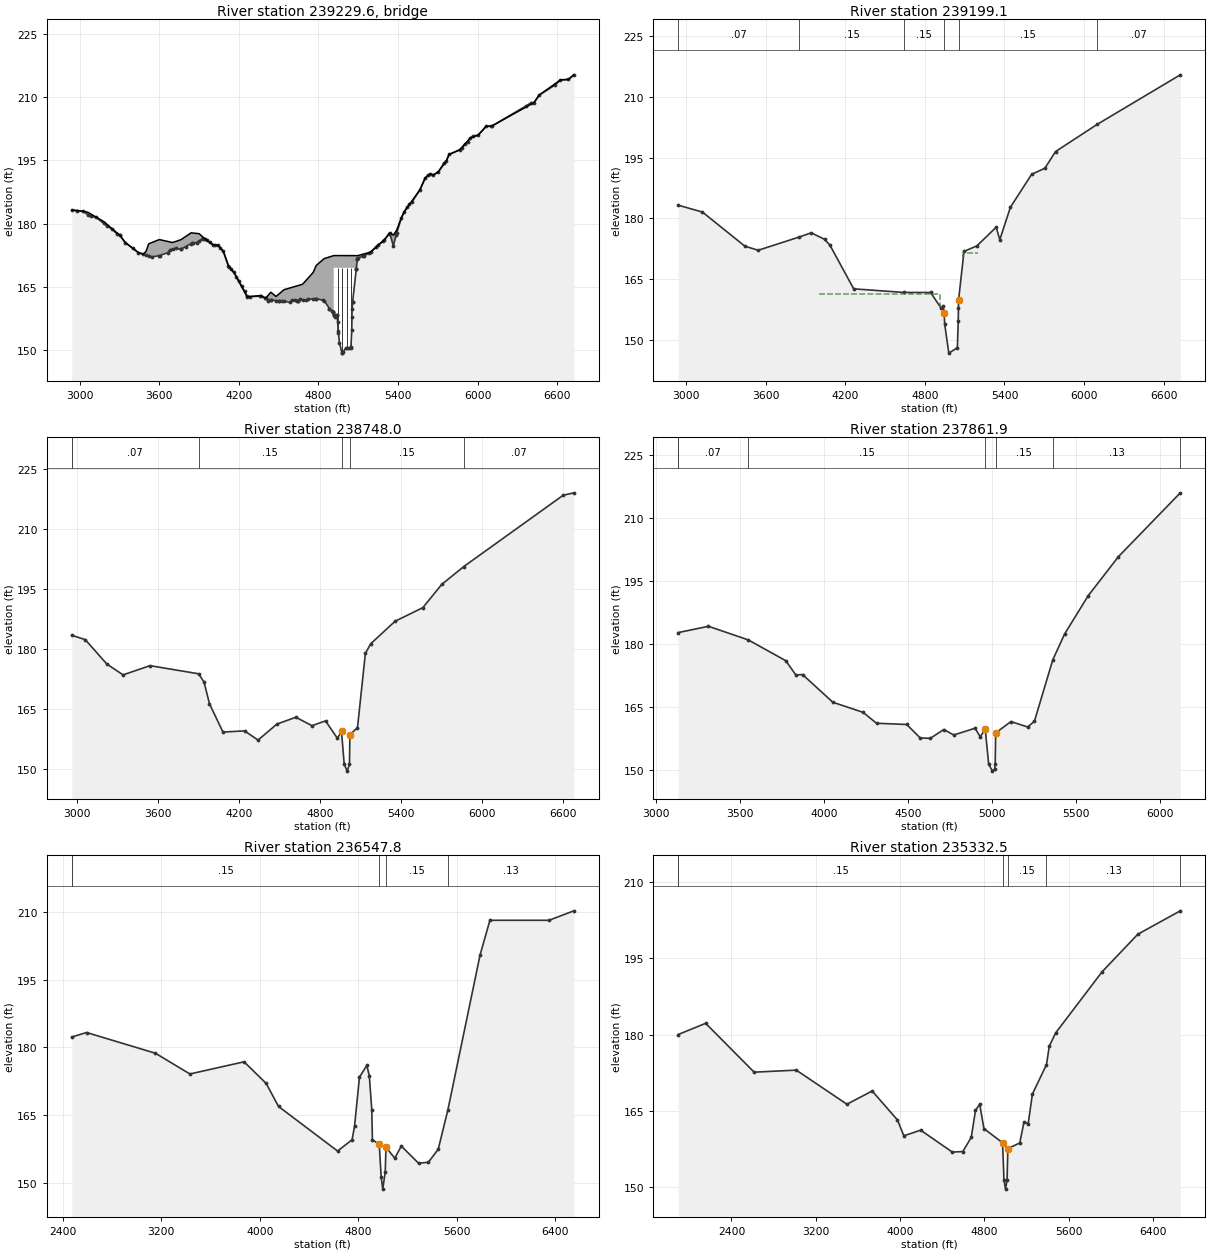
Type RM Length L Ch R = 3 ,239229.6,,,
BEGIN DESCRIPTION:
CYPRESS ROSE HILL DECKER
Structure ID: J100-00-00-10
Square nose piers
END DESCRIPTION:
Node Name=Cypress Rose Hil
Bridge Culvert--1,0,-1,-1, 0
Deck Dist Width WeirC Skew NumUp NumDn MinLoCord MaxHiCord MaxSubmerge Is_Ogee
10,41,2.6,0, 60, 60, , , .95, 0, 1,1,,
  2940.6  3023.3  3060.6  3123.3  3180.6  3303.3  3343.3  3443.3  3480.6  3500.6
  3520.6  3600.6  3700.6  3763.3  3840.6  3900.6  3943.3  4003.3  4043.3  4083.3
  4123.3  4163.3  4263.3  4360.6  4403.3  4440.6  4480.6  4540.6  4680.6  4760.6
  4783.3  4843.3 4915.31  4915.4 5085.51  5094.7  5192.6    5295  5337.2  5364.7
  5389.2  5424.7  5444.7  5564.7  5604.7  5644.7  5664.7  5704.7  5764.7  5784.7
  5864.7  5944.7  6004.7  6064.7  6104.7  6424.7  6464.7  6624.7  6684.7  6725.4
   183.2  182.91   182.7  181.55   180.5  177.21  175.51  173.11  172.74   173.4
   175.2   176.2   175.5  176.17   177.8   177.6  176.41  175.01  174.81  173.41
  169.81  168.41  162.61   162.9  162.31   163.7   162.7   164.3   165.6   168.4
  170.06  171.68   172.4   172.4  172.39  172.37  173.21  176.05  177.78  177.26
   178.4  181.31  182.71     188   190.8   191.8   191.5   192.3   194.9   196.4
   197.5   200.3     201   203.1   203.1   208.7   210.5   214.1   214.2   215.3
   183.2   182.9  182.15   181.5  180.07   177.2   175.5   173.1  172.73  172.53
  172.33  172.39  173.93   173.9  175.25  175.85   176.4     175   174.8   173.4
   169.8   168.4   162.6  162.79   162.3  161.87  161.71  161.58  161.91  162.12
   162.2   161.7  158.36   169.5  169.49  171.81   173.2  176.04  177.77   174.7
  177.66   181.3   182.7     188   190.8   191.8   191.5   192.3   194.9   196.4
   197.5   200.3     201   203.1   203.1   208.7   210.5   214.1   214.2   215.3
  2940.6  3023.3  3060.6  3123.3  3180.6  3303.3  3343.3  3443.3  3480.6  3500.6
  3520.6  3600.6  3700.6  3763.3  3840.6  3900.6  3943.3  4003.3  4043.3  4083.3
  4123.3  4163.3  4263.3  4360.6  4403.3  4440.6  4480.6  4540.6  4680.6  4760.6
  4783.3  4843.3 4915.31  4915.4 5085.51  5094.7  5192.6    5295  5337.2  5364.7
  5389.2  5424.7  5444.7  5564.7  5604.7  5644.7  5664.7  5704.7  5764.7  5784.7
  5864.7  5944.7  6004.7  6064.7  6104.7  6424.7  6464.7  6624.7  6684.7  6725.4
   183.2  182.91   182.7  181.55   180.5  177.21  175.51  173.11  172.74   173.4
   175.2   176.2   175.5  176.17   177.8   177.6  176.41  175.01  174.81  173.41
  169.81  168.41  162.61   162.9  162.31   163.7   162.7   164.3   165.6   168.4
  170.06  171.68   172.4   172.4  172.39  172.37  173.21  176.05  177.78  177.26
   178.4  181.31  182.71     188   190.8   191.8   191.5   192.3   194.9   196.4
   197.5   200.3     201   203.1   203.1   208.7   210.5   214.1   214.2   215.3
   183.2   182.9  182.15   181.5  180.07   177.2   175.5   173.1  172.73  172.53
  172.33  172.39  173.93   173.9  175.25  175.85   176.4     175   174.8   173.4
   169.8   168.4   162.6  162.79   162.3  161.87  161.71  161.58  161.91  162.12
   162.2   161.7  158.36   169.5  169.49  171.81   173.2  176.04  177.77   174.7
  177.66   181.3   182.7     188   190.8   191.8   191.5   192.3   194.9   196.4
   197.5   200.3     201   203.1   203.1   208.7   210.5   214.1   214.2   215.3
Pier Skew, UpSta & Num, DnSta & Num=  ,4948.7, 2 ,4948.7, 2 , 0 , 0 , 0 ,,
     1.3     1.3
  153.42  170.52
     1.3     1.3
  153.42  170.52
Pier Skew, UpSta & Num, DnSta & Num=  ,4980.3, 2 ,4980.3, 2 , 0 , 0 , 0 ,,
     1.3     1.3
  148.26  170.54
     1.3     1.3
  148.26  170.54
Pier Skew, UpSta & Num, DnSta & Num=  ,5012.4, 2 ,5012.4, 2 , 0 , 0 , 0 ,,
     1.3     1.3
  149.36  170.57
     1.3     1.3
  149.36  170.57
Pier Skew, UpSta & Num, DnSta & Num=  ,5044.4, 2 ,5044.4, 2 , 0 , 0 , 0 ,,
     1.3     1.3
  149.65  170.57
     1.3     1.3
  149.65  170.57
Abutment Skew #Up #Dn= , 2 , 2
  4915.2    4938
   169.5  158.25
  4915.2    4938
   169.5  158.25
Abutment Skew #Up #Dn= , 2 , 2
  5057.8 5093.89
  161.44  171.53
  5057.8 5093.89
  161.44  171.53
BR Coef= 1 , 1 , 1 ,1.25, 0 ,,,.8,0,2,0,
WSPro=,,,, 1 ,,,, 0 ,,,, 0 ,,,,-1 ,-1 ,-1 , 0 , 0 , 0 , 0 , 0
BR U #Sta/Elev= 163
  2940.6   183.2  2983.3   183.1  3023.3   182.9  3060.6  182.15  3083.3   181.7
  3123.3   181.5  3180.6  180.07  3203.3   179.5  3243.3   178.7  3283.3   177.5
  3300.6  177.24  3303.3   177.2  3343.3   175.5  3400.6  174.12  3443.3   173.1
  3480.6  172.73  3500.6  172.53  3520.6  172.33  3543.3   172.1  3600.6  172.39
  3603.3   172.4  3663.3   173.1  3683.3   173.8  3700.6  173.93  3723.3   174.1
  3760.6  173.91  3763.3   173.9  3800.6  174.55  3840.6  175.25  3843.3   175.3
  3850.9  175.34  3883.3   175.5  3900.6  175.85  3923.3   176.3  3940.6  176.39
  3943.3   176.4  3960.6     176  3980.6  175.53  4003.3     175  4020.6  174.91
  4043.3   174.8  4060.6  174.19  4083.3   173.4  4120.6  170.04  4123.3   169.8
  4140.6  169.19  4163.3   168.4  4180.6  167.43  4200.6   166.3  4220.6  165.18
  4243.3   163.9  4260.6  162.78  4263.3   162.6  4280.6  162.63  4360.6  162.79
  4363.3   162.8  4400.6  162.33  4403.3   162.3  4420.6  161.78  4423.3   161.7
  4440.6  161.87  4443.3   161.9  4480.6  161.71  4500.6  161.61  4503.3   161.6
  4523.3   161.7  4540.6  161.58  4583.3   161.3  4603.3   161.8  4620.6  161.76
  4640.6  161.71  4643.3   161.7  4643.8  161.71  4663.3     162  4680.6  161.91
  4703.3   161.8  4723.3     162  4760.6  162.12  4783.1   162.2  4783.3   162.2
  4833.4  161.78  4843.3   161.7  4882.6  159.83  4883.3   159.8  4903.3   159.2
 4906.19     159  4906.3  158.99 4906.41  158.98  4915.2  158.37 4915.31  158.36
  4915.4  158.35  4923.3   157.8  4937.9  158.27    4938  158.25  4945.7  156.56
  4948.7  154.05  4948.8  154.58  4958.5  151.73  4976.9   149.3  4980.3  149.25
  4984.5  149.45  5005.2  150.41  5012.4  150.35    5034  150.56  5044.4  150.66
  5044.9  150.58  5051.3  154.68  5053.1  157.82  5053.5  159.73  5057.7   161.4
  5057.8  161.44 5085.29  169.17  5085.4   169.2 5085.51  169.23 5093.69  171.53
  5093.8  171.56  5093.9  171.59  5094.7  171.81  5135.4  172.22    5146  172.33
  5184.7  173.05  5192.6   173.2  5234.7  174.51  5245.3  174.84  5286.4  175.83
    5295  176.04  5329.2  177.44  5337.2  177.77  5364.7   174.7  5384.7   177.2
  5389.2  177.66  5424.7   181.3  5444.7   182.7  5469.2  183.86  5484.7   184.6
  5504.7   185.1  5564.7     188  5604.7   190.8  5624.7   191.5  5644.7   191.8
  5664.7   191.5  5704.7   192.3  5744.7   194.3  5764.7   194.9  5784.7   196.4
  5864.7   197.5  5884.7     198  5904.7   198.9  5924.7   199.4  5944.7   200.3
  5964.7   200.8  6004.7     201  6064.7   203.1  6098.8   203.1  6104.7   203.1
  6364.7   207.9  6404.7   208.7  6424.7   208.7  6464.7   210.5  6584.7   212.9
  6624.7   214.1  6684.7   214.2  6725.4   215.3
BR U #Mann= 6
  2940.6     .07  3850.9     .15  4643.8     .15  4945.7    .075  5053.5     .15
  6098.8     .07
BR U Banks=4945.7,5053.5
BR D #Sta/Elev= 163
  2940.6   183.2  2983.3   183.1  3023.3   182.9  3060.6  182.15  3083.3   181.7
  3123.3   181.5  3180.6  180.07  3203.3   179.5  3243.3   178.7  3283.3   177.5
  3300.6  177.24  3303.3   177.2  3343.3   175.5  3400.6  174.12  3443.3   173.1
  3480.6  172.73  3500.6  172.53  3520.6  172.33  3543.3   172.1  3600.6  172.39
  3603.3   172.4  3663.3   173.1  3683.3   173.8  3700.6  173.93  3723.3   174.1
  3760.6  173.91  3763.3   173.9  3800.6  174.55  3840.6  175.25  3843.3   175.3
  3850.9  175.34  3883.3   175.5  3900.6  175.85  3923.3   176.3  3940.6  176.39
  3943.3   176.4  3960.6     176  3980.6  175.53  4003.3     175  4020.6  174.91
  4043.3   174.8  4060.6  174.19  4083.3   173.4  4120.6  170.04  4123.3   169.8
  4140.6  169.19  4163.3   168.4  4180.6  167.43  4200.6   166.3  4220.6  165.18
  4243.3   163.9  4260.6  162.78  4263.3   162.6  4280.6  162.63  4360.6  162.79
  4363.3   162.8  4400.6  162.33  4403.3   162.3  4420.6  161.78  4423.3   161.7
  4440.6  161.87  4443.3   161.9  4480.6  161.71  4500.6  161.61  4503.3   161.6
  4523.3   161.7  4540.6  161.58  4583.3   161.3  4603.3   161.8  4620.6  161.76
  4640.6  161.71  4643.3   161.7  4643.8  161.71  4663.3     162  4680.6  161.91
  4703.3   161.8  4723.3     162  4760.6  162.12  4783.1   162.2  4783.3   162.2
  4833.4  161.78  4843.3   161.7  4882.6  159.83  4883.3   159.8  4903.3   159.2
 4906.19     159  4906.3  158.99 4906.41  158.98  4915.2  158.37 4915.31  158.36
  4915.4  158.35  4923.3   157.8  4937.9  158.27    4938  158.25  4945.7  156.56
  4948.7  154.05  4948.8  154.58  4958.5  151.73  4976.9  146.89  4980.3  146.84
  4984.5  147.04  5005.2     148  5012.4  147.94    5034  148.15  5044.4  148.25
  5044.9  148.17  5051.3  154.68  5053.1  157.82  5053.5  159.73  5057.7   161.4
  5057.8  161.44 5085.29  169.17  5085.4   169.2 5085.51  169.23 5093.69  171.53
  5093.8  171.56  5093.9  171.59  5094.7  171.81  5135.4  172.22    5146  172.33
  5184.7  173.05  5192.6   173.2  5234.7  174.51  5245.3  174.84  5286.4  175.83
    5295  176.04  5329.2  177.44  5337.2  177.77  5364.7   174.7  5384.7   177.2
  5389.2  177.66  5424.7   181.3  5444.7   182.7  5469.2  183.86  5484.7   184.6
  5504.7   185.1  5564.7     188  5604.7   190.8  5624.7   191.5  5644.7   191.8
  5664.7   191.5  5704.7   192.3  5744.7   194.3  5764.7   194.9  5784.7   196.4
  5864.7   197.5  5884.7     198  5904.7   198.9  5924.7   199.4  5944.7   200.3
  5964.7   200.8  6004.7     201  6064.7   203.1  6098.8   203.1  6104.7   203.1
  6364.7   207.9  6404.7   208.7  6424.7   208.7  6464.7   210.5  6584.7   212.9
  6624.7   214.1  6684.7   214.2  6725.4   215.3
BR D #Mann= 6
  2940.6     .07  3850.9     .15  4643.8     .15  4945.7    .075  5053.5     .15
  6098.8     .07
BR D Banks=4945.7,5053.5
BC Design=,, 0 ,, 0 ,,,,,,
BC HTab HWMax=215.37

Type RM Length L Ch R = 1 ,239199.1,451.1,451.1,451.1
BEGIN DESCRIPTION:
Downstream Section of Cypress Rose Hill Decker
Ineffective at Sta 3940 based on topo upstream of the cross section
END DESCRIPTION:
XS GIS Cut Line= 3
    3011664.3268   13963887.2332    3011211.3173   13961623.5245
     3011300.125   13960151.4333
#Sta/Elev= 30
  2940.6  183.27  3123.3  181.57  3443.3  173.17  3543.3  172.17  3850.9  175.41
  3943.3  176.47  4043.3  174.87  4083.3  173.47  4263.3  162.67  4643.8  161.78
  4843.3  161.77  4923.3  157.87  4937.9  158.34  4945.7  156.63  4948.7  154.12
  4980.3  146.84  5044.9  148.17  5051.3  154.75  5053.1  157.89  5053.5   159.8
  5094.7  171.88  5192.6  173.27  5337.2  177.84  5364.7  174.77  5444.7  182.77
  5604.7  190.87  5704.7  192.37  5784.7  196.47  6098.8  203.17  6725.4  215.37
#Mann= 6 ,-1 , 0
  2940.6     .07       0  3850.9     .15       0  4643.8     .15       0
  4945.7     .08       0  5053.5     .15       0  6098.8     .07       0
#XS Ineff= 3 ,-1
    2950    3940     176    4000    4915   161.4    5090    5200   171.4
Permanent Ineff=
       F       F       F
Bank Sta=4945.7,5053.5
XS Rating Curve= 0
Exp/Cntr=.5,.3

Type RM Length L Ch R = 1 ,238748.0,627.72,886.1,899.72
BEGIN DESCRIPTION:
Cross Section XS175
END DESCRIPTION:
XS GIS Cut Line= 4
    3011855.5588   13963714.2057    3011625.7455    13961631.523
    3011467.7489   13961258.0764    3011640.1088   13960051.5567
#Sta/Elev= 30
  2962.1   183.4  3062.1   182.3  3222.1   176.2  3342.1   173.5  3542.1   175.8
  3901.7  173.77  3942.1   171.7  3982.1   166.3  4082.1   159.2  4242.1   159.5
  4342.1   157.2  4482.1   161.2  4622.1   162.9  4742.1   160.8  4842.1     162
  4930.1  157.64  4960.4  159.37  4980.5  151.18  5002.6  149.44  5019.5  151.15
  5022.4  158.54  5078.8  160.31  5137.4   178.9  5177.4   181.3  5357.4   186.9
  5562.9   190.3  5702.9   196.1  5864.9  200.54  6602.9   218.4  6681.7     219
#Mann= 6 , 1 , 0
  2962.1      .2       0  2962.1     .07       0  3901.7     .15       0
  4960.4     .08       0  5022.4     .15       0  5864.9     .07       0
Bank Sta=4960.4,5022.4
XS Rating Curve= 0
Exp/Cntr=.3,.1

Type RM Length L Ch R = 1 ,237861.9,1053.82,1314.1,1110.82
BEGIN DESCRIPTION:
Cross Section XS174
END DESCRIPTION:
XS GIS Cut Line= 2
    3012185.9153   13963584.9358    3012602.4519   13960626.0899
#Sta/Elev= 30
  3133.2   182.7  3313.2   184.2  3549.4  180.97  3773.2     176  3833.2   172.6
  3873.2   172.7  4053.2   166.1  4233.2   163.7  4313.2   161.1  4493.2   160.8
  4573.2   157.6  4633.2   157.5  4713.2   159.6  4773.2   158.3  4899.6  159.91
  4930.1  157.89  4960.4  159.62  4980.5  151.43  5002.6  149.69  5016.4  150.15
  5019.5   151.4  5022.4  158.79  5113.2   161.5  5213.2   160.2  5253.2   161.6
  5362.4  176.22  5433.2   182.4  5573.2   191.5  5753.2   200.8  6121.2     216
#Mann= 7 , 1 , 0
  3133.2      .2       0  3133.2     .07       0  3549.4     .15       0
  4960.4     .08       0  5022.4     .15       0  5362.4     .13       0
  6121.2      .2       0
Bank Sta=4960.4,5022.4
XS Rating Curve= 0
Exp/Cntr=.3,.1

Type RM Length L Ch R = 1 ,236547.8,822.23,1215.3,1251.56
BEGIN DESCRIPTION:
Cross Section XS173
END DESCRIPTION:
XS GIS Cut Line= 3
    3012717.3585   13964317.4656    3013536.0683   13962234.7828
    3013650.9749   13960396.2766
#Sta/Elev= 30
  2472.4   182.3  2592.4   183.3  3152.4   178.7  3432.4   174.1  3872.4   176.8
  4052.4     172  4152.4   166.9  4632.4     157  4750.2   159.5  4770.2   162.5
  4810.2   173.4  4870.2     176  4890.2   173.7  4910.2   166.2  4915.5   159.5
    4971  158.48  4986.6  151.25  4999.5  148.55  5019.6  152.39  5025.8  157.82
  5096.9  155.42  5150.2   158.1  5290.2   154.3  5370.2   154.5  5450.2   157.4
  5528.7  166.11  5790.2   200.5  5870.2   208.2  6350.2   208.2  6552.3   210.3
#Mann= 5 , 1 , 0
  2472.4      .2       0  2472.4     .15       0    4971     .08       0
  5025.8     .15       0  5528.7     .13       0
Bank Sta=4971,5025.8
XS Rating Curve= 0
Exp/Cntr=.3,.1

Type RM Length L Ch R = 1 ,235332.5,445.4,597.8,562.02
BEGIN DESCRIPTION:
Cross Section XS172
END DESCRIPTION:
XS GIS Cut Line= 2
    3013191.3484   13964619.0955    3015475.1178   13960439.3666
#Sta/Elev= 30
  1895.2     180  2155.2   182.2  2615.2   172.6  3015.2     173  3495.2   166.3
  3735.2   168.9  3975.2   163.2  4035.2   160.1  4195.2   161.2  4495.2   156.9
  4595.2     157  4675.2   159.8  4715.2   165.1  4755.2   166.3  4795.2   161.5
  4972.1  158.73  4985.3  151.45    5000  149.62  5014.8  151.45  5022.2  157.57
  5135.2   158.7  5175.2   162.8  5215.2   162.5  5255.2   168.3  5388.6  174.08
  5415.2   177.7  5475.2   180.3  5915.2   192.3  6255.2   199.7  6658.2   204.3
#Mann= 6 , 1 , 0
  1895.2      .2       0  1895.2     .15       0  4972.1     .08       0
  5022.2     .15       0  5388.6     .13       0  6658.2      .2       0
Bank Sta=4972.1,5022.2
XS Rating Curve= 0
Exp/Cntr=.3,.1

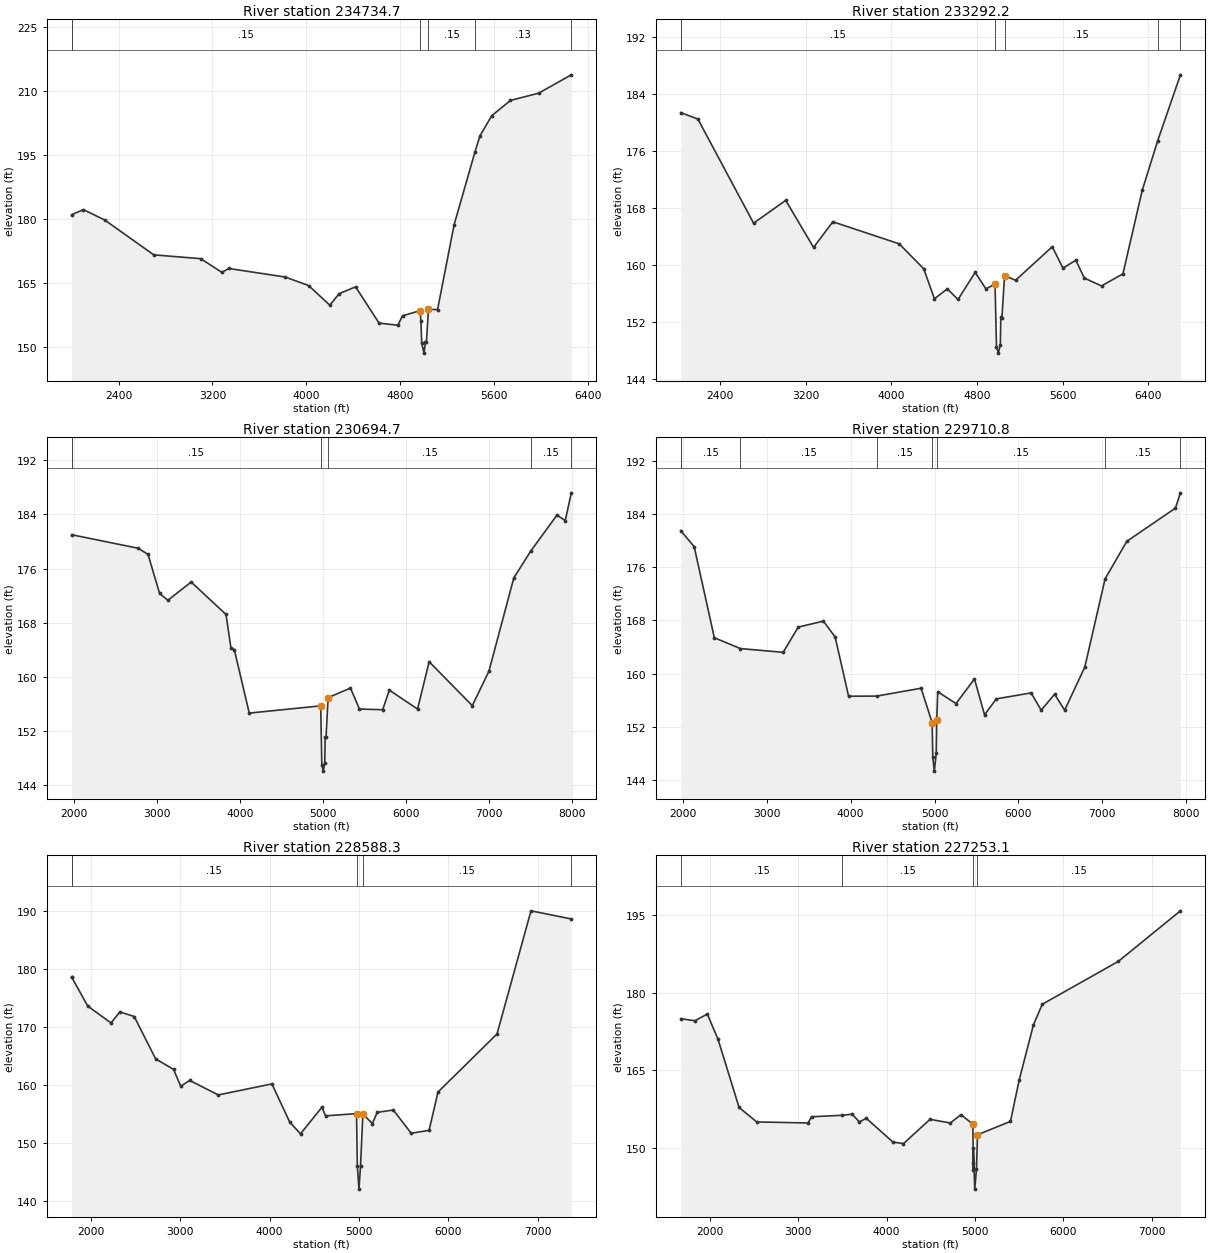
Type RM Length L Ch R = 1 ,234734.7,837.59,1442.5,1740.87
BEGIN DESCRIPTION:
Cross Section XS171
END DESCRIPTION:
XS GIS Cut Line= 2
    3013492.9783   13964647.8222    3015848.5644   13961100.0798
#Sta/Elev= 30
  2000.7   181.1  2100.7   182.3  2280.7   179.9  2700.7   171.7  3100.7   170.8
  3280.7   167.6  3340.7   168.5  3820.7   166.5  4020.7   164.5  4200.7   159.9
  4280.7   162.6  4420.7   164.2  4620.7   155.7  4780.7   155.2  4820.7   157.4
  4971.1  158.63  4977.5  156.11  4984.5  150.97  5003.8  148.66    5016  151.27
  5024.4  151.34  5041.8  158.96  5119.1  158.84  5260.7   178.8  5438.2  195.83
  5480.7   199.6  5580.7   204.3  5740.7   207.9  5980.7   209.6  6259.3   213.9
#Mann= 6 , 1 , 0
  2000.7      .2       0  2000.7     .15       0  4971.1     .08       0
  5041.8     .15       0  5438.2     .13       0  6259.3      .2       0
Bank Sta=4971.1,5041.8
XS Rating Curve= 0
Exp/Cntr=.3,.1

Type RM Length L Ch R = 1 ,233292.2,1581.9,2597.5,904.54
BEGIN DESCRIPTION:
Cross Section XS170
END DESCRIPTION:
XS GIS Cut Line= 3
    3013737.1549   13964662.1855    3015446.3911   13963426.9392
    3017715.7972   13962249.1461
#Sta/Elev= 30
  2033.9   181.4  2193.9   180.5  2713.9   165.9  3013.9   169.1  3273.9   162.5
  3453.9   166.1  4073.9     163  4302.8   159.5  4402.8   155.3  4522.8   156.7
  4622.8   155.2  4782.8     159  4882.8   156.7  4968.6  157.34 4982.01   148.6
  4999.2  147.68  5017.8  148.86  5022.4   152.7  5032.7  152.66  5057.5  158.56
  5159.9  157.89  5502.8   162.6  5602.8   159.6  5722.8   160.7  5802.8   158.2
  5962.8   157.1  6162.8   158.8  6342.8   170.5  6487.4  177.47  6699.6   186.7
#Mann= 6 , 1 , 0
  2033.9      .2       0  2033.9     .15       0  4968.6     .08       0
  5057.5     .15       0  6487.4     .15       0  6699.6      .2       0
Bank Sta=4968.6,5057.5
XS Rating Curve= 0
Exp/Cntr=.3,.1

Type RM Length L Ch R = 1 ,230694.7,1500.5,983.9,283.79
BEGIN DESCRIPTION:
Cross Section XS169
END DESCRIPTION:
XS GIS Cut Line= 3
    3013780.2449   13966615.5983    3016509.2775   13964475.4622
    3017758.8872   13962249.1461
#Sta/Elev= 30
  1967.4     181  2767.4     179  2887.4   178.1  3027.4   172.3  3127.4   171.3
  3407.4     174  3827.4   169.2  3887.4   164.2  3927.4     164  4107.4   154.6
  4968.6  155.67 4982.01  146.93  4999.2  146.01  5017.8  147.19  5022.4  151.03
  5032.7  150.99  5057.5  156.89  5327.4   158.3  5435.5   155.2  5715.5   155.1
  5795.5     158  6135.5   155.2  6275.5   162.2  6795.5   155.7  6995.5   160.8
  7295.5   174.6  7499.6  178.58  7815.5   183.9  7915.5   183.1  7988.6   187.2
#Mann= 6 , 1 , 0
  1967.4      .2       0  1967.4     .15       0  4968.6     .08       0
  5057.5     .15       0  7499.6     .15       0  7988.6      .2       0
Bank Sta=4968.6,5057.5
XS Rating Curve= 0
Exp/Cntr=.3,.1

Type RM Length L Ch R = 1 ,229710.8,1155.97,1122.5,853.53
BEGIN DESCRIPTION:
Cross Section XS168
END DESCRIPTION:
XS GIS Cut Line= 3
    3016629.2206   13968031.2257    3017133.0564    13964027.774
    3017841.1499   13962243.9231
#Sta/Elev= 30
    1976   181.5    2136   179.1    2376   165.4  2686.2  163.77    3196   163.2
    3376     167    3676   167.9    3816   165.5    3976   156.6  4309.9  156.62
  4840.1   157.8  4971.6  152.63  4979.5  147.45  4997.3  145.33  5020.4     148
  5026.2  153.06    5038  157.27    5256   155.5    5476   159.2    5596   153.8
    5736   156.2    6151   157.1    6271   154.5    6431   156.9    6551   154.5
    6791     161  7032.5  174.26    7291   179.9    7871   184.9  7930.3   187.2
#Mann= 8 , 1 , 0
    1976      .2       0    1976     .15       0  2686.2     .15       0
  4309.9     .15       0  4971.6     .08       0  5026.2     .15       0
  7032.5     .15       0  7930.3      .2       0
Bank Sta=4971.6,5026.2
XS Rating Curve= 0
Exp/Cntr=.3,.1

Type RM Length L Ch R = 1 ,228588.3,1089.6,1335.2,929.36
BEGIN DESCRIPTION:
Cross Section XS167
END DESCRIPTION:
XS GIS Cut Line= 3
    3017990.9389   13967881.4367    3017950.0873   13964463.5239
    3018399.4544   13962339.2434
#Sta/Elev= 30
  1786.2   178.6  1786.4  178.59  1966.2   173.6  2226.2   170.7  2326.2   172.6
  2486.2   171.8  2726.2   164.5  2926.2   162.7  3006.2   159.8  3106.2   160.8
  3426.2   158.3  4026.2   160.2  4226.2   153.6  4346.2   151.6  4586.2   156.2
  4626.2   154.7  4972.7  155.08  4982.1  146.08  5000.2  142.08  5017.8  146.05
  5043.4  155.01  5150.4  153.37  5204.4   155.3  5384.4   155.7  5584.4   151.7
  5784.4   152.2  5884.4   158.8  6544.4   168.8  6924.4     190  7375.6   188.6
#Mann= 6 , 1 , 0
  1786.2      .2       0  1786.2     .09       0  1786.4     .15       0
  4972.7     .08       0  5043.4     .15       0  7375.6      .2       0
Bank Sta=4972.7,5043.4
XS Rating Curve= 0
Exp/Cntr=.3,.1

Type RM Length L Ch R = 1 ,227253.1,1525.82,2099.7,1767.1
BEGIN DESCRIPTION:
Cross Section XS166
END DESCRIPTION:
XS GIS Cut Line= 3
    3018930.5245   13967255.0463    3018930.5245   13964204.7974
     3019039.462   13961603.9155
#Sta/Elev= 30
    1672     175    1832   174.6    1972   175.9    2092   171.1    2332   157.8
    2532     155    3112   154.8    3152     156  3501.5  156.29    3612   156.5
    3692     155    3772   155.7    4072   151.1    4192   150.8    4492   155.5
  4722.2   154.8  4842.2   156.4  4976.7  154.58  4981.9  146.99  4982.1   145.6
  4982.9  150.03    4998  141.98  5017.9  145.84  5029.2  152.51  5402.2   155.1
  5502.2   163.2  5662.2   173.8  5762.2   177.8  6622.2   186.1  7325.4   195.9
#Mann= 4 ,-1 , 0
    1672     .15       0  3501.5     .15       0  4976.7     .08       0
  5029.2     .15       0
Bank Sta=4976.7,5029.2
XS Rating Curve= 0
Exp/Cntr=.3,.1

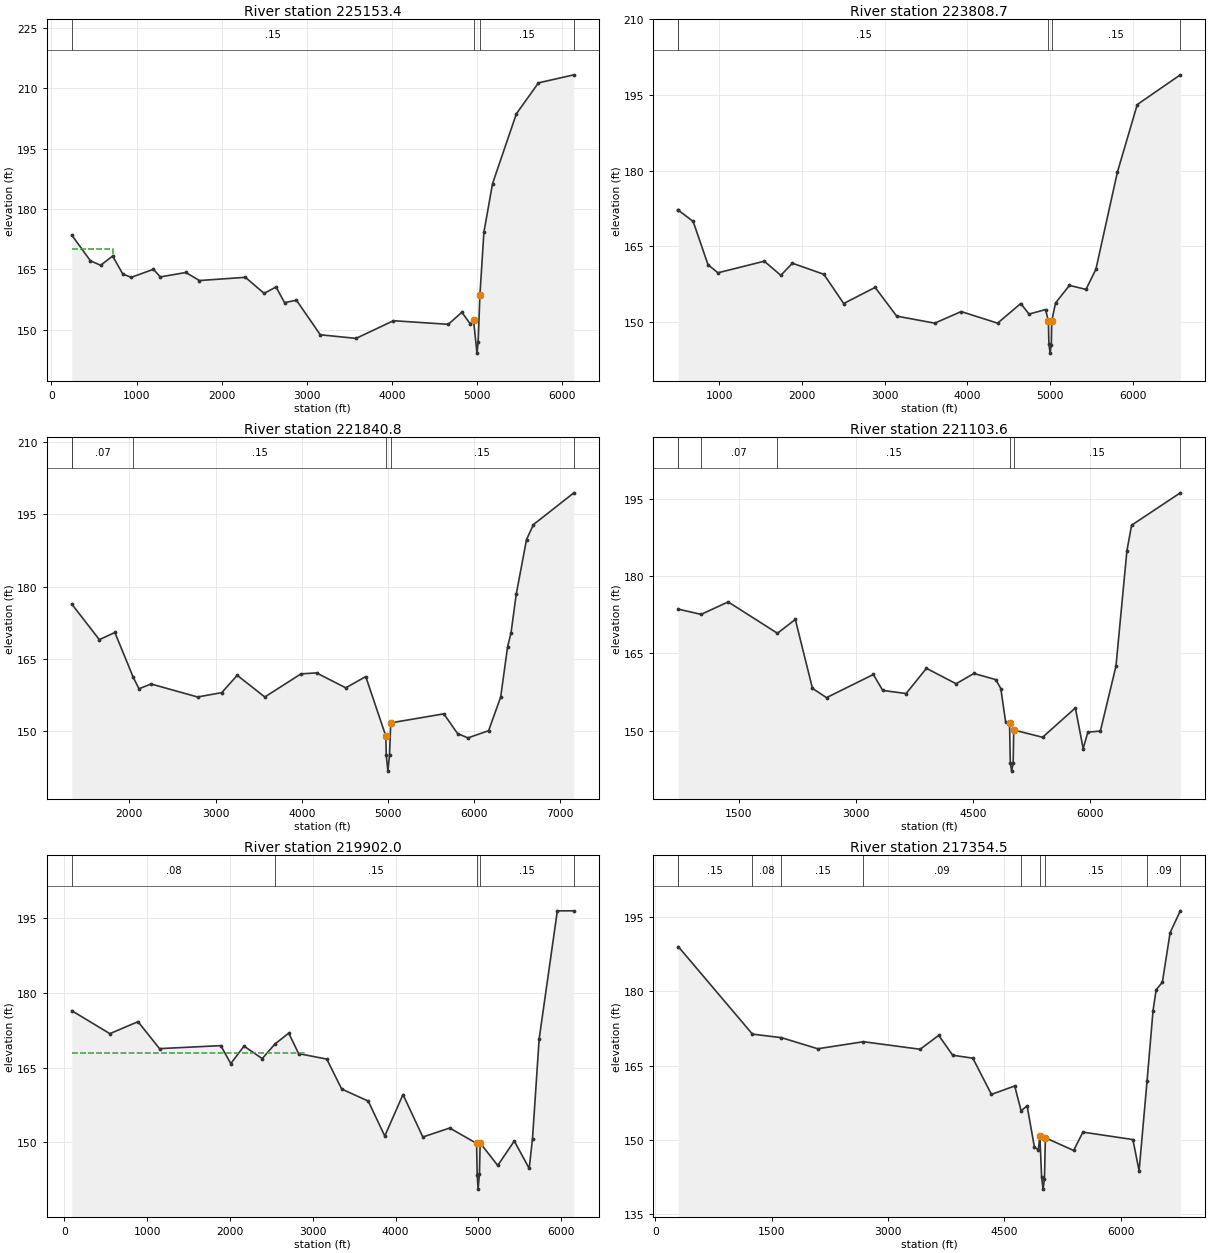
Type RM Length L Ch R = 1 ,225153.4,889.64,1344.7,1513.06
BEGIN DESCRIPTION:
Cross Section XS165
Ineffective at Sta 3940 based on topo upstream of the cross section
END DESCRIPTION:
XS GIS Cut Line= 3
    3019764.7548   13967694.4095    3020658.1029   13963504.9149
    3020619.0551   13961889.8764
#Sta/Elev= 30
   238.8   173.5   458.8   167.1   578.8     166   718.8   168.3   838.8   163.8
   938.8     163  1198.8     165  1278.8   163.1  1578.8   164.2  1738.8   162.2
  2278.8     163  2498.8     159  2638.8   160.6  2738.8   156.7  2878.8   157.3
  3158.8   148.7  3578.8   147.8  4018.8   152.2  4662.5   151.3  4822.5   154.3
  4921.3  151.39  4959.4  152.34    5000  144.13  5013.4  146.84  5034.4   158.6
  5081.1  174.19  5182.5   186.3  5462.5   203.7  5722.5   211.4    6138   213.4
#Mann= 4 ,-1 , 0
   238.8     .15       0  4959.4     .08       0  5034.4     .15       0
    6138      .2       0
#XS Ineff= 2 , 0
       0     720     170               0
Permanent Ineff=
       F       F
Bank Sta=4959.4,5034.4
XS Rating Curve= 0
Exp/Cntr=.3,.1

Type RM Length L Ch R = 1 ,223808.7,732.17,1967.9,1689.94
BEGIN DESCRIPTION:
Cross Section XS164
END DESCRIPTION:
XS GIS Cut Line= 3
    3020292.2427   13967350.3666    3021926.3046   13963020.1025
    3022852.2731   13961917.1107
#Sta/Elev= 30
     505   172.1   507.4  172.11     685   169.9     865   161.3     985   159.7
    1545     162    1745   159.2    1885   161.6    2265   159.4    2505   153.6
    2885   156.8    3145   151.1    3605   149.7    3925     152    4365   149.7
    4645   153.6    4745   151.5    4945   152.4  4978.7  150.12  4985.3  145.56
  4999.4  143.75  5014.6  145.43  5019.5   150.1    5065   153.7  5233.3   157.2
  5433.3   156.4  5553.3   160.4  5813.3   179.7  6053.3   193.1  6573.5     199
#Mann= 6 , 1 , 0
     505      .2       0     505     .07       0   507.4     .15       0
  4978.7     .08       0  5019.5     .15       0  6573.5      .2       0
Bank Sta=4978.7,5019.5
XS Rating Curve= 0
Exp/Cntr=.3,.1

Type RM Length L Ch R = 1 ,221840.8,661.87,737.2,574.72
BEGIN DESCRIPTION:
Cross Section XS163
END DESCRIPTION:
XS GIS Cut Line= 3
    3020611.8953   13967863.8376    3022062.4765   13964858.4221
    3023928.0305   13963210.7431
#Sta/Elev= 30
  1331.7   176.4  1651.7     169  1831.7   170.5    2044  161.23  2111.7   158.8
  2251.7   159.8  2791.7   157.1  3071.7     158  3251.7   161.6  3571.7   157.1
  3991.7   161.9  4171.7   162.1  4511.7     159    4743  161.34    4976  148.98
  4981.1  144.95  5000.2   141.7  5019.2  145.09    5033  151.72  5648.9   153.6
  5808.9   149.5  5928.9   148.6  6168.9   150.1  6308.9   157.1  6388.9   167.5
  6428.9   170.4  6488.9   178.4  6608.9   189.8  6688.9   192.9  7157.9   199.5
#Mann= 6 , 1 , 0
  1331.7      .2       0  1331.7     .07       0    2044     .15       0
    4976     .08       0    5033     .15       0  7157.9      .2       0
Bank Sta=4976,5033
XS Rating Curve= 0
Exp/Cntr=.3,.1

Type RM Length L Ch R = 1 ,221103.6,1036.74,1201.6,1124.96
BEGIN DESCRIPTION:
Cross Section XS162
END DESCRIPTION:
XS GIS Cut Line= 3
     3020755.227   13968861.8738    3022498.2263   13965498.4297
    3024091.4367   13963387.7664
#Sta/Elev= 30
   727.1   173.6  1020.3  172.58  1367.1     175  1998.3  168.91  2227.1   171.6
  2447.1   158.2  2627.1   156.4  3227.1   160.9  3347.1   157.8  3647.1   157.2
  3907.1   162.1  4287.1   159.1  4515.3   161.1  4795.3   159.9  4860.1  158.17
  4922.5  151.59  4971.9  151.46  4981.8  143.72  4998.7  142.12  5018.1  143.64
  5025.6  150.11  5395.3   148.7  5815.3   154.4  5915.3   146.5  5975.3   149.7
  6135.3   149.9  6335.3   162.5  6475.3   184.9  6535.3   189.9  7159.8   196.2
#Mann= 7 , 1 , 0
   727.1      .2       0   727.1     .08       0  1020.3     .07       0
  1998.3     .15       0  4971.9     .08       0  5025.6     .15       0
  7159.8      .2       0
Bank Sta=4971.9,5025.6
XS Rating Curve= 0
Exp/Cntr=.3,.1

Type RM Length L Ch R = 1 ,219902.0,1051.98,2547.5,868.81
BEGIN DESCRIPTION:
Cross Section XS161
Ineffective at Sta 2900 based on topo downstream of the cross section
END DESCRIPTION:
XS GIS Cut Line= 3
    3021327.1486   13969883.1625    3023451.4291   13965934.1796
    3024554.4209   13964803.9534
#Sta/Elev= 30
    90.3   176.4   550.3   171.8   890.3   174.2  1150.3   168.8  1890.3   169.4
  2010.3   165.8  2170.3   169.3  2390.3   166.8    2543  169.71  2710.3   171.9
  2830.3   167.8  3170.3   166.7  3350.3   160.7  3670.3   158.3  3870.3   151.3
  4090.3   159.6  4330.3   151.1  4654.4   152.9  4979.3  149.82 4986.21  143.55
  4997.2  140.66  5013.6  143.68  5022.3  149.91  5234.4   145.4  5434.4   150.3
  5614.4   144.8  5654.4   150.8  5734.4   170.7  5954.4   196.4  6153.6   196.4
#Mann= 5 ,-1 , 0
    90.3     .08       0    2543     .15       0  4979.3     .08       0
  5022.3     .15       0  6153.6      .2       0
#XS Ineff= 2 , 0
       0    2900     168               0
Permanent Ineff=
       F       F
Bank Sta=4979.3,5022.3
XS Rating Curve= 0
Exp/Cntr=.3,.1

Type RM Length L Ch R = 1 ,217354.5,1203.03,3435.6,1686.85
BEGIN DESCRIPTION:
Cross Section XS160
END DESCRIPTION:
XS GIS Cut Line= 3
    3021899.0703    13970890.834    3024758.6786   13965770.7734
    3024881.2333   13965171.6173
#Sta/Elev= 30
   294.8     189  1251.8  171.35  1625.3  170.64  2094.8   168.4  2683.5  169.82
  3414.8   168.3  3654.8   171.1  3834.8   167.1  4094.8   166.5  4334.8   159.2
  4634.8   160.9  4717.3  155.89  4794.8   156.9  4889.2  148.55  4939.6  148.05
  4959.7  150.84  4981.5  142.61  5000.4  140.11  5018.7  142.16  5030.5  150.46
  5394.8   147.9  5514.8   151.6  6159.3   150.1  6239.3   143.8  6342.3  161.96
  6419.3   176.1  6459.3   180.3  6539.3   181.8  6639.3   191.8  6770.9   196.2
#Mann= 10 , 1 , 0
   294.8      .2       0   294.8     .15       0  1251.8     .08       0
  1625.3     .15       0  2683.5     .09       0  4717.3     .15       0
  4959.7     .08       0  5030.5     .15       0  6342.3     .09       0
  6770.9      .2       0
Bank Sta=4959.7,5030.5
XS Rating Curve= 0
Exp/Cntr=.3,.1

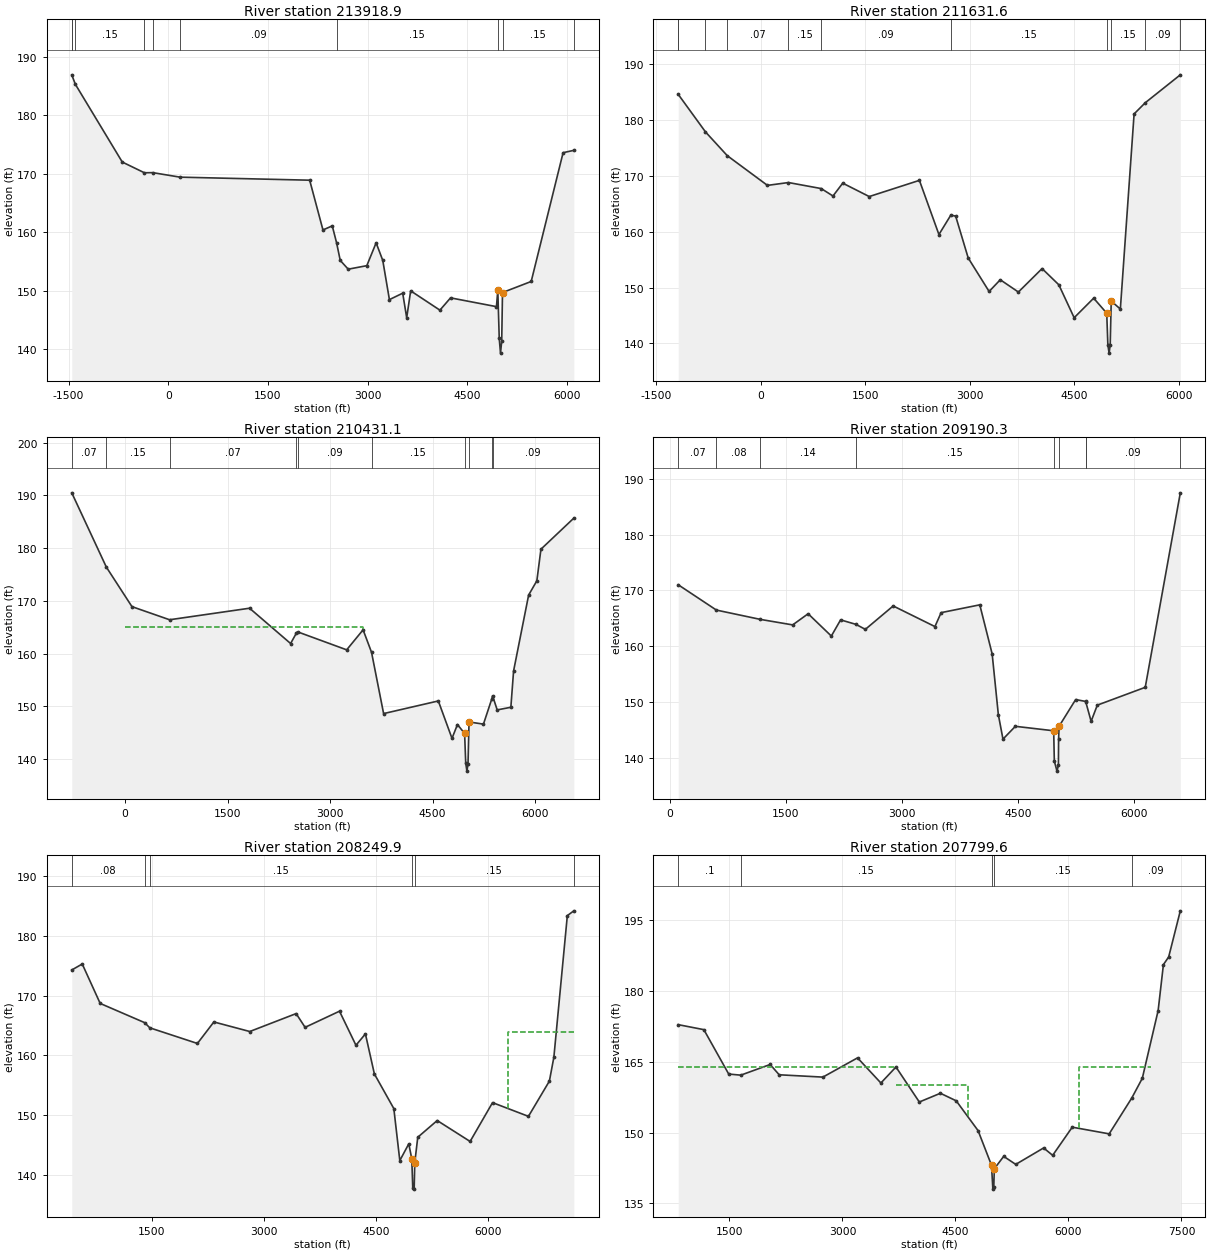
Type RM Length L Ch R = 1 ,213918.9,812.2,2287.3,1452.02
BEGIN DESCRIPTION:
Cross Section XS159.5
END DESCRIPTION:
XS GIS Cut Line= 3
    3022073.6491   13971048.5886    3025967.1533   13966206.0427
    3026648.5165   13965050.1587
#Sta/Elev= 30
 -1451.3   186.9 -1397.7  185.29  -691.3     172  -358.4  170.17  -231.9  170.19
   178.2  169.42  2128.7   168.9  2328.7   160.4  2468.7   161.1  2533.6  158.21
  2588.7   155.2  2708.7   153.7  2988.7   154.3  3128.7   158.2  3228.7   155.2
  3328.7   148.5  3528.7   149.6  3588.7   145.4  3648.7     150  4088.7   146.7
  4248.7   148.8  4939.6   147.3  4959.7  150.09  4981.5  141.86  5000.4  139.36
  5018.7  141.41  5030.5  149.71  5462.4   151.6  5942.4   173.6  6104.1     174
#Mann= 10 , 1 , 0
 -1451.3      .2       0 -1451.3     .07       0 -1397.7     .15       0
  -358.4     .07       0  -231.9     .15       0   178.2     .09       0
  2533.6     .15       0  4959.7     .08       0  5030.5     .15       0
  6104.1      .2       0
Bank Sta=4959.7,5030.5
XS Rating Curve= 0
Exp/Cntr=.3,.1

Type RM Length L Ch R = 1 ,211631.6,976.71,1200.5,987.04
BEGIN DESCRIPTION:
Cross Section XS159
END DESCRIPTION:
XS GIS Cut Line= 2
    3022212.2655   13971217.6464    3027373.1777    13966192.906
#Sta/Elev= 30
 -1180.2   184.6  -789.4  177.88  -476.6  173.62    99.8   168.3   401.1  168.81
   871.4  167.73  1039.8   166.4  1179.8   168.7  1559.8   166.3  2279.8   169.2
  2559.8   159.5  2730.2  162.97  2799.8   162.8  2979.8   155.3  3279.8   149.3
  3439.8   151.4  3699.8   149.2  4039.8   153.4  4279.8   150.5  4499.8   144.6
  4779.8   148.1  4967.2  145.41  4983.2   139.8  5000.9  138.26  5016.9  139.67
  5031.7  147.59  5162.6  146.15  5359.8   181.1  5519.9   183.1  6022.8   188.1
#Mann= 11 , 1 , 0
 -1180.2      .2       0 -1180.2     .07       0  -789.4     .15       0
  -476.6     .07       0   401.1     .15       0   871.4     .09       0
  2730.2     .15       0  4967.2     .08       0  5031.7     .15       0
  5519.9     .09       0  6022.8      .2       0
Bank Sta=4967.2,5031.7
XS Rating Curve= 0
Exp/Cntr=.3,.1

Type RM Length L Ch R = 1 ,210431.1,1256.89,1240.8,1040.02
BEGIN DESCRIPTION:
Cross Section XS158
Ineffective at Sta 3480 based on topo upstream of the cross section
END DESCRIPTION:
XS GIS Cut Line= 3
    3022961.2105   13972021.0602    3027305.0918   13967568.2415
    3028162.9743   13966846.5308
#Sta/Elev= 30
  -777.4   190.5  -271.6   176.4   102.6   168.9   652.8  166.41  1822.6   168.6
  2422.6   161.9  2507.1  163.87  2523.7  164.12  3242.6   160.7  3482.6   164.5
  3606.1  160.23  3782.6   148.6  4582.6     151  4782.6   143.9  4862.4  146.52
  4967.2  144.83  4983.2  139.22  5000.9  137.68  5016.9  139.09  5031.7  147.01
  5242.6   146.6  5363.9  151.36  5376.2  151.98  5443.3   149.3  5643.3   149.8
  5683.3   156.7  5903.3   171.1  6023.3   173.8  6083.3   179.8  6564.4   185.7
#Mann= 10 ,-1 , 0
  -777.4     .07       0  -271.6     .15       0   652.8     .07       0
  2507.1     .14       0  2523.7     .09       0  3606.1     .15       0
  4967.2     .08       0  5031.7     .15       0  5363.9     .15       0
  5376.2     .09       0
#XS Ineff= 2 , 0
       0    3480     165               0
Permanent Ineff=
       F       F
Bank Sta=4967.2,5031.7
XS Rating Curve= 0
Exp/Cntr=.3,.1

Type RM Length L Ch R = 1 ,209190.3,819.38,940.4,813.68
BEGIN DESCRIPTION:
Cross Section XS157
Ineffective at Sta 4000 based on topo upstream of the cross section
END DESCRIPTION:
XS GIS Cut Line= 2
    3024908.4676   13972620.2162    3028721.2787   13967363.9837
#Sta/Elev= 30
   109.5     171     603  166.46  1170.9  164.79  1589.5   163.8  1789.5   165.8
  2089.5   161.8  2209.5   164.7  2407.4   163.9  2529.5     163  2889.5   167.2
  3429.5   163.5  3509.5     166  4009.5   167.4  4169.5   158.6  4249.5   147.7
  4309.5   143.3  4469.5   145.6  4965.3   144.8  4973.6  139.36  5008.2  137.56
  5026.4  138.63  5028.7  143.26    5035  145.61  5249.5   150.4  5377.3  150.07
  5380.5  149.97  5449.5   146.5  5529.5   149.4  6149.5   152.6    6603   187.5
#Mann= 9 ,-1 , 0
   109.5     .07       0     603     .08       0  1170.9     .14       0
  2407.4     .15       0  4965.3     .08       0    5035     .15       0
  5377.3     .15       0  5380.5     .09       0    6603      .2       0
#XS Ineff= 2 , 0
       0    4000     166               0
Permanent Ineff=
       F       F
Bank Sta=4965.3,5035
XS Rating Curve= 0
Exp/Cntr=.3,.1

Type RM Length L Ch R = 1 ,208249.9,354.97,450.3,230
BEGIN DESCRIPTION:
Cross Section 156
Ineffective at Sta 4000 based on topo upstream of the cross section
END DESCRIPTION:
XS GIS Cut Line= 3
    3025766.3501   13973083.2004    3027890.6306   13969828.6938
    3029606.3956   13967581.8587
#Sta/Elev= 30
   430.9   174.3   570.9   175.3   810.9   168.7  1406.2  165.48  1474.1  164.62
  2110.9     162  2330.9   165.6  2810.9     164  3430.9     167  3550.9   164.7
  4010.9   167.4  4230.9   161.7  4357.3   163.6  4477.3   156.9  4737.3   151.1
  4817.3   142.4  4937.3   145.2  4977.2   142.7  4990.4  137.87  5009.2  137.62
  5017.3  142.04  5057.3   146.3  5317.3   149.1  5757.3   145.6  6057.3   152.1
  6537.3   149.8  6817.3   155.7  6877.3   159.7  7057.3   183.4  7144.4   184.2
#Mann= 6 ,-1 , 0
   430.9     .08       0  1406.2      .1       0  1474.1     .15       0
  4977.2     .08       0  5017.3     .15       0  7144.4      .2       0
#XS Ineff= 2 , 0
       0    4050     164    6270       0     164
Permanent Ineff=
       F       F
Bank Sta=4977.2,5017.3
XS Rating Curve= 0
Exp/Cntr=.3,.1

Type RM Length L Ch R = 1 ,207799.6,354.97,281.5,157.4
XS GIS Cut Line= 2
       3026318.7     13973114.66      3029883.32     13967483.78
#Sta/Elev= 30
     820172.8708    1160171.8128    1490  162.41    1650162.1729    2040164.4339
    2160162.2519    2740  161.76    3200165.8369    3510160.5131    3710163.9028
    4020156.4856    4300158.3385    4510156.7346    4800150.4253 4978.26  143.09
 4996.25  138.03 5008.46  138.48 5015.53  142.35    5140144.9696    5300143.2703
    5670146.7528    5790145.1892    6050151.1544    6540149.7386    6840157.3296
    6980161.5141    7190175.8542    7260185.5893    7330187.2188 7484.34196.9848
#Mann= 5 ,-1 , 0
     820      .1       0    1650     .15       0 4978.26     .08       0
 5015.53     .15       0    6840     .09       0
#XS Ineff= 3 ,-1
     820    3710     164    3710    4660     160    6140    7100     164
Permanent Ineff=
       F       F       F
Bank Sta=4978.26,5015.53
XS Rating Curve= 0
Exp/Cntr=.5,.3