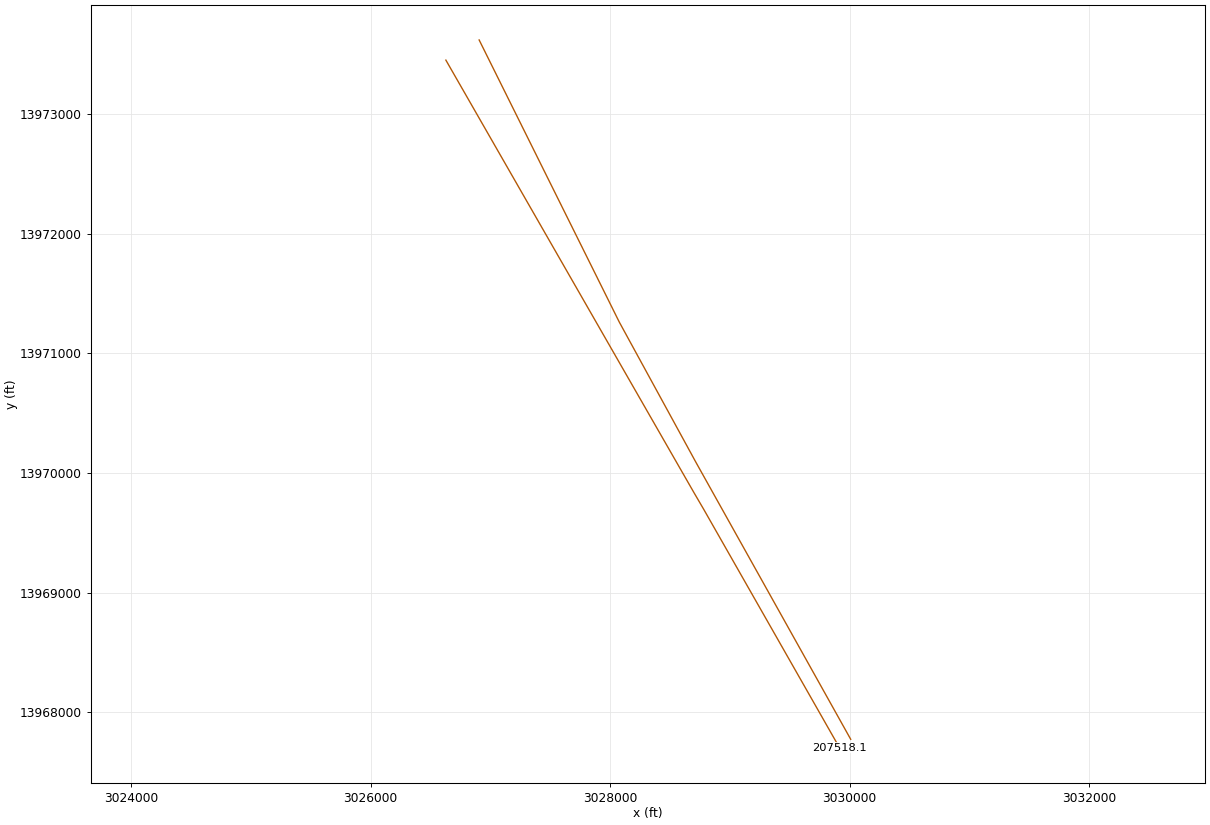
HEC-RAS study J100-00-00.prj: J100-00-00

--- J100-00-00.g01 (geometry) --- (continued)

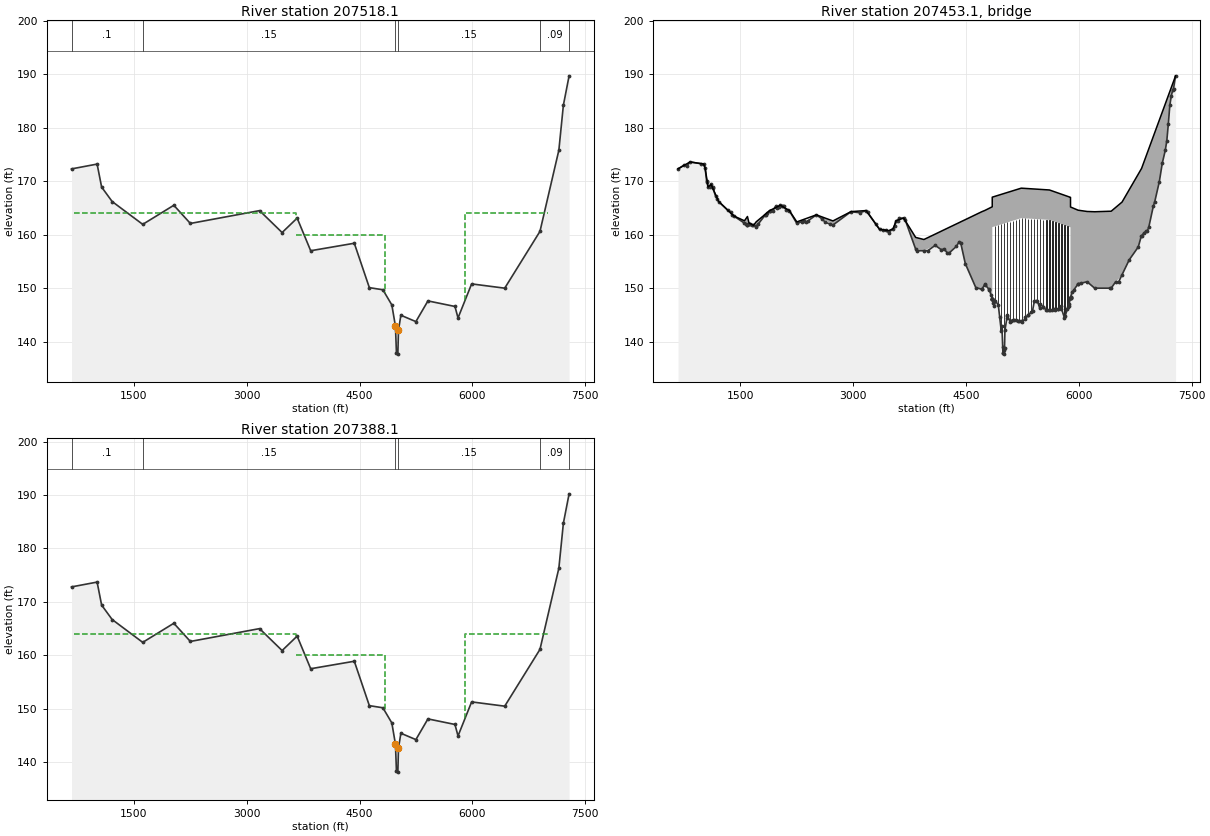
Type RM Length L Ch R = 1 ,207518.1,130,130,130
BEGIN DESCRIPTION:
Upstream Section of Tomball Parkway SH249 (149)
Ineffective at Sta 3650 based on topo upstream of the cross section
END DESCRIPTION:
XS GIS Cut Line= 4
    3026627.9005   13973448.3687    3028696.7172   13969841.5502
    3028783.4454   13969693.1485    3029914.8202   13967706.7713
#Sta/Elev= 30
   670.2   172.3  1010.2   173.2  1070.2   168.9  1210.2   166.2  1616.8  161.93
  2030.2   165.5  2250.2   162.1  3170.2   164.5  3470.2   160.4  3670.2   163.1
  3850.2     157  4430.2   158.4  4630.2   150.1  4810.2   149.7  4929.1  146.87
  4977.3  142.89  4990.4  137.92  5009.2  137.67  5017.3  142.09  5049.1  144.94
    5249  143.75  5409.2  147.62  5768.7  146.58  5809.2  144.43  5990.2   150.8
  6430.2     150    6899  160.62  7150.2   175.8  7210.2   184.2  7286.4   189.7
#Mann= 6 ,-1 , 0
   670.2      .1       0  1616.8     .15       0  4977.3     .08       0
  5017.3     .15       0    6899     .09       0  7286.4      .2       0
#XS Ineff= 3 ,-1
     700    3650     164    3650    4835     160    5900    7000     164
Permanent Ineff=
       F       F       F
Bank Sta=4977.3,5017.3
XS Rating Curve= 0
Exp/Cntr=.5,.3

Type RM Length L Ch R = 3 ,207453.1,,,
BEGIN DESCRIPTION:
TOMBALL PARKWAY SH 249(149)
Structure ID: J100-00-00-09
Circular piers, twin-cylinder piers without diaphragm
END DESCRIPTION:
Node Name=Tomball Parkway
Bridge Culvert--1,0,-1,-1, 0
Deck Dist Width WeirC Skew NumUp NumDn MinLoCord MaxHiCord MaxSubmerge Is_Ogee
10,110,2.6,0, 60, 60, , , .95, 0, 1,1,,
   670.2   830.2  1010.2  1030.2  1070.2  1110.2  1210.2  1413.7  1553.7  1593.7
  1613.7  1673.7  1710.2  1890.2  2030.2  2150.2  2250.2  2510.2  2730.2  2970.2
  3170.2  3350.2  3470.2  3530.2  3570.2  3670.2  3830.2    3940  4090.2  4270.2
  4410.2  4430.2  4490.2  4630.2  4710.2  4750.2  4810.2 4848.59  4848.7 4849.51
  4849.6  5234.4  5609.1 5888.99  5889.1  5889.4 5889.51  5990.2  6110.2  6210.2
  6430.2  6574.6  6790.2  6834.6  6930.2  7070.2  7150.2  7170.2  7210.2  7286.4
   172.3   173.6  173.21  172.51  168.91  169.41  166.21  163.49   162.6   163.4
   162.2  161.74  162.41  164.51  165.51  164.51  162.39  163.71  162.57  164.31
  164.51  161.01  160.75  161.11  162.61  163.11  159.49   159.1  160.11  161.33
  162.27  162.41  162.81  163.76   164.3  164.53  164.95  165.22  167.02  167.02
  167.02   168.7  168.36  166.98  166.98  166.98  165.18  164.58  164.34  164.29
  164.39   166.1  171.32   172.4  176.06  181.42  184.48  185.25  186.78   189.7
   172.3   173.6   173.2   172.5   168.9   169.4   166.2  163.48  162.15  161.82
  161.92  161.73   161.5   164.5   165.5   164.5   162.1   163.7   161.8   164.3
   164.5     161   160.4   161.1   162.6   163.1   157.3     157     158   156.5
   158.7   158.4   154.6   150.1   149.8   150.7   149.7  147.97  147.96  147.92
  161.42   163.1  162.76  161.38  148.23  148.25  148.26   150.8   151.2     150
     150   152.5   157.7  159.78   161.4   169.9   175.8   177.6   184.2   189.7
   670.2   830.2  1010.2  1030.2  1050.2  1070.2  1110.2  1210.2  1553.7  1593.7
  1613.7  1710.2  1890.2  2030.2  2150.2  2250.2  2510.2  2730.2  2970.2  3170.2
  3350.2  3470.2  3530.2  3570.2  3670.2  3830.2    3940  4090.2  4270.2  4410.2
  4430.2  4490.2  4630.2  4710.2  4750.2  4810.2 4848.59  4848.7 4849.51  4849.6
  5234.4  5609.1 5888.99  5889.1  5889.4 5889.51  5990.2  6110.2  6210.2  6430.2
  6574.6  6790.2  6834.6  6930.2  7070.2  7110.2  7150.2  7170.2  7210.2  7286.4
  172.83  174.13  173.73  173.03  170.63  169.43  169.93  166.73  162.68   163.4
  162.45  162.41  165.03  166.03  165.03  162.63  164.23  162.57  164.83  165.03
  161.53  160.93  161.63  163.13  163.63  159.49   159.1  160.11  161.33  162.27
  162.41  162.81  163.76   164.3  164.53  164.95  165.22  167.02  167.02  167.02
   168.7  168.36  166.98  166.98  166.98  165.18  164.58  164.34  164.29  164.39
   166.1  171.32   172.4  176.06  181.42  182.95  184.48  185.25  186.78  190.23
  172.83  174.13  173.73  173.03  170.63  169.43  169.93  166.73  162.68  162.35
  162.45  162.03  165.03  166.03  165.03  162.63  164.23  162.33  164.83  165.03
  161.53  160.93  161.63  163.13  163.63  157.83  157.53  158.53  157.03  159.23
  158.93  155.13  150.63  150.33  151.23  150.23   148.5  148.49  148.45  161.95
  163.63  163.29  161.91  148.76  148.78  148.79  151.33  151.73  150.53  150.53
  153.03  158.23  160.31  161.93  170.43  173.93  176.33  178.13  184.73  190.23
Pier Skew, UpSta & Num, DnSta & Num=  ,4889, 2 ,4889, 2 , 0 , 0 , 0 ,,
       2       2
  146.56  162.67
       2       2
  147.09   163.2
Pier Skew, UpSta & Num, DnSta & Num=  ,4929.1, 2 ,4929.1, 2 , 0 , 0 , 0 ,,
       2       2
  145.75  162.91
       2       2
  146.28  163.44
Pier Skew, UpSta & Num, DnSta & Num=  ,4969.1, 2 ,4969.1, 2 , 0 , 0 , 0 ,,
       2       2
  141.06  163.11
       2       2
  141.59  163.64
Pier Skew, UpSta & Num, DnSta & Num=  ,5009, 2 ,5009, 2 , 0 , 0 , 0 ,,
       2       2
     137   163.3
       2       2
  137.53  163.83
Pier Skew, UpSta & Num, DnSta & Num=  ,5049.1, 2 ,5049.1, 2 , 0 , 0 , 0 ,,
       2       2
  143.72  163.49
       2       2
  144.25  164.02
Pier Skew, UpSta & Num, DnSta & Num=  ,5089, 2 ,5089, 2 , 0 , 0 , 0 ,,
       2       2
  142.76  163.65
       2       2
  143.29  164.18
Pier Skew, UpSta & Num, DnSta & Num=  ,5129.1, 2 ,5129.1, 2 , 0 , 0 , 0 ,,
       2       2
  143.06  163.82
       2       2
  143.59  164.35
Pier Skew, UpSta & Num, DnSta & Num=  ,5169.2, 2 ,5169.2, 2 , 0 , 0 , 0 ,,
       2       2
  143.02  163.94
       2       2
  143.55  164.47
Pier Skew, UpSta & Num, DnSta & Num=  ,5209, 2 ,5209, 2 , 0 , 0 , 0 ,,
       2       2
  142.86  164.04
       2       2
  143.39  164.57
Pier Skew, UpSta & Num, DnSta & Num=  ,5249, 2 ,5249, 2 , 0 , 0 , 0 ,,
       2       2
  142.75   164.1
       2       2
  143.28  164.63
Pier Skew, UpSta & Num, DnSta & Num=  ,5289.1, 2 ,5289.1, 2 , 0 , 0 , 0 ,,
       2       2
  143.28  164.11
       2       2
  143.81  164.64
Pier Skew, UpSta & Num, DnSta & Num=  ,5329.1, 2 ,5329.1, 2 , 0 , 0 , 0 ,,
       2       2
  143.91  164.12
       2       2
  144.44  164.65
Pier Skew, UpSta & Num, DnSta & Num=  ,5369.1, 2 ,5369.1, 2 , 0 , 0 , 0 ,,
       2       2
  144.55  164.12
       2       2
  145.08  164.65
Pier Skew, UpSta & Num, DnSta & Num=  ,5409.2, 2 ,5409.2, 2 , 0 , 0 , 0 ,,
       2       2
  146.55  164.12
       2       2
  147.08  164.65
Pier Skew, UpSta & Num, DnSta & Num=  ,5449.1, 2 ,5449.1, 2 , 0 , 0 , 0 ,,
       2       2
  146.53  164.09
       2       2
  147.06  164.62
Pier Skew, UpSta & Num, DnSta & Num=  ,5489.2, 2 ,5489.2, 2 , 0 , 0 , 0 ,,
       2       2
  145.89  164.03
       2       2
  146.42  164.56
Pier Skew, UpSta & Num, DnSta & Num=  ,5529.2, 2 ,5529.2, 2 , 0 , 0 , 0 ,,
       2       2
  145.45  163.97
       2       2
  145.98   164.5
Pier Skew, UpSta & Num, DnSta & Num=  ,5569.2, 2 ,5569.2, 2 , 0 , 0 , 0 ,,
       2       2
  144.88  163.86
       2       2
  145.41  164.39
Pier Skew, UpSta & Num, DnSta & Num=  ,5609.1, 2 ,5609.1, 2 , 0 , 0 , 0 ,,
       2       2
  144.92  163.76
       2       2
  145.45  164.29
Pier Skew, UpSta & Num, DnSta & Num=  ,5649.2, 2 ,5649.2, 2 , 0 , 0 , 0 ,,
       2       2
  144.96  163.62
       2       2
  145.49  164.15
Pier Skew, UpSta & Num, DnSta & Num=  ,5689.2, 2 ,5689.2, 2 , 0 , 0 , 0 ,,
       2       2
  144.97  163.46
       2       2
   145.5  163.99
Pier Skew, UpSta & Num, DnSta & Num=  ,5729.2, 2 ,5729.2, 2 , 0 , 0 , 0 ,,
       2       2
  145.17   163.3
       2       2
   145.7  163.83
Pier Skew, UpSta & Num, DnSta & Num=  ,5769.3, 2 ,5769.3, 2 , 0 , 0 , 0 ,,
       2       2
  145.14   163.1
       2       2
  145.67  163.63
Pier Skew, UpSta & Num, DnSta & Num=  ,5809.2, 2 ,5809.2, 2 , 0 , 0 , 0 ,,
       2       2
  143.47  162.91
       2       2
     144  163.44
Pier Skew, UpSta & Num, DnSta & Num=  ,5849.3, 2 ,5849.3, 2 , 0 , 0 , 0 ,,
       2       2
  145.11  162.65
       2       2
  145.64  163.18
Abutment Skew #Up #Dn= , 2 , 2
  4849.4  4863.7
  161.42  147.28
  4849.4  4863.7
  161.95  147.81
Abutment Skew #Up #Dn= , 2 , 2
  5863.7 5889.19
  146.72  161.38
  5863.7 5889.19
  147.25  161.91
BR Coef= 1 , 1 , 1 ,1.05, 0 ,,,.8,-1,1.2,1,
WSPro=,,,, 1 ,,,, 0 ,,,, 0 ,,,,-1 ,-1 ,-1 , 0 , 0 , 0 , 0 , 0
BR U #Sta/Elev= 198
   670.2   172.3   750.2     173   790.2   172.9   830.2   173.6   973.7  173.28
  1010.2   173.2  1030.2   172.5  1050.2   170.1  1053.7  169.89  1070.2   168.9
  1090.2   168.9  1110.2   169.4  1130.2   168.9  1133.7  168.75  1170.2   167.2
  1193.7  166.61  1210.2   166.2  1330.2   164.6  1370.2   164.3  1390.2   163.7
  1413.7  163.48  1553.7  162.15  1573.7  161.96  1590.2   161.8  1593.7  161.82
  1613.7  161.92  1616.8  161.93  1630.2     162  1653.7  161.85  1673.7  161.73
  1710.2   161.5  1713.7  161.56  1733.7  161.93  1830.2   163.7  1833.7  163.75
  1853.7  164.01  1890.2   164.5  1893.7   164.5  1930.2   164.5  1970.2   165.3
  1973.7  165.23  1990.2   164.9  2013.7  165.25  2030.2   165.5  2053.7  165.44
  2070.2   165.4  2073.7  165.33  2110.2   164.6  2133.7  164.54  2150.2   164.5
  2250.2   162.1  2313.7  162.42  2350.2   162.6  2370.2   162.3  2393.7  162.54
  2510.2   163.7  2590.2   162.9  2630.2   162.3  2693.7  161.98  2730.2   161.8
  2970.2   164.3  3090.2   164.1  3170.2   164.5  3190.2   164.2    3300     162
  3350.2     161    3400  160.88  3430.2   160.8  3470.2   160.4  3530.2   161.1
  3550.2   161.6  3570.2   162.6  3590.2   162.6  3610.2   163.1  3670.2   163.1
  3690.2   162.8  3830.2   157.3  3850.2     157    3940     157  3990.2     157
  4090.2     158  4170.2   157.2  4210.2   157.3  4250.2   156.6  4270.2   156.5
  4370.2   157.8  4410.2   158.7  4430.2   158.4  4490.2   154.6  4630.2   150.1
  4710.1   149.8  4710.2   149.8  4750.2   150.7  4755.8  150.61  4801.1  149.85
  4810.2   149.7  4830.2   148.8 4848.59  147.97  4848.7  147.96 4848.81  147.96
  4849.4  147.93 4849.51  147.92  4849.6  147.92  4863.7  147.28  4876.7  146.69
    4889  147.64  4929.1  146.87  4946.7   144.7  4969.1  141.94  4977.3  142.89
  4987.9  139.03  4990.4  137.92  4997.8   137.9    5009  138.35  5009.2  137.67
  5012.1  138.87  5017.3  142.09  5043.4  144.43  5049.1  144.94  5049.5  144.74
    5089  143.74  5097.3  143.94  5129.1  144.06  5138.8  144.05  5169.2  144.03
  5191.9  143.86    5209  143.86  5234.4  143.79    5249  143.75  5289.1  144.29
  5289.8  144.56    5329  144.92  5329.1  144.92  5369.1  145.57  5385.2  145.82
  5409.2  147.62  5426.9   147.6  5449.1  147.57  5481.4  146.23  5489.2  146.99
  5525.1  146.51  5529.2  146.46  5569.2  145.87  5575.8  145.96  5609.1  145.92
  5622.7  145.93  5649.2  145.96  5671.8  146.07  5689.2  145.96  5720.6  146.13
  5729.2  146.18  5768.7  146.58  5769.3  146.18  5809.2  144.43  5818.2  144.82
  5849.3  146.15  5859.7  146.55  5863.7  146.72  5870.2     147 5888.99  148.22
  5889.1  148.23  5889.2  148.24 5889.29  148.24  5889.4  148.25 5889.51  148.26
  5890.2   148.3  5910.2   149.2  5937.9  149.75  5986.1  150.72  5990.2   150.8
  6033.6  150.94  6110.2   151.2  6210.2     150  6414.6     150  6430.2     150
  6490.2   151.2  6530.2   151.2  6574.6   152.5  6670.2   155.3  6790.2   157.7
  6830.2   159.7  6834.6  159.78  6870.2   160.4    6899  160.62  6910.2   160.7
  6930.2   161.4  6990.2   165.3  7010.2   166.2  7070.2   169.9  7110.2   173.4
  7150.2   175.8  7170.2   177.6  7190.2   180.7  7210.2   184.2  7230.2     186
  7250.2   187.1  7259.1   187.3  7286.4   189.7
BR U #Mann= 5
   670.2      .1  1616.8     .15  4977.3    .075  5017.3     .15    6899     .09
BR U Banks=4977.3,5017.3
BR D #Sta/Elev= 198
   670.2  172.83   750.2  173.53   790.2  173.43   830.2  174.13   973.7  173.81
  1010.2  173.73  1030.2  173.03  1050.2  170.63  1053.7  170.42  1070.2  169.43
  1090.2  169.43  1110.2  169.93  1130.2  169.43  1133.7  169.28  1170.2  167.73
  1193.7  167.14  1210.2  166.73  1330.2  165.13  1370.2  164.83  1390.2  164.23
  1413.7  164.01  1553.7  162.68  1573.7  162.49  1590.2  162.33  1593.7  162.35
  1613.7  162.45  1616.8  162.46  1630.2  162.53  1653.7  162.38  1673.7  162.26
  1710.2  162.03  1713.7  162.09  1733.7  162.46  1830.2  164.23  1833.7  164.28
  1853.7  164.54  1890.2  165.03  1893.7  165.03  1930.2  165.03  1970.2  165.83
  1973.7  165.76  1990.2  165.43  2013.7  165.78  2030.2  166.03  2053.7  165.97
  2070.2  165.93  2073.7  165.86  2110.2  165.13  2133.7  165.07  2150.2  165.03
  2250.2  162.63  2313.7  162.95  2350.2  163.13  2370.2  162.83  2393.7  163.07
  2510.2  164.23  2590.2  163.43  2630.2  162.83  2693.7  162.51  2730.2  162.33
  2970.2  164.83  3090.2  164.63  3170.2  165.03  3190.2  164.73    3300  162.53
  3350.2  161.53    3400  161.41  3430.2  161.33  3470.2  160.93  3530.2  161.63
  3550.2  162.13  3570.2  163.13  3590.2  163.13  3610.2  163.63  3670.2  163.63
  3690.2  163.33  3830.2  157.83  3850.2  157.53    3940  157.53  3990.2  157.53
  4090.2  158.53  4170.2  157.73  4210.2  157.83  4250.2  157.13  4270.2  157.03
  4370.2  158.33  4410.2  159.23  4430.2  158.93  4490.2  155.13  4630.2  150.63
  4710.1  150.33  4710.2  150.33  4750.2  151.23  4755.8  151.14  4801.1  150.38
  4810.2  150.23  4830.2  149.33 4848.59   148.5  4848.7  148.49 4848.81  148.49
  4849.4  148.46 4849.51  148.45  4849.6  148.45  4863.7  147.81  4876.7  147.22
    4889  148.17  4929.1   147.4  4946.7  145.23  4969.1  142.47  4977.3  143.42
  4987.9  139.56  4990.4  138.45  4997.8  138.43    5009  138.88  5009.2   138.2
  5012.1   139.4  5017.3  142.62  5043.4  144.96  5049.1  145.47  5049.5  145.27
    5089  144.27  5097.3  144.47  5129.1  144.59  5138.8  144.58  5169.2  144.56
  5191.9  144.39    5209  144.39  5234.4  144.32    5249  144.28  5289.1  144.82
  5289.8  145.09    5329  145.45  5329.1  145.45  5369.1   146.1  5385.2  146.35
  5409.2  148.15  5426.9  148.13  5449.1   148.1  5481.4  146.76  5489.2  147.52
  5525.1  147.04  5529.2  146.99  5569.2   146.4  5575.8  146.49  5609.1  146.45
  5622.7  146.46  5649.2  146.49  5671.8   146.6  5689.2  146.49  5720.6  146.66
  5729.2  146.71  5768.7  147.11  5769.3  146.71  5809.2  144.96  5818.2  145.35
  5849.3  146.68  5859.7  147.08  5863.7  147.25  5870.2  147.53 5888.99  148.75
  5889.1  148.76  5889.2  148.77 5889.29  148.77  5889.4  148.78 5889.51  148.79
  5890.2  148.83  5910.2  149.73  5937.9  150.28  5986.1  151.25  5990.2  151.33
  6033.6  151.47  6110.2  151.73  6210.2  150.53  6414.6  150.53  6430.2  150.53
  6490.2  151.73  6530.2  151.73  6574.6  153.03  6670.2  155.83  6790.2  158.23
  6830.2  160.23  6834.6  160.31  6870.2  160.93    6899  161.15  6910.2  161.23
  6930.2  161.93  6990.2  165.83  7010.2  166.73  7070.2  170.43  7110.2  173.93
  7150.2  176.33  7170.2  178.13  7190.2  181.23  7210.2  184.73  7230.2  186.53
  7250.2  187.63  7259.1  187.83  7286.4  190.23
BR D #Mann= 5
   670.2      .1  1616.8     .15  4977.3    .075  5017.3     .15    6899     .09
BR D Banks=4977.3,5017.3
BC Design=,, 0 ,, 0 ,,,,,,
BC HTab HWMax=189.7

Type RM Length L Ch R = 1 ,207388.1,248.7,248.7,248.7
BEGIN DESCRIPTION:
Downstream Section of Tomball Parkway SH249 (149)
Ineffective at Sta 3650 based on topo upstream of the cross section
END DESCRIPTION:
XS GIS Cut Line= 4
    3026905.8286   13973616.6759    3028075.9752   13971260.9861
    3028715.9828   13970089.9084    3030009.1273   13967775.8604
#Sta/Elev= 30
   670.2  172.82  1010.2  173.72  1070.2  169.42  1210.2  166.72  1616.8  162.45
  2030.2  166.02  2250.2  162.62  3170.2  165.02  3470.2  160.92  3670.2  163.62
  3850.2  157.52  4430.2  158.92  4630.2  150.62  4810.2  150.22  4929.1  147.39
  4977.3  143.41  4990.4  138.44  5009.2  138.19  5017.3  142.61  5049.1  145.46
    5249  144.27  5409.2  148.14  5768.7   147.1  5809.2  144.95  5990.2  151.32
  6430.2  150.52    6899  161.14  7150.2  176.32  7210.2  184.72  7286.4  190.22
#Mann= 6 ,-1 , 0
   670.2      .1       0  1616.8     .15       0  4977.3     .08       0
  5017.3     .15       0    6899     .09       0  7286.4      .2       0
#XS Ineff= 3 ,-1
     700    3650     164    3650    4835     160    5900    7000     164
Permanent Ineff=
       F       F       F
Bank Sta=4977.3,5017.3
XS Rating Curve= 0
Exp/Cntr=.5,.3