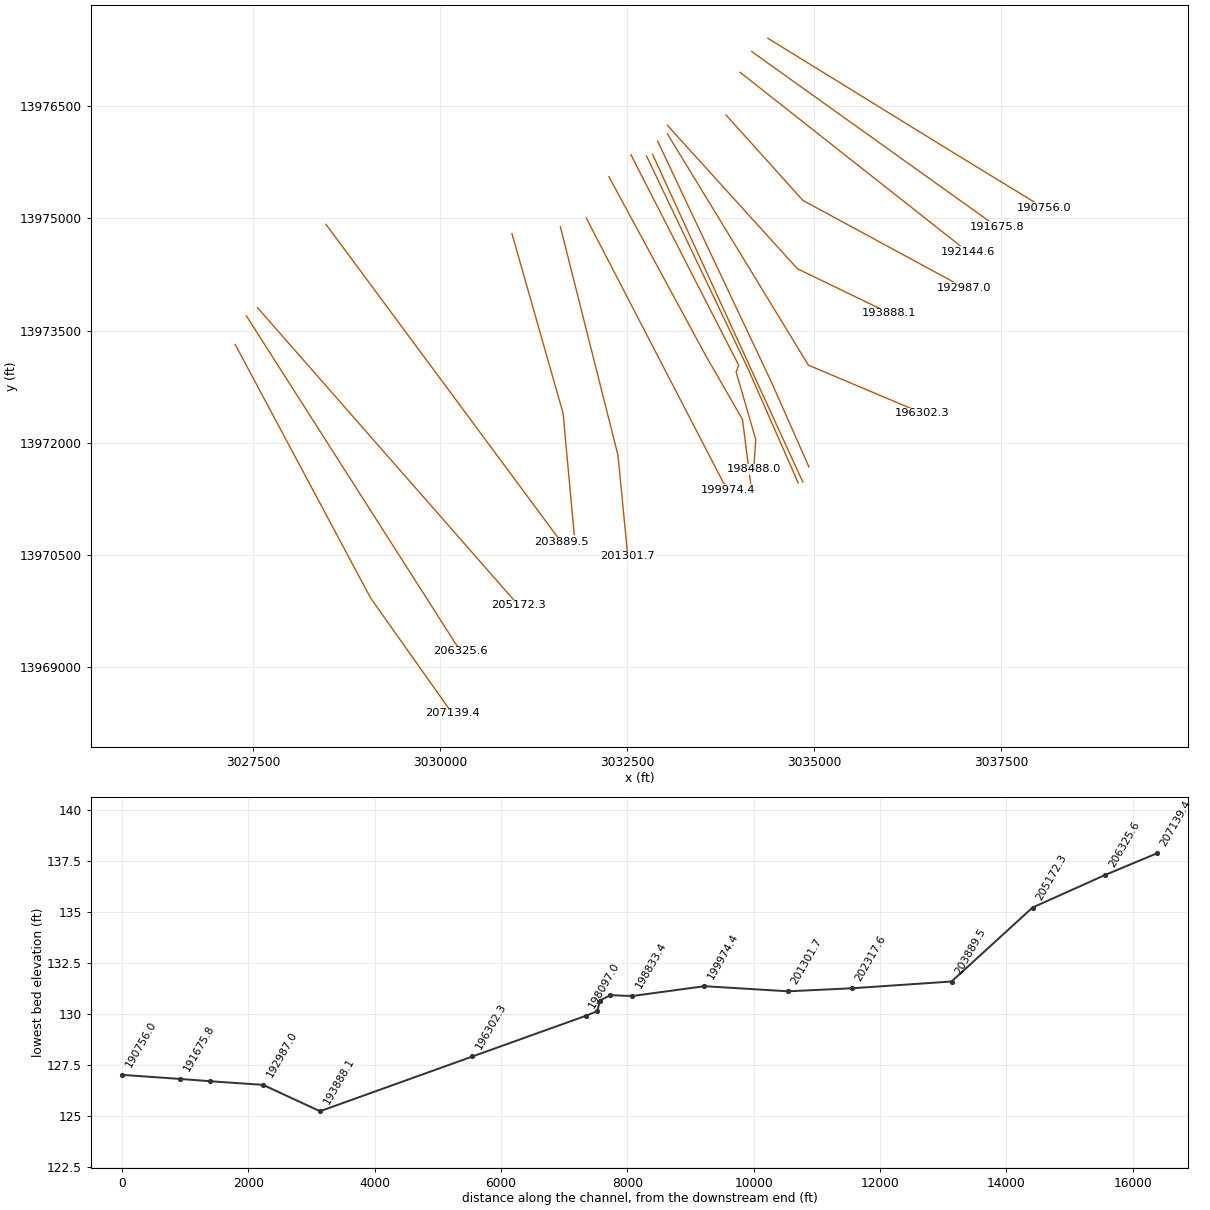
HEC-RAS study J100-00-00.prj: J100-00-00

--- J100-00-00.g01 (geometry) --- (continued)

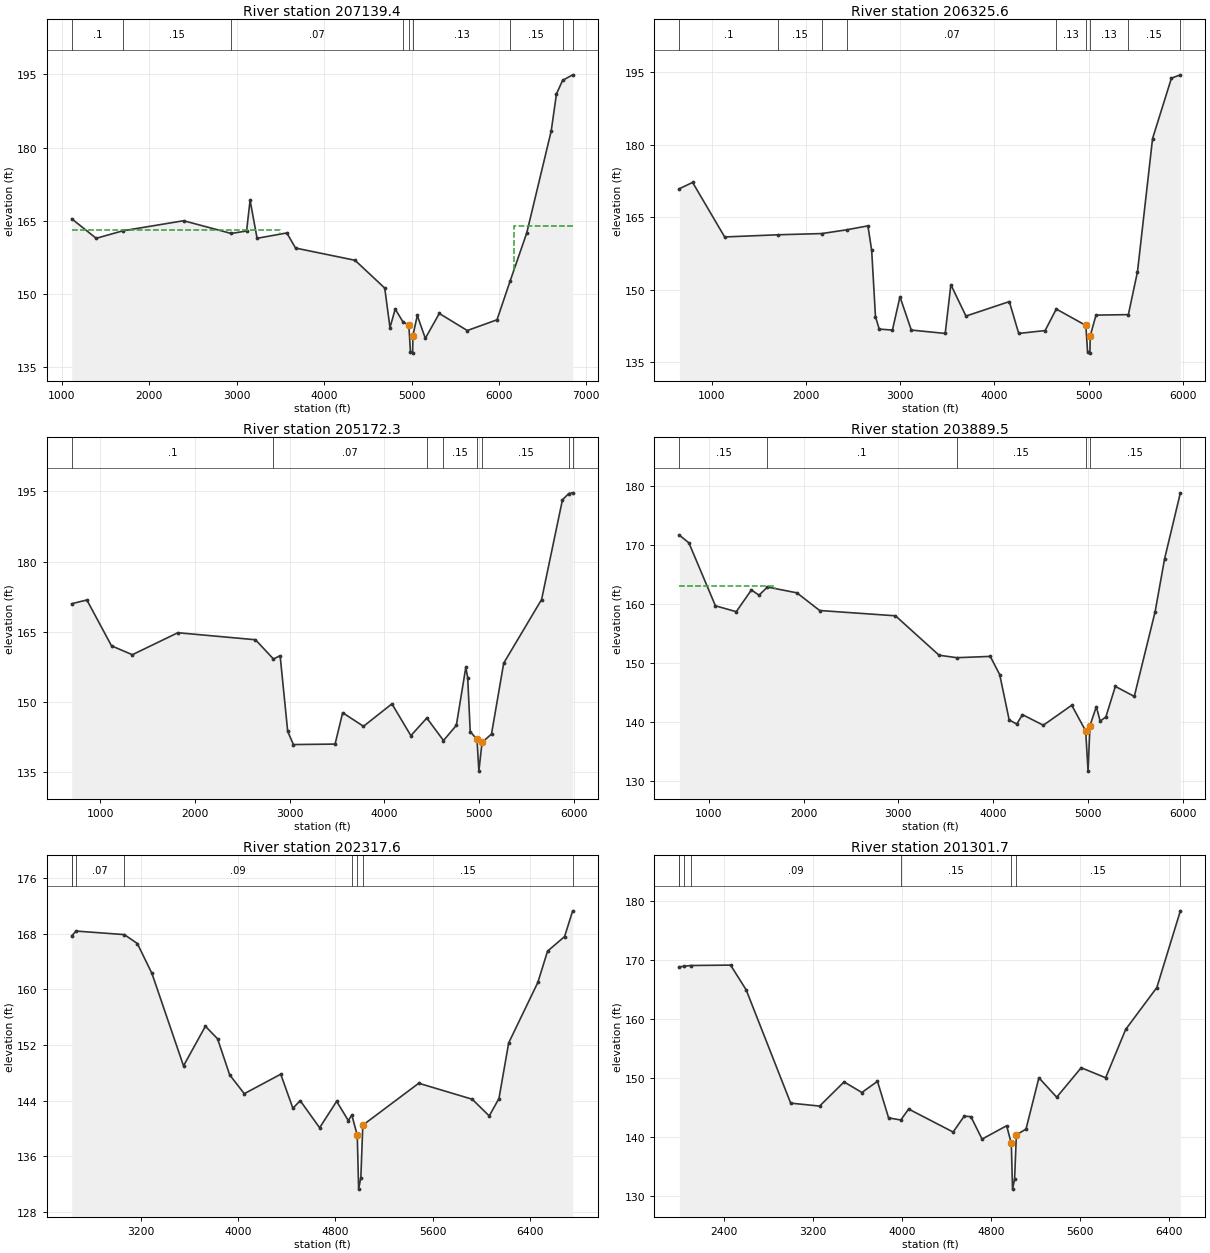
Type RM Length L Ch R = 1 ,207139.4,547.95,813.8,598.63
BEGIN DESCRIPTION:
Cross Section XS155
Ineffective at Sta 3500 based on topo upstream of the cross section
END DESCRIPTION:
XS GIS Cut Line= 3
    3027264.2402   13973314.6925    3029075.3255   13969924.0141
    3030164.7001   13968385.2724
#Sta/Elev= 30
  1113.5   165.4  1393.5   161.4  1699.2  162.94  2393.5     165  2938.2  162.39
  3113.5   162.9  3153.5   169.2  3233.5   161.4  3573.5   162.5  3673.5   159.4
  4353.5   156.9  4693.5   151.2  4753.5   143.1  4813.5   146.9  4902.1  144.27
  4969.4  143.61  4987.3  138.18  5012.4  137.87  5015.6  141.44    5066  145.59
  5157.6   140.9  5317.6     146  5637.6   142.5  5977.6   144.7  6127.7  152.65
  6317.6   162.5  6597.6   183.4  6657.6     191  6727.8  193.76  6842.9   194.9
#Mann= 9 ,-1 , 0
  1113.5      .1       0  1699.2     .15       0  2938.2     .07       0
  4902.1     .13       0  4969.4     .08       0  5015.6     .13       0
  6127.7     .15       0  6727.8     .09       0  6842.9      .2       0
#XS Ineff= 2 , 0
       0    3500     163    6170       0     164
Permanent Ineff=
       F       F
Bank Sta=4969.4,5015.6
XS Rating Curve= 0
Exp/Cntr=.3,.1

Type RM Length L Ch R = 1 ,206325.6,610.34,1153.3,901.28
BEGIN DESCRIPTION:
Cross Section XS154
Ineffective at Sta 2640 based on topo upstream of the cross section
END DESCRIPTION:
XS GIS Cut Line= 2
    3027414.0292   13973695.9736    3030273.6375   13969215.9206
#Sta/Elev= 30
   657.2   170.9   797.2   172.2  1137.2   160.9  1705.1  161.35  2167.2   161.6
    2432  162.38  2657.2   163.2  2697.2   158.1  2737.2   144.4  2777.2   141.8
  2917.2   141.6  2997.2   148.5  3117.2   141.6  3477.2   140.9  3537.2     151
  3697.2   144.5  4157.2   147.5  4257.2   140.9  4537.2   141.5  4655.7  145.96
  4969.4  142.56  4987.3  137.13  5012.4  136.82  5015.6  140.39  5077.2   144.7
  5420.4   144.8  5517.2   153.7  5677.2   181.3  5877.2   193.8  5972.1   194.5
#Mann= 9 ,-1 , 0
   657.2      .1       0  1705.1     .15       0  2167.2      .1       0
    2432     .07       0  4655.7     .13       0  4969.4     .08       0
  5015.6     .13       0  5420.4     .15       0  5972.1      .2       0
#XS Ineff= 2 , 0
       0    2640     163               0
Permanent Ineff=
       F       F
Bank Sta=4969.4,5015.6
XS Rating Curve= 0
Exp/Cntr=.3,.1

Type RM Length L Ch R = 1 ,205172.3,1182.97,1282.8,1031.03
BEGIN DESCRIPTION:
Cross Section XS153
Ineffective at Sta 2625 based on topo upstream of the cross section
END DESCRIPTION:
XS GIS Cut Line= 2
    3027563.8182   13973804.9111    3031049.8169   13969828.6938
#Sta/Elev= 30
   700.7     171   860.7   171.8  1120.7     162  1340.7   160.1  1820.7   164.8
  2640.7   163.3  2830.2  159.18  2900.7   159.9  2980.7   143.7  3040.7   140.9
  3480.7     141  3560.7   147.7  3780.7   144.8  4080.7   149.6  4280.7   142.8
  4449.2  146.57  4625.1  141.76  4760.7     145  4860.7   157.4  4880.7   155.2
  4907.3  143.67    4979  141.99  4998.6  135.22  5032.2  141.38  5131.9  143.14
  5260.7   158.3  5660.7   171.9  5880.7   193.2  5947.5  194.55  5988.7   194.7
#Mann= 8 ,-1 , 0
   700.7      .1       0  2830.2     .07       0  4449.2     .13       0
  4625.1     .15       0    4979     .08       0  5032.2     .15       0
  5947.5     .09       0  5988.7      .2       0
#XS Ineff= 2 , 0
       0    2625     163               0
Permanent Ineff=
       F       F
Bank Sta=4979,5032.2
XS Rating Curve= 0
Exp/Cntr=.3,.1

Type RM Length L Ch R = 1 ,203889.5,1505.74,1571.9,476.04
BEGIN DESCRIPTION:
Cross Section XS152
Ineffective at Sta 1700 based on topo upstream of the cross section
END DESCRIPTION:
XS GIS Cut Line= 2
    3028476.1694     13974921.52    3031621.7386   13970672.9591
#Sta/Elev= 30
     689   171.7     789   170.4    1069   159.7    1289   158.7    1449   162.4
    1529   161.5    1618  162.89    1929   161.9    2169   158.9    2969     158
    3429   151.3  3616.5  150.88    3969   151.1    4069     148    4169   140.3
    4249   139.6    4309   141.2    4529   139.4    4829   142.8  4976.2  138.43
  5001.2   131.6  5021.6  139.35  5088.3  142.55    5129   140.1    5189   140.8
    5289     146    5489   144.3    5709   158.7    5809   167.7  5975.3   178.9
#Mann= 6 ,-1 , 0
     689     .15       0    1618      .1       0  3616.5     .15       0
  4976.2     .08       0  5021.6     .15       0  5975.3      .2       0
#XS Ineff= 2 , 0
       0    1700     163               0
Permanent Ineff=
       F       F
Bank Sta=4976.2,5021.6
XS Rating Curve= 0
Exp/Cntr=.3,.1

Type RM Length L Ch R = 1 ,202317.6,756.35,1015.9,744.46
BEGIN DESCRIPTION:
Cross Section XS151
END DESCRIPTION:
XS GIS Cut Line= 3
    3030962.4114   13974794.9868    3031645.5847   13972394.7092
    3031794.1493   13970774.9203
#Sta/Elev= 30
  2629.8   167.7  2665.6  168.39  3062.6  167.88  3169.8   166.6  3289.8   162.3
  3549.8     149  3729.8   154.7  3829.8   152.9  3929.8   147.7  4049.8     145
  4349.8   147.8  4449.8   142.9  4509.8     144  4669.8   140.1  4809.8   143.9
  4905.9  141.13  4934.8  141.93  4979.6  139.01  4990.7  131.27    5009  132.93
  5025.1  140.47  5485.4   146.5  5925.4   144.2  6065.4   141.8  6145.4   144.3
  6225.4   152.3  6465.4     161  6545.4   165.5  6685.4   167.6    6752   171.3
#Mann= 8 , 1 , 0
  2629.8      .2       0  2629.8     .09       0  2665.6     .07       0
  3062.6     .09       0  4934.8     .15       0  4979.6     .08       0
  5025.1     .15       0    6752      .2       0
Bank Sta=4979.6,5025.1
XS Rating Curve= 0
Exp/Cntr=.3,.1

Type RM Length L Ch R = 1 ,201301.7,853.61,1327.3,1166.12
BEGIN DESCRIPTION:
Cross Section XS150
END DESCRIPTION:
XS GIS Cut Line= 3
    3031609.3187   13974887.4021    3032379.3154   13971832.1824
    3032509.7565   13970487.0094
#Sta/Elev= 30
  1996.8   168.8  2040.7   168.9  2097.8  169.03  2456.8   169.1  2596.8   164.9
  2996.8   145.7  3256.8   145.2  3476.8   149.3  3636.8   147.5  3776.8   149.4
  3876.8   143.2  3986.6  142.84  4056.8   144.7  4456.8   140.8  4556.8   143.5
  4616.8   143.4  4716.8   139.6  4937.9  141.87  4979.6  138.86  4990.7  131.12
    5009  132.78  5025.1  140.32  5111.8   141.3  5227.6     150  5387.6   146.7
  5607.6   151.7  5827.6     150  6007.6   158.2  6287.6   165.3    6499   178.3
#Mann= 8 , 1 , 0
  1996.8      .2       0  1996.8     .09       0  2040.7     .07       0
  2097.8     .09       0  3986.6     .15       0  4979.6     .08       0
  5025.1     .15       0    6499      .2       0
Bank Sta=4979.6,5025.1
XS Rating Curve= 0
Exp/Cntr=.3,.1

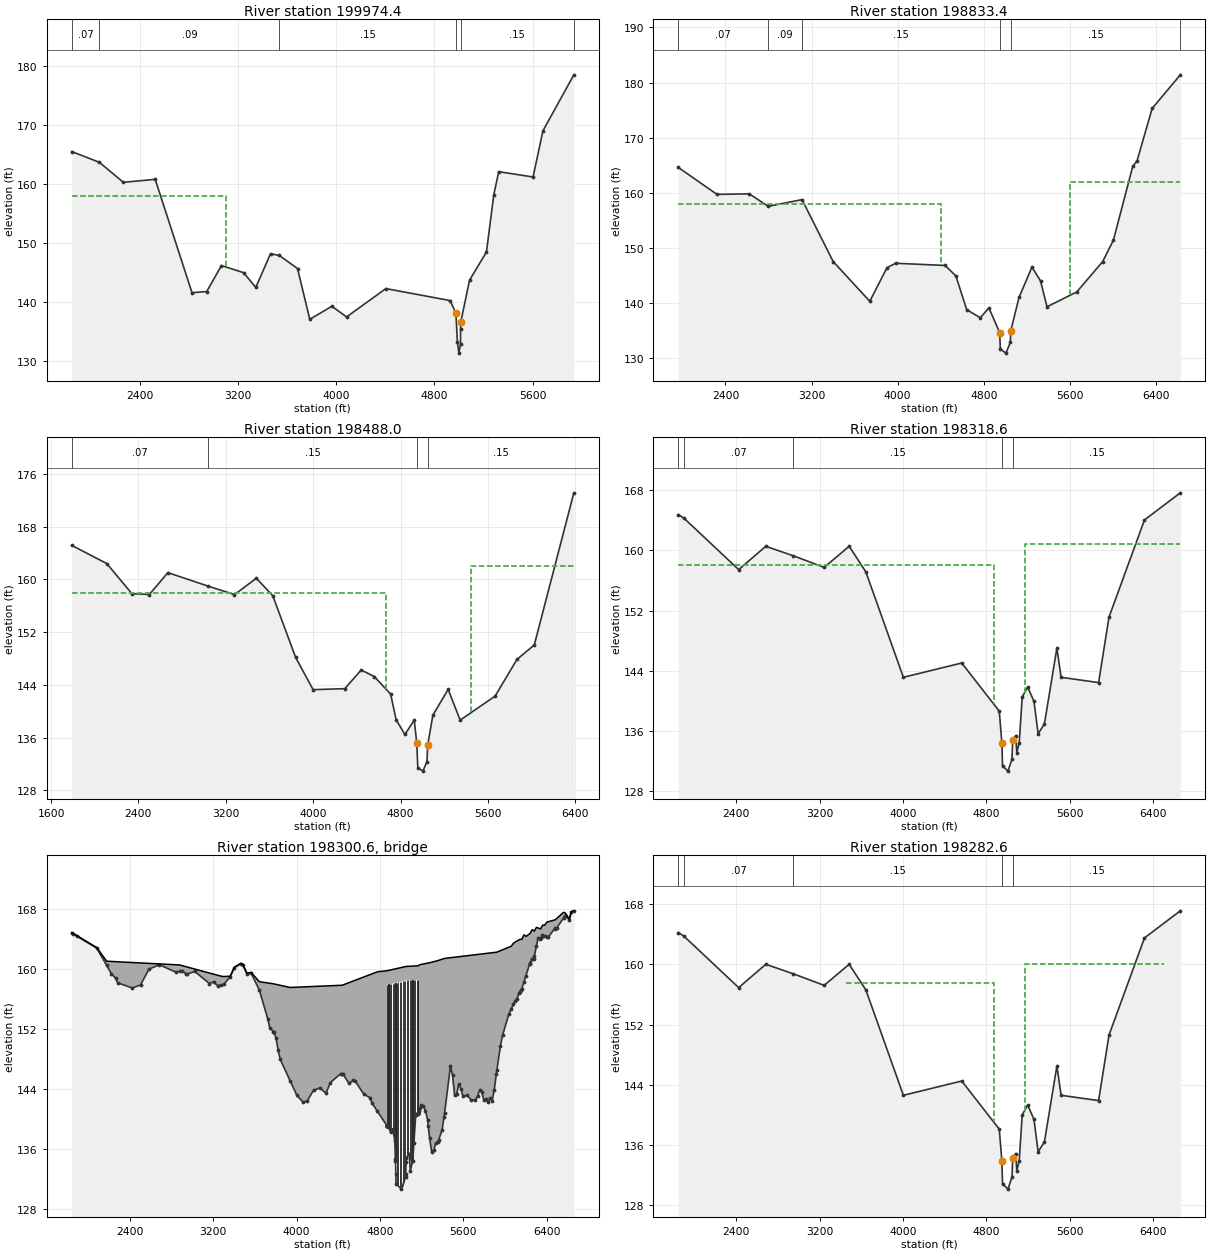
Type RM Length L Ch R = 1 ,199974.4,643.77,1141,605.95
BEGIN DESCRIPTION:
Cross Section XS149
END DESCRIPTION:
XS GIS Cut Line= 3
    3031955.3822   13975003.5295    3033814.1666   13971416.4016
    3033846.7768   13971375.6388
#Sta/Elev= 30
    1844   165.5  2069.6  163.68    2264   160.3    2524   160.8    2824   141.6
    2944   141.8    3064   146.2    3244     145    3344   142.5    3464   148.2
  3534.8  147.92    3684   145.7    3784   137.1    3964   139.3    4084   137.5
    4404   142.3  4928.1  140.27  4975.2   138.1 4987.31  133.19  4999.6  131.37
  5012.6  132.99  5012.9  135.54  5014.9  136.66  5086.3  143.73    5224   148.5
    5284   158.2    5324   162.1    5604   161.2    5684     169  5936.3   178.5
#Mann= 6 ,-1 , 0
    1844     .07       0  2069.6     .09       0  3534.8     .15       0
  4975.2     .08       0  5014.9     .15       0  5936.3      .2       0
#XS Ineff= 2 , 0
       0    3100     158               0
Permanent Ineff=
       F       F
Bank Sta=4975.2,5014.9
XS Rating Curve= 0
Exp/Cntr=.3,.1

Type RM Length L Ch R = 1 ,198833.4,379.22,345.4,180
BEGIN DESCRIPTION:
Cross Section XS148
END DESCRIPTION:
XS GIS Cut Line= 4
     3032257.027   13975557.9038     3033545.132   13973177.3553
    3034042.4384   13972313.1836    3034164.7268   13971359.3337
#Sta/Elev= 30
  1961.3   164.6  2321.3   159.7  2621.3   159.8  2797.5  157.53  3111.6  158.75
  3401.3   147.5  3741.3   140.3  3901.3   146.4  3981.3   147.2  4441.3   146.8
  4541.3   144.9  4641.3   138.8    4768   137.3    4848   139.1  4948.2  134.61
  4954.4  131.61  5006.5  130.89  5047.4  132.86  5051.7  134.97    5128     141
    5248   146.5    5328     144    5388   139.3    5665     142    5905   147.5
    6005   151.4    6185   164.8    6225   165.8    6365   175.3  6626.7   181.4
#Mann= 6 ,-1 , 0
  1961.3     .07       0  2797.5     .09       0  3111.6     .15       0
  4948.2     .08       0  5051.7     .15       0  6626.7      .2       0
#XS Ineff= 2 , 0
       0    4400     158    5600       0     162
Permanent Ineff=
       F       F
Bank Sta=4948.2,5051.7
XS Rating Curve= 0
Exp/Cntr=.3,.1

Type RM Length L Ch R = 1 ,198488.0,124,169.4,171
XS GIS Cut Line= 5
      3032552.03      13975848.9      3033993.08      13973035.1
      3033957.83       13972947.      3034219.75      13972045.5
        3034193.      13971644.2
#Sta/Elev= 30
    1790165.1778    2110162.4238    2340157.8629    2500157.7215    2670161.0422
    3040158.9865    3280157.7122    3480160.1855    3630157.5513    3840148.1726
    4000 143.287    4290 143.441    4440146.2722    4560145.2794    4710142.6062
    4760 138.721    4840  136.49 4925.96  138.67 4948.95  135.14 4958.46  131.48
 5004.43  130.93 5042.47  132.37 5048.81  134.86 5096.28139.4057 5236.28143.3327
 5346.28138.6656 5666.28142.3107 5866.28147.8753 6025.05150.0659 6387.21173.1478
#Mann= 4 ,-1 , 0
    1790     .07       0    3040     .15       0 4948.95     .08       0
 5048.81     .15       0
#XS Ineff= 2 , 0
       0    4670     158    5450       0     162
Permanent Ineff=
       F       F
Bank Sta=4948.95,5048.81
XS Rating Curve= 0
Exp/Cntr=.5,.3

Type RM Length L Ch R = 1 ,198318.6,36,36,36
BEGIN DESCRIPTION:
Upstream Section of Burlington Northern Railroad
END DESCRIPTION:
XS GIS Cut Line= 3
    3032760.5638   13975833.3643    3034120.4795   13972982.1774
    3034786.7924   13971465.7894
#Sta/Elev= 30
  1843.2  164.73  1895.9  164.29  2423.2  157.43  2683.2  160.53  2948.8  159.26
  3243.2  157.73  3483.2  160.53  3643.2  157.13  4003.2  143.13  4563.2  145.03
  4923.2  138.63  4948.2  134.39  4954.4  131.39  5006.5  130.67  5045.5  132.29
  5051.7  134.75  5080.9   135.4  5091.5  133.12  5114.8  134.46  5143.2  140.53
  5196.2  141.83  5256.2  139.93  5296.2  135.63  5356.2  136.93  5476.2  147.03
  5516.2  143.13  5876.2  142.43  5976.2  151.13  6316.2  164.03  6660.1  167.63
#Mann= 5 ,-1 , 0
  1843.2     .09       0  1895.9     .07       0  2948.8     .15       0
  4948.2     .08       0  5051.7     .15       0
#XS Ineff= 2 , 0
       0  4868.2     158  5165.9       0   160.8
Permanent Ineff=
       F       F
Bank Sta=4948.2,5051.7
XS Rating Curve= 0
Exp/Cntr=.5,.3

Type RM Length L Ch R = 3 ,198300.6,,,
BEGIN DESCRIPTION:
BURLINGTON NORTHERN RAILROAD
Structure ID: J100-00-00-08
Square nose piers, ten pile trestle bent
END DESCRIPTION:
Node Name=BN Railroad
Bridge Culvert--1,0,-1,-1, 0
Deck Dist Width WeirC Skew NumUp NumDn MinLoCord MaxHiCord MaxSubmerge Is_Ogee
10,16,2.6,0, 161, 161, , , .95, 0, 1,1,,
  1843.2  1857.5  1895.9  2083.2  2177.5  2223.2  2263.2  2283.2  2423.2  2503.2
  2583.2  2683.2  2843.2  2877.5  2903.2  2943.2  2948.8  3023.2  3163.2  3203.2
  3243.2  3277.5  3303.2  3363.2  3403.2  3463.2  3483.2  3523.2  3563.2  3643.2
  3723.2  3743.2  3777.5  3783.2  3803.2  3823.2  3843.2  3937.5  4003.2  4063.2
  4103.2  4163.2  4223.2  4283.2  4323.2  4423.2  4437.5  4443.2  4503.2  4543.2
  4563.2  4643.2  4703.2  4723.2  4776.3  4868.1 4868.21 4868.29  4868.4  4868.5
 4868.61  4868.7  4903.2  4908.4  4923.2  4943.2  4948.2  4948.9  4952.6  4954.4
  5006.5  5045.5  5047.4  5050.8  5051.7  5080.9  5091.5  5114.8  5125.8  5143.2
  5163.2 5165.29  5165.4 5165.51  5165.6 5165.69  5165.8  5176.2  5184.5  5196.2
  5216.2  5236.2  5256.2    5263  5276.2  5296.2  5316.2  5336.2  5356.2    5363
  5396.2  5416.2  5420.2  5476.2  5496.2  5516.2  5536.2  5556.2  5576.2  5596.2
  5636.2  5676.2  5716.2  5736.2  5756.2  5776.2  5796.2  5816.2  5836.2  5856.2
  5876.2  5896.2  5916.2    5921  5956.2  5976.2  6036.2    6061    6081  6096.2
  6116.2  6136.2    6141  6156.2    6161    6181    6201  6236.2    6241  6256.2
    6261  6276.2    6281    6301  6316.2  6336.2    6341  6356.2    6361    6381
    6401  6416.2  6476.2    6481  6496.2    6561  6576.2  6579.2  6616.2  6636.2
  6660.1
   164.8  164.69  164.37  162.81     161  160.97  160.94  160.92  160.82  160.77
  160.71  160.64  160.52   160.5   160.4  160.25  160.23  159.95  159.43  159.28
  159.13     159  158.95  159.01  160.21  160.71  160.61  159.41  159.51  158.27
  158.11  158.07     158  157.98  157.92  157.86  157.79   157.5  157.54  157.58
   157.6  157.64  157.67  157.71  157.73  157.79   157.8  157.83  158.15  158.36
  158.46  158.89   159.2  159.31  159.59  159.72  159.73  159.73  159.73  159.73
  159.73  159.73  159.84  159.85   159.9  159.96  159.98  159.98  159.99     160
  160.16  160.28  160.29   160.3   160.3  160.32  160.33  160.34  160.35  160.36
  160.38  160.38  160.38  160.38  160.38  160.38  160.38  160.47  160.54  160.57
  160.62  160.67  160.72  160.74  160.79  160.86  160.94  161.01  161.08  161.11
  161.26  161.35  161.37  161.46   161.5  161.53  161.56   161.6  161.63  161.66
  161.73  161.79  161.86  161.89  161.93  161.96  161.99  162.03  162.06  162.09
  162.13  162.16  162.19   162.2   162.4  162.52  162.86     163   163.4  163.53
  163.69  163.86   163.9   163.9   163.9   164.5   164.3  164.65   164.7  165.08
   165.2  165.05     165   165.5  165.42  165.32   165.3  165.68   165.8   165.8
   166.2  166.26  166.48   166.5  166.69   167.5  167.42   167.4   166.6   167.6
   167.7
                                                                                
                                                                                
                                                                                
                                                                                
                                                                                
                                                                  157.86  157.86
  157.86  157.86  157.97  157.98  158.03  158.09  158.11  158.11  158.12  158.13
  158.29  158.41  158.42  158.43  158.43  158.45  158.46  158.47  158.48  158.49
  158.51  158.51  158.51  158.51  158.51  158.51
                                                                                
                                                                                
                                                                                
                                                                                
                                                                                
                                                                                
                                                                                
        
  1843.2  1857.5  1895.9  2083.2  2177.5  2223.2  2263.2  2283.2  2423.2  2503.2
  2583.2  2683.2  2843.2  2877.5  2903.2  2943.2  2948.8  3023.2  3163.2  3203.2
  3243.2  3277.5  3303.2  3363.2  3403.2  3463.2  3483.2  3523.2  3563.2  3643.2
  3723.2  3743.2  3777.5  3783.2  3803.2  3823.2  3843.2  3937.5  4003.2  4063.2
  4103.2  4163.2  4223.2  4283.2  4323.2  4423.2  4437.5  4443.2  4503.2  4543.2
  4563.2  4643.2  4703.2  4723.2  4776.3  4868.1 4868.21 4868.29  4868.4  4868.5
 4868.61  4868.7  4903.2  4908.4  4923.2  4943.2  4948.2  4948.9  4952.6  4954.4
  5006.5  5045.5  5047.4  5050.8  5051.7  5080.9  5091.5  5114.8  5125.8  5143.2
  5163.2 5165.29  5165.4 5165.51  5165.6 5165.69  5165.8  5176.2  5184.5  5196.2
  5216.2  5236.2  5256.2    5263  5276.2  5296.2  5316.2  5336.2  5356.2    5363
  5396.2  5416.2  5420.2  5476.2  5496.2  5516.2  5536.2  5556.2  5576.2  5596.2
  5636.2  5676.2  5716.2  5736.2  5756.2  5776.2  5796.2  5816.2  5836.2  5856.2
  5876.2  5896.2  5916.2    5921  5956.2  5976.2  6036.2    6061    6081  6096.2
  6116.2  6136.2    6141  6156.2    6161    6181    6201  6236.2    6241  6256.2
    6261  6276.2    6281    6301  6316.2  6336.2    6341  6356.2    6361    6381
    6401  6416.2  6476.2    6481  6496.2    6561  6576.2  6579.2  6616.2  6636.2
  6660.1
   164.8  164.69  164.37  162.81     161  160.97  160.94  160.92  160.82  160.77
  160.71  160.64  160.52   160.5   160.4  160.25  160.23  159.95  159.43  159.28
  159.13     159  158.95  159.01  160.21  160.71  160.61  159.41  159.51  158.27
  158.11  158.07     158  157.98  157.92  157.86  157.79   157.5  157.54  157.58
   157.6  157.64  157.67  157.71  157.73  157.79   157.8  157.83  158.15  158.36
  158.46  158.89   159.2  159.31  159.59  159.72  159.73  159.73  159.73  159.73
  159.73  159.73  159.84  159.85   159.9  159.96  159.98  159.98  159.99     160
  160.16  160.28  160.29   160.3   160.3  160.32  160.33  160.34  160.35  160.36
  160.38  160.38  160.38  160.38  160.38  160.38  160.38  160.47  160.54  160.57
  160.62  160.67  160.72  160.74  160.79  160.86  160.94  161.01  161.08  161.11
  161.26  161.35  161.37  161.46   161.5  161.53  161.56   161.6  161.63  161.66
  161.73  161.79  161.86  161.89  161.93  161.96  161.99  162.03  162.06  162.09
  162.13  162.16  162.19   162.2   162.4  162.52  162.86     163   163.4  163.53
  163.69  163.86   163.9   163.9   163.9   164.5   164.3  164.65   164.7  165.08
   165.2  165.05     165   165.5  165.42  165.32   165.3  165.68   165.8   165.8
   166.2  166.26  166.48   166.5  166.69   167.5  167.42   167.4   166.6   167.6
   167.7
                                                                                
                                                                                
                                                                                
                                                                                
                                                                                
                                                                  157.86  157.86
  157.86  157.86  157.97  157.98  158.03  158.09  158.11  158.11  158.12  158.13
  158.29  158.41  158.42  158.43  158.43  158.45  158.46  158.47  158.48  158.49
  158.51  158.51  158.51  158.51  158.51  158.51
                                                                                
                                                                                
                                                                                
                                                                                
                                                                                
                                                                                
                                                                                
        
Pier Skew, UpSta & Num, DnSta & Num=  ,4869.9, 2 ,4869.9, 2 , 0 , 0 , 0 ,,
       1       1
  138.02  158.87
       1       1
  138.01  158.86
Pier Skew, UpSta & Num, DnSta & Num=  ,4882.3, 2 ,4882.3, 2 , 0 , 0 , 0 ,,
       1       1
  137.76   158.9
       1       1
  137.75  158.89
Pier Skew, UpSta & Num, DnSta & Num=  ,4894.9, 2 ,4894.9, 2 , 0 , 0 , 0 ,,
       1       1
   137.5  158.95
       1       1
  137.49  158.94
Pier Skew, UpSta & Num, DnSta & Num=  ,4908.9, 2 ,4908.9, 2 , 0 , 0 , 0 ,,
       1       1
  137.41  158.98
       1       1
   137.4  158.97
Pier Skew, UpSta & Num, DnSta & Num=  ,4921.7, 2 ,4921.7, 2 , 0 , 0 , 0 ,,
       1       1
   137.6  159.03
       1       1
  137.59  159.02
Pier Skew, UpSta & Num, DnSta & Num=  ,4935.1, 2 ,4935.1, 2 , 0 , 0 , 0 ,,
       1       1
  136.64  159.07
       1       1
  136.63  159.06
Pier Skew, UpSta & Num, DnSta & Num=  ,4948.9, 2 ,4948.9, 2 , 0 , 0 , 0 ,,
       1       1
  133.39  159.11
       1       1
  133.38   159.1
Pier Skew, UpSta & Num, DnSta & Num=  ,4963.4, 2 ,4963.4, 2 , 0 , 0 , 0 ,,
       1       1
  130.26  159.16
       1       1
  130.25  159.15
Pier Skew, UpSta & Num, DnSta & Num=  ,4976.9, 2 ,4976.9, 2 , 0 , 0 , 0 ,,
       1       1
  130.07   159.2
       1       1
  130.06  159.19
Pier Skew, UpSta & Num, DnSta & Num=  ,4989.6, 2 ,4989.6, 2 , 0 , 0 , 0 ,,
       1       1
   129.9  159.24
       1       1
  129.89  159.23
Pier Skew, UpSta & Num, DnSta & Num=  ,5003.3, 2 ,5003.3, 2 , 0 , 0 , 0 ,,
       1       1
  129.71  159.28
       1       1
   129.7  159.27
Pier Skew, UpSta & Num, DnSta & Num=  ,5017.1, 2 ,5017.1, 2 , 0 , 0 , 0 ,,
       1       1
  130.09  159.32
       1       1
  130.08  159.31
Pier Skew, UpSta & Num, DnSta & Num=  ,5029.9, 2 ,5029.9, 2 , 0 , 0 , 0 ,,
       1       1
  130.62  159.36
       1       1
  130.61  159.35
Pier Skew, UpSta & Num, DnSta & Num=  ,5043.8, 2 ,5043.8, 2 , 0 , 0 , 0 ,,
       1       1
   131.2  159.41
       1       1
  131.19   159.4
Pier Skew, UpSta & Num, DnSta & Num=  ,5057.9, 2 ,5057.9, 2 , 0 , 0 , 0 ,,
       1       1
  133.88  159.43
       1       1
  133.87  159.42
Pier Skew, UpSta & Num, DnSta & Num=  ,5071.8, 2 ,5071.8, 2 , 0 , 0 , 0 ,,
       1       1
  134.19  159.44
       1       1
  134.18  159.43
Pier Skew, UpSta & Num, DnSta & Num=  ,5084.9, 2 ,5084.9, 2 , 0 , 0 , 0 ,,
       1       1
  133.43  159.45
       1       1
  133.42  159.44
Pier Skew, UpSta & Num, DnSta & Num=  ,5099.2, 2 ,5099.2, 2 , 0 , 0 , 0 ,,
       1       1
  132.53  159.46
       1       1
  132.52  159.45
Pier Skew, UpSta & Num, DnSta & Num=  ,5112.1, 2 ,5112.1, 2 , 0 , 0 , 0 ,,
       1       1
  133.28  159.47
       1       1
  133.27  159.46
Pier Skew, UpSta & Num, DnSta & Num=  ,5125.7, 2 ,5125.7, 2 , 0 , 0 , 0 ,,
       1       1
  135.68  159.48
       1       1
  135.67  159.47
Pier Skew, UpSta & Num, DnSta & Num=  ,5138.9, 2 ,5138.9, 2 , 0 , 0 , 0 ,,
       1       1
   138.5  159.49
       1       1
  138.49  159.48
Pier Skew, UpSta & Num, DnSta & Num=  ,5152.8, 2 ,5152.8, 2 , 0 , 0 , 0 ,,
       1       1
  139.62   159.5
       1       1
  139.61  159.49
Pier Skew, UpSta & Num, DnSta & Num=  ,5164.9, 2 ,5164.9, 2 , 0 , 0 , 0 ,,
       1       1
  139.76  159.51
       1       1
  139.75   159.5
Abutment Skew #Up #Dn= , 2 , 2
  4868.2  4908.4
  157.86  138.41
  4868.2  4908.4
  157.85   138.4
Abutment Skew #Up #Dn= , 2 , 2
  5125.8 5165.89
  136.81  158.51
  5125.8 5165.89
   136.8   158.5
BR Coef= 1 , 1 , 1 ,2.5, 0 ,,,.8,0,2,0,
WSPro=,,,, 1 ,,,, 0 ,,,, 0 ,,,,-1 ,-1 ,-1 , 0 , 0 , 0 , 0 , 0
BR U #Sta/Elev= 161
  1843.2  164.73  1857.5  164.61  1895.9  164.29  2083.2  162.73  2177.5  160.44
  2223.2  159.33  2263.2  158.73  2283.2  158.13  2423.2  157.43  2503.2  157.83
  2583.2  159.93  2683.2  160.53  2843.2  159.53  2877.5  159.64  2903.2  159.73
  2943.2  159.23  2948.8  159.26  3023.2  159.63  3163.2  158.03  3203.2  158.23
  3243.2  157.73  3277.5  157.84  3303.2  157.93  3363.2  158.93  3403.2  160.13
  3463.2  160.63  3483.2  160.53  3523.2  159.33  3563.2  159.43  3643.2  157.13
  3723.2  153.33  3743.2  152.13  3777.5  151.62  3783.2  151.53  3803.2  150.73
  3823.2  149.13  3843.2  147.93  3937.5   145.1  4003.2  143.13  4063.2  142.23
  4103.2  142.43  4163.2  143.83  4223.2  144.13  4283.2  143.43  4323.2  144.83
  4423.2  146.03  4437.5  146.03  4443.2  146.03  4503.2  144.73  4543.2  145.13
  4563.2  145.03  4643.2  143.33  4703.2  142.83  4723.2  142.13  4776.3  141.01
  4868.1  139.07 4868.21  139.07 4868.29  139.07  4868.4  139.06  4868.5  139.06
 4868.61  139.06  4868.7  139.06  4903.2  138.33  4908.4  138.41  4923.2  138.63
  4943.2  137.03  4948.2  134.39  4948.9  134.65  4952.6  132.73  4954.4  131.39
  5006.5  130.67  5045.5  132.29  5047.4  132.64  5050.8  134.31  5051.7  134.75
  5080.9   135.4  5091.5  133.12  5114.8  134.46  5125.8  136.81  5143.2  140.53
  5163.2  140.73 5165.29  140.79  5165.4   140.8 5165.51   140.8  5165.6   140.8
 5165.69  140.81  5165.8  140.81  5176.2  141.13  5184.5  141.42  5196.2  141.83
  5216.2  141.73  5236.2  141.13  5256.2  139.93    5263  139.08  5276.2  137.43
  5296.2  135.63  5316.2  135.83  5336.2  136.83  5356.2  136.93    5363   137.2
  5396.2  138.53  5416.2  140.33  5420.2  140.78  5476.2  147.03  5496.2  145.83
  5516.2  143.13  5536.2  143.33  5556.2  144.63  5576.2  144.03  5596.2  143.03
  5636.2  143.13  5676.2  142.53  5716.2  142.53  5736.2  143.03  5756.2  143.83
  5776.2  143.63  5796.2  142.53  5816.2  142.63  5836.2  142.23  5856.2  142.73
  5876.2  142.43  5896.2  143.83  5916.2  146.03    5921  146.47  5956.2  149.73
  5976.2  151.13  6036.2  153.93    6061  154.67    6081  155.27  6096.2  155.73
  6116.2  156.03  6136.2  156.83    6141   156.9  6156.2  157.13    6161  157.34
    6181  158.22    6201  159.09  6236.2  160.63    6241  160.77  6256.2  161.23
    6261  161.25  6276.2  161.33    6281  161.65    6301     163  6316.2  164.03
  6336.2  163.93    6341  164.05  6356.2  164.43    6361  164.41    6381  164.35
    6401  164.28  6416.2  164.23  6476.2  165.33    6481  165.35  6496.2  165.43
    6561  166.73  6576.2  167.03  6579.2  166.99  6616.2  166.53  6636.2  167.53
  6660.1  167.63
BR U #Mann= 5
  1843.2     .09  1895.9     .07  2948.8     .15  4948.2    .075  5051.7     .15
BR D #Sta/Elev= 161
  1843.2  164.21  1857.5  164.09  1895.9  163.77  2083.2  162.21  2177.5  159.92
  2223.2  158.81  2263.2  158.21  2283.2  157.61  2423.2  156.91  2503.2  157.31
  2583.2  159.41  2683.2  160.01  2843.2  159.01  2877.5  159.12  2903.2  159.21
  2943.2  158.71  2948.8  158.74  3023.2  159.11  3163.2  157.51  3203.2  157.71
  3243.2  157.21  3277.5  157.32  3303.2  157.41  3363.2  158.41  3403.2  159.61
  3463.2  160.11  3483.2  160.01  3523.2  158.81  3563.2  158.91  3643.2  156.61
  3723.2  152.81  3743.2  151.61  3777.5   151.1  3783.2  151.01  3803.2  150.21
  3823.2  148.61  3843.2  147.41  3937.5  144.58  4003.2  142.61  4063.2  141.71
  4103.2  141.91  4163.2  143.31  4223.2  143.61  4283.2  142.91  4323.2  144.31
  4423.2  145.51  4437.5  145.51  4443.2  145.51  4503.2  144.21  4543.2  144.61
  4563.2  144.51  4643.2  142.81  4703.2  142.31  4723.2  141.61  4776.3  140.49
  4868.1  138.55 4868.21  138.55 4868.29  138.55  4868.4  138.54  4868.5  138.54
 4868.61  138.54  4868.7  138.54  4903.2  137.81  4908.4  137.89  4923.2  138.11
  4943.2  136.51  4948.2  133.87  4948.9  134.13  4952.6  132.21  4954.4  130.87
  5006.5  130.15  5045.5  131.77  5047.4  132.12  5050.8  133.79  5051.7  134.23
  5080.9  134.88  5091.5   132.6  5114.8  133.94  5125.8  136.29  5143.2  140.01
  5163.2  140.21 5165.29  140.27  5165.4  140.28 5165.51  140.28  5165.6  140.28
 5165.69  140.29  5165.8  140.29  5176.2  140.61  5184.5   140.9  5196.2  141.31
  5216.2  141.21  5236.2  140.61  5256.2  139.41    5263  138.56  5276.2  136.91
  5296.2  135.11  5316.2  135.31  5336.2  136.31  5356.2  136.41    5363  136.68
  5396.2  138.01  5416.2  139.81  5420.2  140.26  5476.2  146.51  5496.2  145.31
  5516.2  142.61  5536.2  142.81  5556.2  144.11  5576.2  143.51  5596.2  142.51
  5636.2  142.61  5676.2  142.01  5716.2  142.01  5736.2  142.51  5756.2  143.31
  5776.2  143.11  5796.2  142.01  5816.2  142.11  5836.2  141.71  5856.2  142.21
  5876.2  141.91  5896.2  143.31  5916.2  145.51    5921  145.95  5956.2  149.21
  5976.2  150.61  6036.2  153.41    6061  154.15    6081  154.75  6096.2  155.21
  6116.2  155.51  6136.2  156.31    6141  156.38  6156.2  156.61    6161  156.82
    6181   157.7    6201  158.57  6236.2  160.11    6241  160.25  6256.2  160.71
    6261  160.73  6276.2  160.81    6281  161.13    6301  162.48  6316.2  163.51
  6336.2  163.41    6341  163.53  6356.2  163.91    6361  163.89    6381  163.83
    6401  163.76  6416.2  163.71  6476.2  164.81    6481  164.83  6496.2  164.91
    6561  166.21  6576.2  166.51  6579.2  166.47  6616.2  166.01  6636.2  167.01
  6660.1  167.11
BR D #Mann= 5
  1843.2     .09  1895.9     .07  2948.8     .15  4948.2    .075  5051.7     .15
BC Design=,, 0 ,, 0 ,,,,,,
BC HTab HWMax=167.63

Type RM Length L Ch R = 1 ,198282.6,185.6,185.6,185.6
BEGIN DESCRIPTION:
Downstream Section of Burlington Northern Railroad
Ineffective at Sta 3450 based on topo upstream of the cross section
END DESCRIPTION:
XS GIS Cut Line= 2
    3032841.4756   13975854.7759    3034849.0981    13971475.747
#Sta/Elev= 30
  1843.2  164.21  1895.9  163.77  2423.2  156.91  2683.2  160.01  2948.8  158.74
  3243.2  157.21  3483.2  160.01  3643.2  156.61  4003.2  142.61  4563.2  144.51
  4923.2  138.11  4948.2  133.87  4954.4  130.87  5006.5  130.15  5045.5  131.77
  5051.7  134.23  5080.9  134.88  5091.5   132.6  5114.8  133.94  5143.2  140.01
  5196.2  141.31  5256.2  139.41  5296.2  135.11  5356.2  136.41  5476.2  146.51
  5516.2  142.61  5876.2  141.91  5976.2  150.61  6316.2  163.51  6660.1  167.11
#Mann= 5 ,-1 , 0
  1843.2     .09       0  1895.9     .07       0  2948.8     .15       0
  4948.2     .08       0  5051.7     .15       0
#XS Ineff= 3 ,-1
    1850    3450     159    3450  4868.2   157.5  5165.9    6500   160.1
Permanent Ineff=
       F       F       F
Bank Sta=4948.2,5051.7
XS Rating Curve= 0
Exp/Cntr=.5,.3

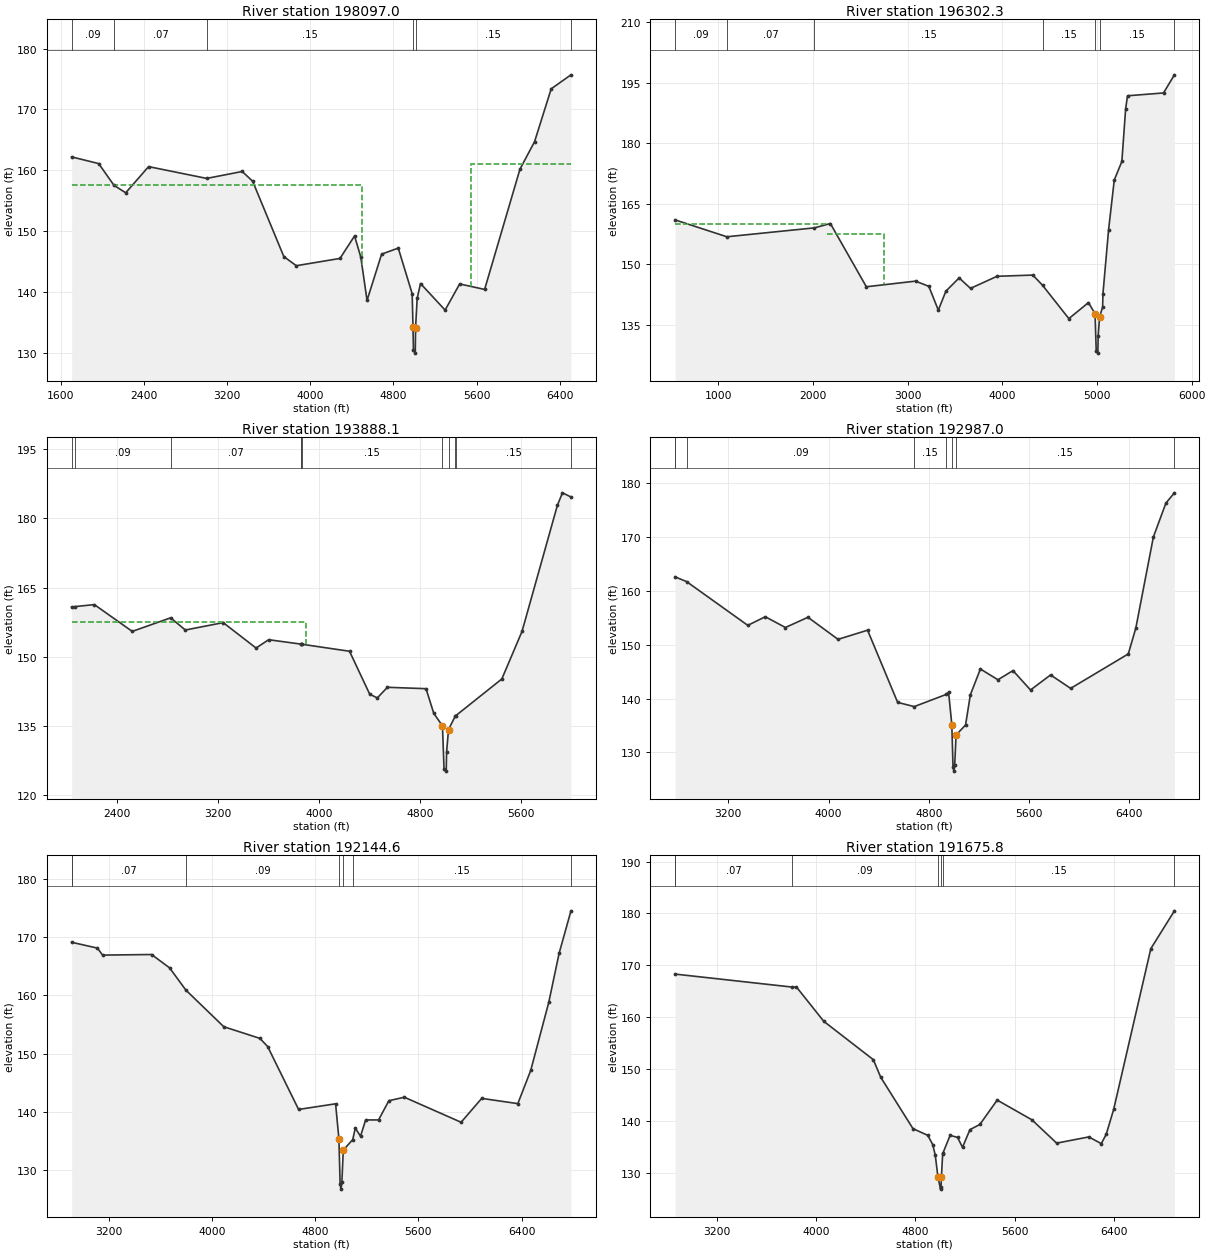
Type RM Length L Ch R = 1 ,198097.0,387.74,1794.7,1247.52
BEGIN DESCRIPTION:
Cross Section XS147-Bridge 8- Exp
END DESCRIPTION:
XS GIS Cut Line= 3
    3032909.2321   13976030.7525    3034433.7614   13972802.3374
    3034931.0677   13971677.2837
#Sta/Elev= 30
    1706   162.2    1966   161.1  2113.9  157.51    2226   156.3    2446   160.6
  3004.2  158.66    3346   159.8    3446   158.2    3746   145.8    3866   144.3
    4286   145.5    4426   149.2    4486   145.7    4546   138.6    4686   146.2
    4846   147.2  4979.7  139.71  4987.7  134.15  4992.2  130.43  5009.5  129.92
  5012.4   134.1  5027.8  138.93  5059.9  141.37  5296.3     137  5436.3   141.3
  5676.3   140.4  6016.3   160.2  6156.3   164.7  6316.3   173.4  6506.3   175.7
#Mann= 6 ,-1 , 0
    1706     .09       0  2113.9     .07       0  3004.2     .15       0
  4987.7     .08       0  5012.4     .15       0  6506.3      .2       0
#XS Ineff= 2 , 0
       0    4500   157.5    5550       0     161
Permanent Ineff=
       F       F
Bank Sta=4987.7,5012.4
XS Rating Curve= 0
Exp/Cntr=.3,.1

Type RM Length L Ch R = 1 ,196302.3,475.15,2414.2,1474.1
BEGIN DESCRIPTION:
Cross Section XS146
Ineffective at Sta 2150 based on topo upstream of the cross section
END DESCRIPTION:
XS GIS Cut Line= 3
    3033039.6731   13976128.5832    3034922.9152   13973038.7617
    3036447.4445   13972394.7092
#Sta/Elev= 30
   544.4     161  1090.9  156.81  2016.1  159.02  2184.4   160.1  2564.4   144.4
  3084.4   145.8  3224.4   144.5  3324.4   138.6  3404.4   143.3  3544.4   146.6
  3664.4     144  3944.4     147  4322.9   147.3  4425.2  144.77  4702.9   136.5
  4910.5  140.47  4979.7  137.72  4992.2  128.44  5009.5  127.93  5012.4  132.11
  5027.8  136.94  5059.9  139.38  5062.9   142.6  5122.9   158.6  5182.9   170.9
  5262.9   175.5  5302.9   188.6  5322.9   191.8  5702.9   192.5  5817.9     197
#Mann= 7 ,-1 , 0
   544.4     .09       0  1090.9     .07       0  2016.1     .15       0
  4425.2     .15       0  4979.7     .08       0  5027.8     .15       0
  5817.9      .2       0
#XS Ineff= 2 ,-1
   544.4    2150     160    2150    2750   157.5
Permanent Ineff=
       F       F
Bank Sta=4979.7,5027.8
XS Rating Curve= 0
Exp/Cntr=.3,.1

Type RM Length L Ch R = 1 ,193888.1,720.86,901.1,801.91
BEGIN DESCRIPTION:
Cross Section XS145
END DESCRIPTION:
XS GIS Cut Line= 3
    3033039.6731   13976242.7191     3034776.169   13974326.8667
    3036007.2061   13973731.7296
#Sta/Elev= 30
  2043.9   160.8  2070.5  160.87  2223.9   161.3  2523.9   155.5  2827.7  158.44
  2943.9   155.8  3243.9   157.4  3503.9   151.9  3603.9   153.7  3856.5  152.76
  3858.4  152.77  3866.7  152.72  4243.9   151.2  4403.9   141.9  4463.9   141.1
  4543.9   143.4  4849.6   143.1  4910.5  137.79  4979.7  135.04  4992.2  125.76
  5009.5  125.25  5012.4  129.43  5027.8  134.26  5081.4  137.18  5085.3  137.26
  5449.6   145.2  5609.6   155.5  5889.6   182.8  5929.6   185.5    5997   184.6
#Mann= 11 ,-1 , 0
  2043.9     .07       0  2070.5     .09       0  2827.7     .07       0
  3856.5     .09       0  3858.4     .07       0  3866.7     .15       0
  4979.7     .08       0  5027.8     .15       0  5081.4     .15       0
  5085.3     .15       0    5997      .2       0
#XS Ineff= 2 , 0
       0    3900   157.5               0
Permanent Ineff=
       F       F
Bank Sta=4979.7,5027.8
XS Rating Curve= 0
Exp/Cntr=.3,.1

Type RM Length L Ch R = 1 ,192987.0,821.16,842.4,599.41
BEGIN DESCRIPTION:
Cross Section XS144
END DESCRIPTION:
XS GIS Cut Line= 3
    3033822.3191   13976381.3127    3034849.5421   13975239.9538
    3037001.8188   13974074.1373
#Sta/Elev= 30
    2776   162.6  2867.3  161.73    3356   153.6    3496   155.2    3656   153.2
    3836   155.1    4076     151  4311.5   152.7  4551.5   139.3  4683.8  138.52
    4940  140.79  4957.9  141.19  4983.6  135.18  4993.1  127.36  4999.9  126.54
  5006.6  127.71  5017.7  133.25  5093.1   135.1  5131.5   140.7  5211.5   145.5
  5351.5   143.5  5471.5   145.2  5611.5   141.6  5771.5   144.4  5931.5   141.9
  6391.5   148.3  6451.5   153.1  6591.5     170  6691.5   176.3  6759.3   178.2
#Mann= 8 , 1 , 0
    2776      .2       0    2776     .07       0  2867.3     .09       0
  4683.8     .15       0    4940     .15       0  4983.6     .08       0
  5017.7     .15       0  6759.3      .2       0
Bank Sta=4983.6,5017.7
XS Rating Curve= 0
Exp/Cntr=.3,.1

Type RM Length L Ch R = 1 ,192144.6,411.59,468.8,463.43
BEGIN DESCRIPTION:
Cross Section XS143
END DESCRIPTION:
XS GIS Cut Line= 2
    3034009.8281   13976951.9921    3037050.7342   13974555.1385
#Sta/Elev= 30
  2911.1   169.1  3111.1   168.1  3151.1   166.9  3531.1     167  3671.1   164.7
    3797  160.89  4091.1   154.6  4371.1   152.6  4431.1   151.2  4671.1   140.4
  4957.9  141.37  4983.6  135.36  4993.1  127.54  4999.9  126.72  5006.6  127.89
  5017.7  133.43  5090.6  135.21  5111.1   137.2  5151.1   135.8  5191.1   138.6
  5291.1   138.6  5371.1   141.9  5491.1   142.5  5931.1   138.2  6091.1   142.3
  6371.1   141.4  6471.1   147.1  6611.1   158.8  6691.1   167.2  6783.1   174.5
#Mann= 7 , 1 , 0
  2911.1      .2       0  2911.1     .07       0    3797     .09       0
  4983.6     .08       0  5017.7     .09       0  5090.6     .15       0
  6783.1      .2       0
Bank Sta=4983.6,5017.7
XS Rating Curve= 0
Exp/Cntr=.3,.1

Type RM Length L Ch R = 1 ,191675.8,464.59,919.8,729.3
BEGIN DESCRIPTION:
Cross Section XS142- Bridge 7- Exp
END DESCRIPTION:
XS GIS Cut Line= 2
    3034166.1426   13977228.5903    3037445.3981   13974885.4221
#Sta/Elev= 30
  2859.6   168.3  3802.7   165.8  3839.6   165.8  4059.6   159.2  4459.6   151.8
  4519.6   148.4  4779.6   138.5  4899.6   137.2  4939.6   135.4  4959.6   133.4
    4981  129.23  5002.1  126.83    5006  127.18  5009.4  129.23  5019.6   133.7
  5022.7  133.84  5079.6   137.2  5139.6   136.8  5179.6   134.9  5239.6   138.3
  5319.6   139.3  5459.6     144  5739.6   140.2  5939.6   135.7  6199.6   136.9
  6299.6   135.6  6339.6   137.4  6399.6   142.2  6699.6   173.2    6890   180.5
#Mann= 7 , 1 , 0
  2859.6      .2       0  2859.6     .07       0  3802.7     .09       0
    4981     .07       0  5009.4     .09       0  5022.7     .15       0
    6890      .2       0
Bank Sta=4981,5009.4
XS Rating Curve= 0
Exp/Cntr=.5,.3

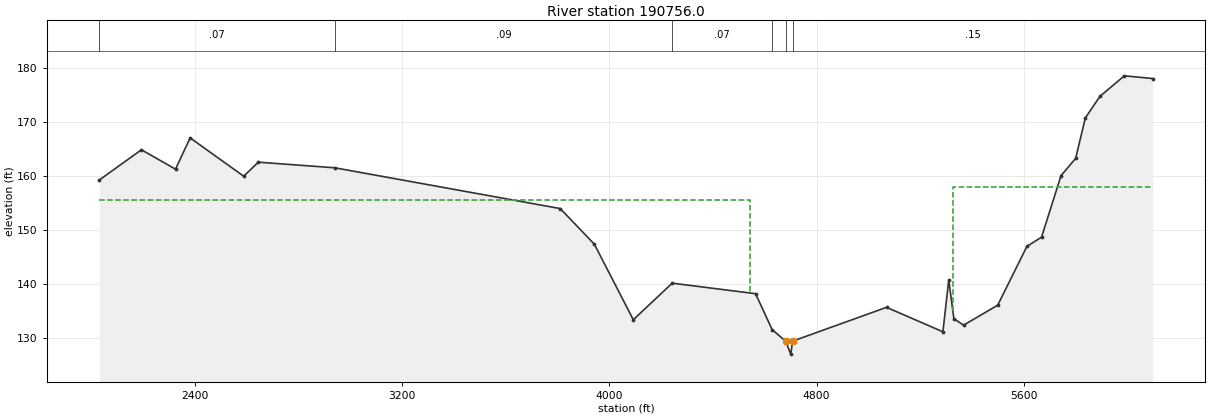
Type RM Length L Ch R = 1 ,190756.0,33,33,33
BEGIN DESCRIPTION:
Upstream Section of Union Pacific Railroad
END DESCRIPTION:
XS GIS Cut Line= 3
    3034382.9077   13977405.2401    3036857.0945   13975880.0564
     3038068.608    13975139.687
#Sta/Elev= 30
2032.085   159.32194.558   164.92326.115   161.32382.497   167.12589.229     160
2645.611   162.62940.392  161.563810.829     1543942.386   147.44092.737   133.4
  4242.9  140.184564.463  138.23 4628.55  131.574680.609  129.434700.437  127.03
4707.296  129.435069.923   135.75287.462  131.175310.109  140.775329.842   133.6
 5367.43   132.45498.987   136.1 5611.75     1475668.132   148.75743.307   160.1
5799.689   163.35837.276   170.85893.658   174.85987.627   178.6 6097.29   178.1
#Mann= 6 ,-1 , 0
2032.085     .07       02940.392     .09       0  4242.9     .07       0
 4628.55     .15       04680.609     .07       04707.296     .15       0
#XS Ineff= 2 , 0
       04541.723   155.55325.708       0     158
Permanent Ineff=
       F       F
Bank Sta=4680.609,4707.296
XS Rating Curve= 0
Skew Angle= 20
Exp/Cntr=.5,.3