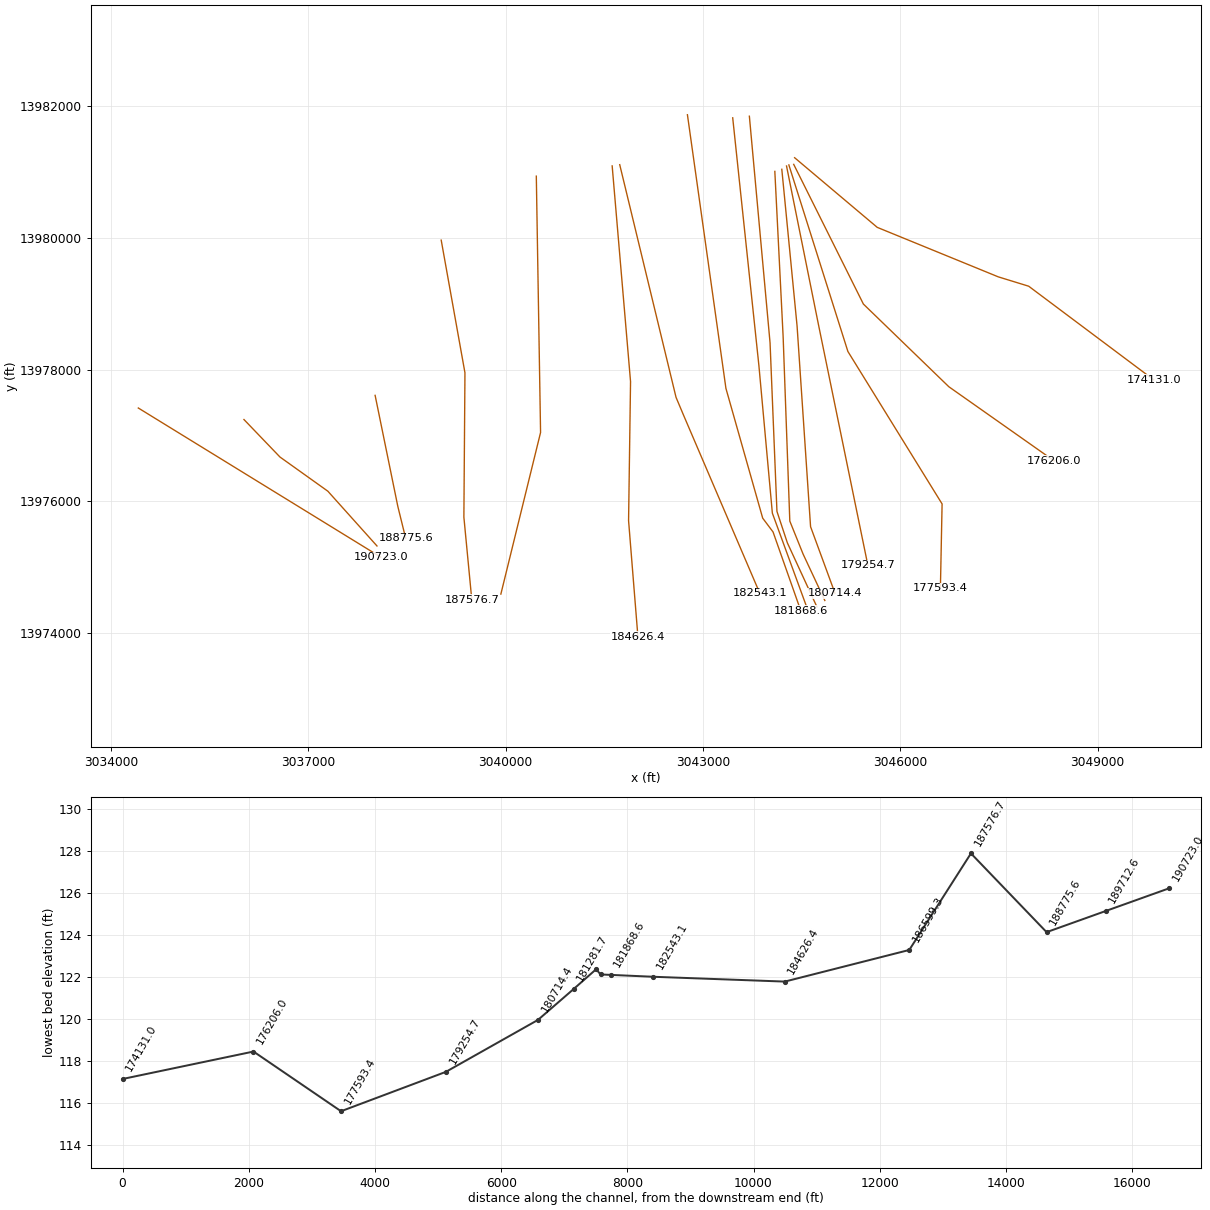
HEC-RAS study J100-00-00.prj: J100-00-00

--- J100-00-00.g01 (geometry) --- (continued)

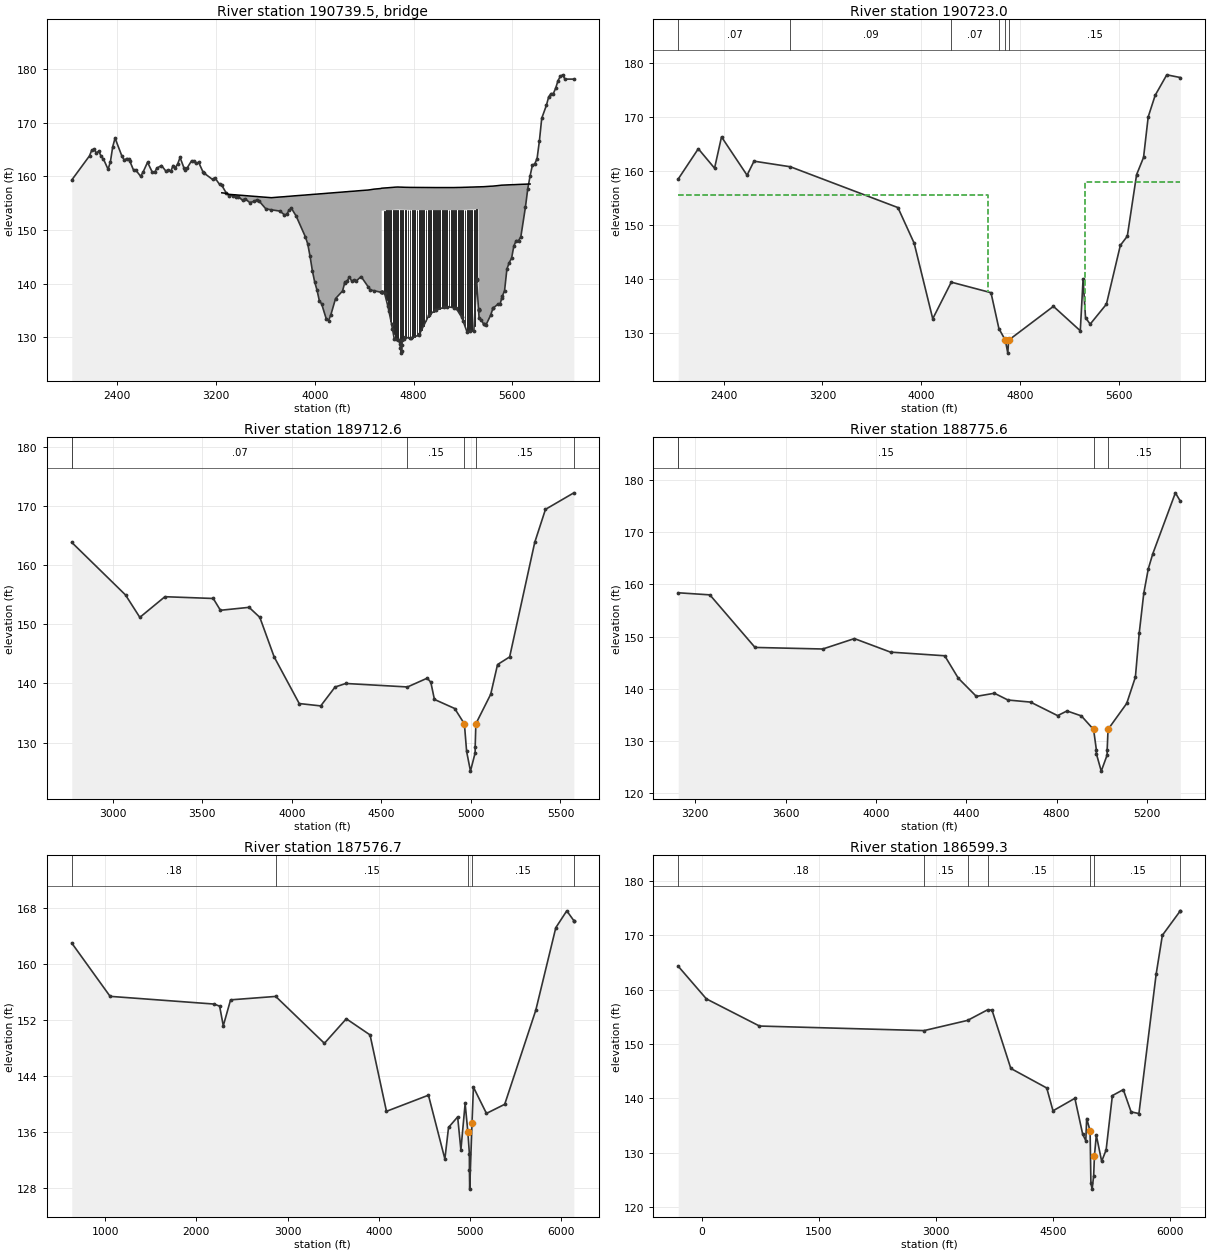
Type RM Length L Ch R = 3 ,190739.5,,,
BEGIN DESCRIPTION:
UNION PACIFIC RAILROAD
Structure ID: J100-00-00-07
Circular piers, twin-cylinder piers without diaphragm
END DESCRIPTION:
Node Name=UP Railroad 1
Bridge Culvert--1,0,-1,-1, 0
Deck Dist Width WeirC Skew NumUp NumDn MinLoCord MaxHiCord MaxSubmerge Is_Ogee
10,13,2.6,20, 111, 111, , , .95, 0, 1,1,,
3247.0143284.6023303.3953340.9833359.7773378.5713416.1583434.952 3472.543510.128
3528.9223547.7153604.0973648.357 3716.863754.4483773.2423792.0353810.8293848.417
3923.5933942.386 3961.183979.9743998.7684017.5624036.3554055.1494092.7374111.531
4130.3254167.9134224.294  4242.94243.0884261.8824280.676 4299.474318.2634337.057
4374.6454431.214 4449.82 4480.834532.7954541.6284541.7324541.816 4541.914564.463
4590.9624599.7014621.502 4628.554642.8334653.8284672.9034680.6094690.9454693.013
4700.4374704.1014706.0754707.2964718.5724729.9434772.2294782.0014844.7734846.276
4923.6134976.3314980.841 5048.785069.9235126.5875143.126 5190.115199.6955231.833
5254.4795287.4625310.0155310.109 5325.525325.6045325.7085325.8025329.8425348.636
 5367.43 5373.825386.2245423.8125442.6055445.9895480.1935498.9875514.8685517.781
5536.5755555.3695574.1635592.957 5611.755630.5445649.3385668.132 5705.725724.513
5743.307
  156.91  156.81  156.63  156.56  156.53  156.49  156.43  156.39  156.32  156.25
  156.22  156.18  156.08     156  156.13  156.19  156.23  156.26   156.3  156.37
   156.5  156.54  156.57  156.61  156.64  156.67  156.71  156.74  156.81  156.85
  156.88  156.95  157.05  157.09  157.09  157.12  157.16  157.19  157.22  157.26
  157.33  157.43  157.49   157.6  157.71  157.77  157.77  157.77  157.77  157.81
  157.85  157.87  157.91  157.92  157.95  157.97  157.99  157.98  157.97  157.97
  157.97  157.96  157.96  157.96  157.95  157.94  157.92  157.92  157.91  157.91
   157.9  157.89  157.89  157.89  157.89  157.89   157.9  157.92  157.93  157.95
  157.97  157.99  158.01  158.01  158.02  158.02  158.02  158.02  158.02  158.04
  158.05  158.06  158.08  158.14  158.16  158.17  158.25   158.3  158.34  158.34
  158.36  158.38   158.4  158.42  158.43  158.45  158.47  158.49  158.52  158.54
  158.55
                                                                                
                                                                                
                                                                                
                                                                                
                                                          153.57  153.57  153.61
  153.65  153.67  153.71  153.72  153.75  153.77  153.79  153.78  153.77  153.77
  153.77  153.76  153.76  153.76  153.75  153.74  153.72  153.72  153.71  153.71
   153.7  153.69  153.69  153.69  153.69  153.69   153.7  153.72  153.73  153.75
  153.77  153.79  153.81  153.81  153.82  153.82
                                                                                
                                                                                
        
3247.0143284.6023303.3953340.9833359.7773378.5713416.1583434.952 3472.543510.128
3528.9223547.7153604.0973648.357 3716.863754.4483773.2423792.0353810.8293848.417
3923.5933942.386 3961.183979.9743998.7684017.5624036.3554055.1494092.7374111.531
4130.3254167.9134224.294  4242.94243.0884261.8824280.676 4299.474318.2634337.057
4374.6454431.214 4449.82 4480.834532.7954541.6284541.7324541.816 4541.914564.463
4590.9624599.7014621.502 4628.554642.8334653.8284672.9034680.6094690.9454693.013
4700.4374704.1014706.0754707.2964718.5724729.9434772.2294782.0014844.7734846.276
4923.6134976.3314980.841 5048.785069.9235126.5875143.126 5190.115199.6955231.833
5254.4795287.4625310.0155310.109 5325.525325.6045325.7085325.8025329.8425348.636
 5367.43 5373.825386.2245423.8125442.6055445.9895480.1935498.9875514.8685517.781
5536.5755555.3695574.1635592.957 5611.755630.5445649.3385668.132 5705.725724.513
5743.307
  156.91  156.81  156.63  156.56  156.53  156.49  156.43  156.39  156.32  156.25
  156.22  156.18  156.08     156  156.13  156.19  156.23  156.26   156.3  156.37
   156.5  156.54  156.57  156.61  156.64  156.67  156.71  156.74  156.81  156.85
  156.88  156.95  157.05  157.09  157.09  157.12  157.16  157.19  157.22  157.26
  157.33  157.43  157.49   157.6  157.71  157.77  157.77  157.77  157.77  157.81
  157.85  157.87  157.91  157.92  157.95  157.97  157.99  157.98  157.97  157.97
  157.97  157.96  157.96  157.96  157.95  157.94  157.92  157.92  157.91  157.91
   157.9  157.89  157.89  157.89  157.89  157.89   157.9  157.92  157.93  157.95
  157.97  157.99  158.01  158.01  158.02  158.02  158.02  158.02  158.02  158.04
  158.05  158.06  158.08  158.14  158.16  158.17  158.25   158.3  158.34  158.34
  158.36  158.38   158.4  158.42  158.43  158.45  158.47  158.49  158.52  158.54
  158.55
                                                                                
                                                                                
                                                                                
                                                                                
                                                          153.57  153.57  153.61
  153.65  153.67  153.71  153.72  153.75  153.77  153.79  153.78  153.77  153.77
  153.77  153.76  153.76  153.76  153.75  153.74  153.72  153.72  153.71  153.71
   153.7  153.69  153.69  153.69  153.69  153.69   153.7  153.72  153.73  153.75
  153.77  153.79  153.81  153.81  153.82  153.82
                                                                                
                                                                                
        
Pier Skew= 20
Pier Skew, UpSta & Num, DnSta & Num=  ,4562.583, 2 ,4562.583, 2 , 0 , 0 , 0 ,,
     6.8     6.8
  137.23  154.61
     6.8     6.8
  136.45  153.83
Pier Skew, UpSta & Num, DnSta & Num=  ,4579.404, 2 ,4579.404, 2 , 0 , 0 , 0 ,,
     6.8     6.8
  135.77  154.63
     6.8     6.8
  134.99  153.85
Pier Skew, UpSta & Num, DnSta & Num=  ,4599.514, 2 ,4599.514, 2 , 0 , 0 , 0 ,,
     6.8     6.8
  133.76  154.67
     6.8     6.8
  132.98  153.89
Pier Skew, UpSta & Num, DnSta & Num=  ,4615.864, 2 ,4615.864, 2 , 0 , 0 , 0 ,,
     6.8     6.8
  131.97   154.7
     6.8     6.8
  131.19  153.92
Pier Skew, UpSta & Num, DnSta & Num=  ,4635.692, 2 ,4635.692, 2 , 0 , 0 , 0 ,,
     6.8     6.8
   129.5  154.74
     6.8     6.8
  128.72  153.96
Pier Skew, UpSta & Num, DnSta & Num=  ,4652.418, 2 ,4652.418, 2 , 0 , 0 , 0 ,,
     6.8     6.8
  128.65  154.77
     6.8     6.8
  127.87  153.99
Pier Skew, UpSta & Num, DnSta & Num=  ,4672.058, 2 ,4672.058, 2 , 0 , 0 , 0 ,,
     6.8     6.8
  128.49  154.79
     6.8     6.8
  127.71  154.01
Pier Skew, UpSta & Num, DnSta & Num=  ,4691.979, 2 ,4691.979, 2 , 0 , 0 , 0 ,,
     6.8     6.8
  126.98  154.77
     6.8     6.8
   126.2  153.99
Pier Skew, UpSta & Num, DnSta & Num=  ,4711.807, 2 ,4711.807, 2 , 0 , 0 , 0 ,,
     6.8     6.8
  128.51  154.76
     6.8     6.8
  127.73  153.98
Pier Skew, UpSta & Num, DnSta & Num=  ,4732.386, 2 ,4732.386, 2 , 0 , 0 , 0 ,,
     6.8     6.8
  128.95  154.74
     6.8     6.8
  128.17  153.96
Pier Skew, UpSta & Num, DnSta & Num=  ,4754.281, 2 ,4754.281, 2 , 0 , 0 , 0 ,,
     6.8     6.8
  128.88  154.73
     6.8     6.8
   128.1  153.95
Pier Skew, UpSta & Num, DnSta & Num=  ,4771.195, 2 ,4771.195, 2 , 0 , 0 , 0 ,,
     6.8     6.8
  128.83  154.72
     6.8     6.8
  128.05  153.94
Pier Skew, UpSta & Num, DnSta & Num=  ,4791.023, 2 ,4791.023, 2 , 0 , 0 , 0 ,,
     6.8     6.8
  128.88  154.72
     6.8     6.8
   128.1  153.94
Pier Skew, UpSta & Num, DnSta & Num=  ,4808.595, 2 ,4808.595, 2 , 0 , 0 , 0 ,,
     6.8     6.8
  129.06  154.72
     6.8     6.8
  128.28  153.94
Pier Skew, UpSta & Num, DnSta & Num=  ,4827.953, 2 ,4827.953, 2 , 0 , 0 , 0 ,,
     6.8     6.8
  129.26  154.71
     6.8     6.8
  128.48  153.93
Pier Skew, UpSta & Num, DnSta & Num=  ,4844.773, 2 ,4844.773, 2 , 0 , 0 , 0 ,,
     6.8     6.8
  129.43  154.71
     6.8     6.8
  128.65  153.93
Pier Skew, UpSta & Num, DnSta & Num=  ,4864.507, 2 ,4864.507, 2 , 0 , 0 , 0 ,,
     6.8     6.8
   130.3  154.71
     6.8     6.8
  129.52  153.93
Pier Skew, UpSta & Num, DnSta & Num=  ,4881.703, 2 ,4881.703, 2 , 0 , 0 , 0 ,,
     6.8     6.8
   131.1  154.71
     6.8     6.8
  130.32  153.93
Pier Skew, UpSta & Num, DnSta & Num=  ,4900.685, 2 ,4900.685, 2 , 0 , 0 , 0 ,,
     6.8     6.8
  131.97   154.7
     6.8     6.8
  131.19  153.92
Pier Skew, UpSta & Num, DnSta & Num=  ,4918.069, 2 ,4918.069, 2 , 0 , 0 , 0 ,,
     6.8     6.8
  132.78   154.7
     6.8     6.8
     132  153.92
Pier Skew, UpSta & Num, DnSta & Num=  ,4938.648, 2 ,4938.648, 2 , 0 , 0 , 0 ,,
     6.8     6.8
  133.34   154.7
     6.8     6.8
  132.56  153.92
Pier Skew, UpSta & Num, DnSta & Num=  ,4958.476, 2 ,4958.476, 2 , 0 , 0 , 0 ,,
     6.8     6.8
  133.69  154.69
     6.8     6.8
  132.91  153.91
Pier Skew, UpSta & Num, DnSta & Num=  ,4975.391, 2 ,4975.391, 2 , 0 , 0 , 0 ,,
     6.8     6.8
  133.99  154.69
     6.8     6.8
  133.21  153.91
Pier Skew, UpSta & Num, DnSta & Num=  ,4995.218, 2 ,4995.218, 2 , 0 , 0 , 0 ,,
     6.8     6.8
   134.2  154.69
     6.8     6.8
  133.42  153.91
Pier Skew, UpSta & Num, DnSta & Num=  ,5012.508, 2 ,5012.508, 2 , 0 , 0 , 0 ,,
     6.8     6.8
  134.31  154.69
     6.8     6.8
  133.53  153.91
Pier Skew, UpSta & Num, DnSta & Num=  ,5032.806, 2 ,5032.806, 2 , 0 , 0 , 0 ,,
     6.8     6.8
  134.45  154.69
     6.8     6.8
  133.67  153.91
Pier Skew, UpSta & Num, DnSta & Num=  ,5049.532, 2 ,5049.532, 2 , 0 , 0 , 0 ,,
     6.8     6.8
  134.56  154.69
     6.8     6.8
  133.78  153.91
Pier Skew, UpSta & Num, DnSta & Num=  ,5069.266, 2 ,5069.266, 2 , 0 , 0 , 0 ,,
     6.8     6.8
  134.69  154.69
     6.8     6.8
  133.91  153.91
Pier Skew, UpSta & Num, DnSta & Num=  ,5086.368, 2 ,5086.368, 2 , 0 , 0 , 0 ,,
     6.8     6.8
  134.63  154.69
     6.8     6.8
  133.85  153.91
Pier Skew, UpSta & Num, DnSta & Num=  ,5106.196, 2 ,5106.196, 2 , 0 , 0 , 0 ,,
     6.8     6.8
  134.56  154.69
     6.8     6.8
  133.78  153.91
Pier Skew, UpSta & Num, DnSta & Num=  ,5122.828, 2 ,5122.828, 2 , 0 , 0 , 0 ,,
     6.8     6.8
   134.5  154.69
     6.8     6.8
  133.72  153.91
Pier Skew, UpSta & Num, DnSta & Num=  ,5141.622, 2 ,5141.622, 2 , 0 , 0 , 0 ,,
     6.8     6.8
  134.43   154.7
     6.8     6.8
  133.65  153.92
Pier Skew, UpSta & Num, DnSta & Num=  ,5161.731, 2 ,5161.731, 2 , 0 , 0 , 0 ,,
     6.8     6.8
   133.7  154.71
     6.8     6.8
  132.92  153.93
Pier Skew, UpSta & Num, DnSta & Num=  ,5179.022, 2 ,5179.022, 2 , 0 , 0 , 0 ,,
     6.8     6.8
  133.06  154.72
     6.8     6.8
  132.28  153.94
Pier Skew, UpSta & Num, DnSta & Num=  ,5198.379, 2 ,5198.379, 2 , 0 , 0 , 0 ,,
     6.8     6.8
  132.09  154.73
     6.8     6.8
  131.31  153.95
Pier Skew, UpSta & Num, DnSta & Num=  ,5216.234, 2 ,5216.234, 2 , 0 , 0 , 0 ,,
     6.8     6.8
  130.94  154.74
     6.8     6.8
  130.16  153.96
Pier Skew, UpSta & Num, DnSta & Num=  ,5233.618, 2 ,5233.618, 2 , 0 , 0 , 0 ,,
     6.8     6.8
  130.02  154.75
     6.8     6.8
  129.24  153.97
Pier Skew, UpSta & Num, DnSta & Num=  ,5252.13, 2 ,5252.13, 2 , 0 , 0 , 0 ,,
     6.8     6.8
  130.07  154.77
     6.8     6.8
  129.29  153.99
Pier Skew, UpSta & Num, DnSta & Num=  ,5269.515, 2 ,5269.515, 2 , 0 , 0 , 0 ,,
     6.8     6.8
  130.12  154.78
     6.8     6.8
  129.34     154
Pier Skew, UpSta & Num, DnSta & Num=  ,5289.53, 2 ,5289.53, 2 , 0 , 0 , 0 ,,
     6.8     6.8
  130.55  154.79
     6.8     6.8
  129.77  154.01
Pier Skew, UpSta & Num, DnSta & Num=  ,5308.981, 2 ,5308.981, 2 , 0 , 0 , 0 ,,
     6.8     6.8
  138.79  154.81
     6.8     6.8
  138.01  154.03
BR Coef= 1 , 1 , 1 ,1.05, 0 ,,,.8,0,1.2,0,
WSPro=,,,, 1 ,,,, 0 ,,,, 0 ,,,,-1 ,-1 ,-1 , 0 , 0 , 0 , 0 , 0
BR U #Sta/Elev= 171
2032.085   159.32175.764   163.82194.558   164.92213.352     1652232.146   164.3
 2250.94   164.72269.733   163.72288.527   163.22326.115   161.32344.909   162.7
2363.703   165.52382.497   167.12438.878   163.72457.672     1632476.466   163.3
 2495.26   163.22501.932  162.832532.847   161.12551.641   161.12589.229     160
2608.023   160.72645.611   162.62683.198   160.82701.992   160.72720.786   161.5
2758.374     1622795.961   160.92814.755   161.22833.549   160.92852.343     162
2871.137   161.62889.931   162.32908.724   163.52940.392  161.562946.312   161.2
2965.106   161.53002.694   162.93021.488   162.83040.281   162.43059.075   162.6
3096.663   160.73103.335  160.583171.838   159.43190.632   159.7 3228.22   158.5
3247.014   158.33284.602   156.83303.395   156.43340.983   156.43359.777   156.2
3378.571   156.23416.158   155.53434.952   155.8 3472.54   155.13510.128   155.3
3528.922   155.63547.715   155.43604.097   153.93648.357  153.74 3716.86   153.5
3754.448   152.83773.242   152.93792.035   153.73810.829     1543848.417   152.6
3923.593   148.73942.386   147.4 3961.18   145.13979.974   142.43998.768   140.3
4017.562   138.84036.355   136.84055.149   136.24092.737   133.44111.531   133.1
4130.325   134.24167.913   137.24224.294   138.6  4242.9  140.184243.088   140.2
4261.882   140.54280.676   141.2 4299.47   140.44318.263   140.74337.057   140.5
4374.645   141.34431.214  139.42 4449.82   138.8 4480.83  138.654532.795  138.39
4541.628  138.344541.732  138.344541.816  138.34 4541.91  138.344564.463  138.23
4590.962  135.834599.701  134.874621.502  132.48 4628.55  131.574642.833  129.74
4653.828  129.654672.903  129.494680.609  129.434690.945  128.644693.013     128
4700.437  127.034704.101  127.384706.075  128.524707.296  129.434718.572  129.69
4729.943  129.964772.229  129.834782.001   129.84844.773  130.444846.276  130.51
4923.613  134.094976.331  135.034980.841  135.11 5048.78  135.565069.923   135.7
5126.587  135.495143.126  135.43 5190.11  133.695199.695  133.085231.833  131.02
5254.479  131.085287.462  131.175310.015  140.735310.109  140.77 5325.52  135.17
5325.604  135.145325.708   135.15325.802  135.075329.842   133.65348.636   133.2
 5367.43   132.4 5373.82  132.375386.224   132.35423.812   134.15442.605   135.4
5445.989  135.465480.193   136.15498.987   136.15514.868  137.375517.781   137.6
5536.575   138.75555.369   142.75574.163   143.95592.957   144.7 5611.75     147
5630.544     1485649.338     1485668.132   148.7 5705.72   154.35724.513   157.7
5743.307   160.15762.101   162.15780.895   162.35799.689   163.35818.482   166.6
5837.276   170.85874.864   173.25893.658   174.85912.452   175.45931.246   175.4
 5950.04   176.45968.833   177.85987.627   178.66006.421   178.96025.215   178.1
 6097.29   178.1
BR U #Mann= 6
2032.085     .072940.392     .09  4242.9     .07 4628.55     .154680.609    .065
4707.296     .15
BR D #Sta/Elev= 171
2032.085  158.512175.764  163.012194.558  164.112213.352  164.212232.146  163.51
 2250.94  163.912269.733  162.912288.527  162.412326.115  160.512344.909  161.91
2363.703  164.712382.497  166.312438.878  162.912457.672  162.212476.466  162.51
 2495.26  162.412501.932  162.042532.847  160.312551.641  160.312589.229  159.21
2608.023  159.912645.611  161.812683.198  160.012701.992  159.912720.786  160.71
2758.374  161.212795.961  160.112814.755  160.412833.549  160.112852.343  161.21
2871.137  160.812889.931  161.512908.724  162.712940.392  160.772946.312  160.41
2965.106  160.713002.694  162.113021.488  162.013040.281  161.613059.075  161.81
3096.663  159.913103.335  159.793171.838  158.613190.632  158.91 3228.22  157.71
3247.014  157.513284.602  156.013303.395  155.613340.983  155.613359.777  155.41
3378.571  155.413416.158  154.713434.952  155.01 3472.54  154.313510.128  154.51
3528.922  154.813547.715  154.613604.097  153.113648.357  152.95 3716.86  152.71
3754.448  152.013773.242  152.113792.035  152.913810.829  153.213848.417  151.81
3923.593  147.913942.386  146.61 3961.18  144.313979.974  141.613998.768  139.51
4017.562  138.014036.355  136.014055.149  135.414092.737  132.614111.531  132.31
4130.325  133.414167.913  136.414224.294  137.81  4242.9  139.394243.088  139.41
4261.882  139.714280.676  140.41 4299.47  139.614318.263  139.914337.057  139.71
4374.645  140.514431.214  138.63 4449.82  138.01 4480.83  137.864532.795   137.6
4541.628  137.554541.732  137.554541.816  137.55 4541.91  137.554564.463  137.44
4590.962  135.044599.701  134.084621.502  131.69 4628.55  130.784642.833  128.95
4653.828  128.864672.903   128.74680.609  128.644690.945  127.854693.013  127.21
4700.437  126.244704.101  126.594706.075  127.734707.296  128.644718.572   128.9
4729.943  129.174772.229  129.044782.001  129.014844.773  129.654846.276  129.72
4923.613   133.34976.331  134.244980.841  134.32 5048.78  134.775069.923  134.91
5126.587   134.75143.126  134.64 5190.11   132.95199.695  132.295231.833  130.23
5254.479  130.295287.462  130.385310.015  139.945310.109  139.98 5325.52  134.38
5325.604  134.355325.708  134.315325.802  134.285329.842  132.815348.636  132.41
 5367.43  131.61 5373.82  131.585386.224  131.515423.812  133.315442.605  134.61
5445.989  134.675480.193  135.315498.987  135.315514.868  136.585517.781  136.81
5536.575  137.915555.369  141.915574.163  143.115592.957  143.91 5611.75  146.21
5630.544  147.215649.338  147.215668.132  147.91 5705.72  153.515724.513  156.91
5743.307  159.315762.101  161.315780.895  161.515799.689  162.515818.482  165.81
5837.276  170.015874.864  172.415893.658  174.015912.452  174.615931.246  174.61
 5950.04  175.615968.833  177.015987.627  177.816006.421  178.116025.215  177.31
 6097.29  177.31
BR D #Mann= 6
2032.085     .072940.392     .09  4242.9     .07 4628.55     .154680.609    .065
4707.296     .15
BC Design=,, 0 ,, 0 ,,,,,,
BC HTab HWMax=178.9

Type RM Length L Ch R = 1 ,190723.0,1010.4,1010.4,1010.4
BEGIN DESCRIPTION:
Downstream Section of Union Pacific Railroad
END DESCRIPTION:
XS GIS Cut Line= 3
    3034417.4563   13977416.6882    3036365.9189   13976218.2614
    3038102.4149   13975150.2756
#Sta/Elev= 30
2032.085  158.512194.558  164.112326.115  160.512382.497  166.312589.229  159.21
2645.611  161.812940.392  160.773810.829  153.213942.386  146.614092.737  132.61
  4242.9  139.394564.463  137.44 4628.55  130.784680.609  128.644700.437  126.24
4707.296  128.645069.923  134.915287.462  130.385310.109  139.985329.842  132.81
 5367.43  131.615498.987  135.31 5611.75  146.215668.132  147.915743.307  159.31
5799.689  162.515837.276  170.015893.658  174.015987.627  177.81 6097.29  177.31
#Mann= 6 ,-1 , 0
2032.085     .07       02940.392     .09       0  4242.9     .07       0
 4628.55     .15       04680.609     .07       04707.296     .15       0
#XS Ineff= 2 , 0
       04541.723   155.55325.708       0     158
Permanent Ineff=
       F       F
Bank Sta=4680.609,4707.296
XS Rating Curve= 0
Skew Angle= 20
Exp/Cntr=.5,.3

Type RM Length L Ch R = 1 ,189712.6,1456.06,937,620.84
BEGIN DESCRIPTION:
Cross Section XS141
END DESCRIPTION:
XS GIS Cut Line= 4
    3036023.7089   13977241.3828    3036570.8941   13976671.7105
    3037299.0778   13976151.8491    3038045.8156   13975319.3373
#Sta/Elev= 30
  2771.8   163.9  3071.8     155  3151.8   151.2  3291.8   154.7  3561.7   154.4
  3601.7   152.4  3761.7   152.9  3821.7   151.2  3901.7   144.5  4041.7   136.6
  4161.7   136.2  4241.7   139.4  4301.7     140    4646  139.41  4756.4   140.9
  4776.4   140.2  4796.4   137.3  4909.6  135.76  4963.8  133.15 4976.21  128.48
  4997.7  125.15  5023.8  128.25  5023.9  129.19  5027.8  133.17  5110.5  138.16
  5148.9  143.21  5216.4   144.5  5356.4   163.9  5416.4   169.5  5574.8   172.3
#Mann= 6 , 1 , 0
  2771.8      .2       0  2771.8     .07       0    4646     .15       0
  4963.8     .07       0  5027.8     .15       0  5574.8      .2       0
Bank Sta=4963.8,5027.8
XS Rating Curve= 0
Exp/Cntr=.3,.1

Type RM Length L Ch R = 1 ,188775.6,1151.46,1198.9,1044.67
BEGIN DESCRIPTION:
Cross Section XS140
END DESCRIPTION:
XS GIS Cut Line= 3
     3038017.562   13977608.6715    3038362.3636   13975922.1416
    3038482.2946   13975434.9219
#Sta/Elev= 30
  3124.6   158.4  3264.6     158  3464.6   147.9  3764.6   147.6  3904.6   149.6
  4064.6     147  4304.6   146.3  4364.6     142  4444.6   138.5  4524.6   139.1
  4584.6   137.8  4684.6   137.4  4804.6   134.8    4846   135.7  4909.6  134.75
  4963.8  132.14  4976.1  128.23 4976.21  127.47  4997.7  124.14  5023.8  127.24
  5023.9  128.18  5027.8  132.16  5110.5  137.15  5148.9   142.2    5166   150.7
    5186   158.3    5206     163    5226   165.9    5326   177.6  5347.8     176
#Mann= 5 , 1 , 0
  3124.6      .2       0  3124.6     .15       0  4963.8     .07       0
  5027.8     .15       0  5347.8      .2       0
Bank Sta=4963.8,5027.8
XS Rating Curve= 0
Exp/Cntr=.3,.1

Type RM Length L Ch R = 1 ,187576.7,1028.49,977.4,679.44
BEGIN DESCRIPTION:
Cross Section XS139
END DESCRIPTION:
XS GIS Cut Line= 5
    3039022.0541   13979968.5187    3039382.9323   13977952.6916
    3039381.7772    13977766.081    3039366.7859   13975757.2365
    3039486.7169   13974505.4565
#Sta/Elev= 30
   634.6     163  1054.6   155.4  2194.6   154.3  2254.6     154  2294.6   151.2
  2374.6   154.9    2869  155.39  3402.5   148.7  3642.5   152.2  3902.5   149.9
  4082.5     139  4542.5   141.3  4722.5   132.2  4762.5   136.7  4862.5   138.2
    4898   133.5  4944.5  140.12  4974.5  136.02  4990.9  132.98  4991.5  130.64
  4994.4   127.9    5020  137.37  5035.2  142.45    5178   138.7    5378     140
    5718   153.4    5938   165.2    6058   167.6  6135.4   166.2  6135.5   166.2
#Mann= 5 ,-1 , 0
   634.6     .18       0    2869     .15       0  4974.5     .07       0
    5020     .15       0  6135.4      .2       0
Bank Sta=4974.5,5020
XS Rating Curve= 0
Exp/Cntr=.3,.1

Type RM Length L Ch R = 1 ,186599.3,1525.33,1972.9,1933.57
BEGIN DESCRIPTION:
Cross Section XS138
END DESCRIPTION:
XS GIS Cut Line= 3
    3040467.8405   13980941.1059    3040532.5779   13977044.5177
    3039928.9625   13974587.9091
#Sta/Elev= 30
  -300.4   164.3    59.6   158.3   739.6   153.3    2846  152.46  3403.6  154.34
    3661   156.3  3716.7   156.2  3956.7   145.5  4416.7   141.9  4496.7   137.7
  4776.7     140  4876.7   133.4  4916.7   132.2  4927.7  136.28  4971.5  134.03
    4982  124.36  4997.7  123.29  5017.3  125.75  5027.3  129.45  5051.2  133.22
  5119.8  128.41  5176.7   130.5  5256.7   140.5  5396.7   141.6  5496.7   137.5
  5596.7   137.2  5816.7   162.8  5896.7     170  6126.3   174.5  6126.4   174.5
#Mann= 7 ,-1 , 0
  -300.4     .18       0    2846     .15       0  3403.6     .08       0
    3661     .15       0  4971.5     .07       0  5027.3     .15       0
  6126.3      .2       0
Bank Sta=4971.5,5027.3
XS Rating Curve= 0
Exp/Cntr=.3,.1

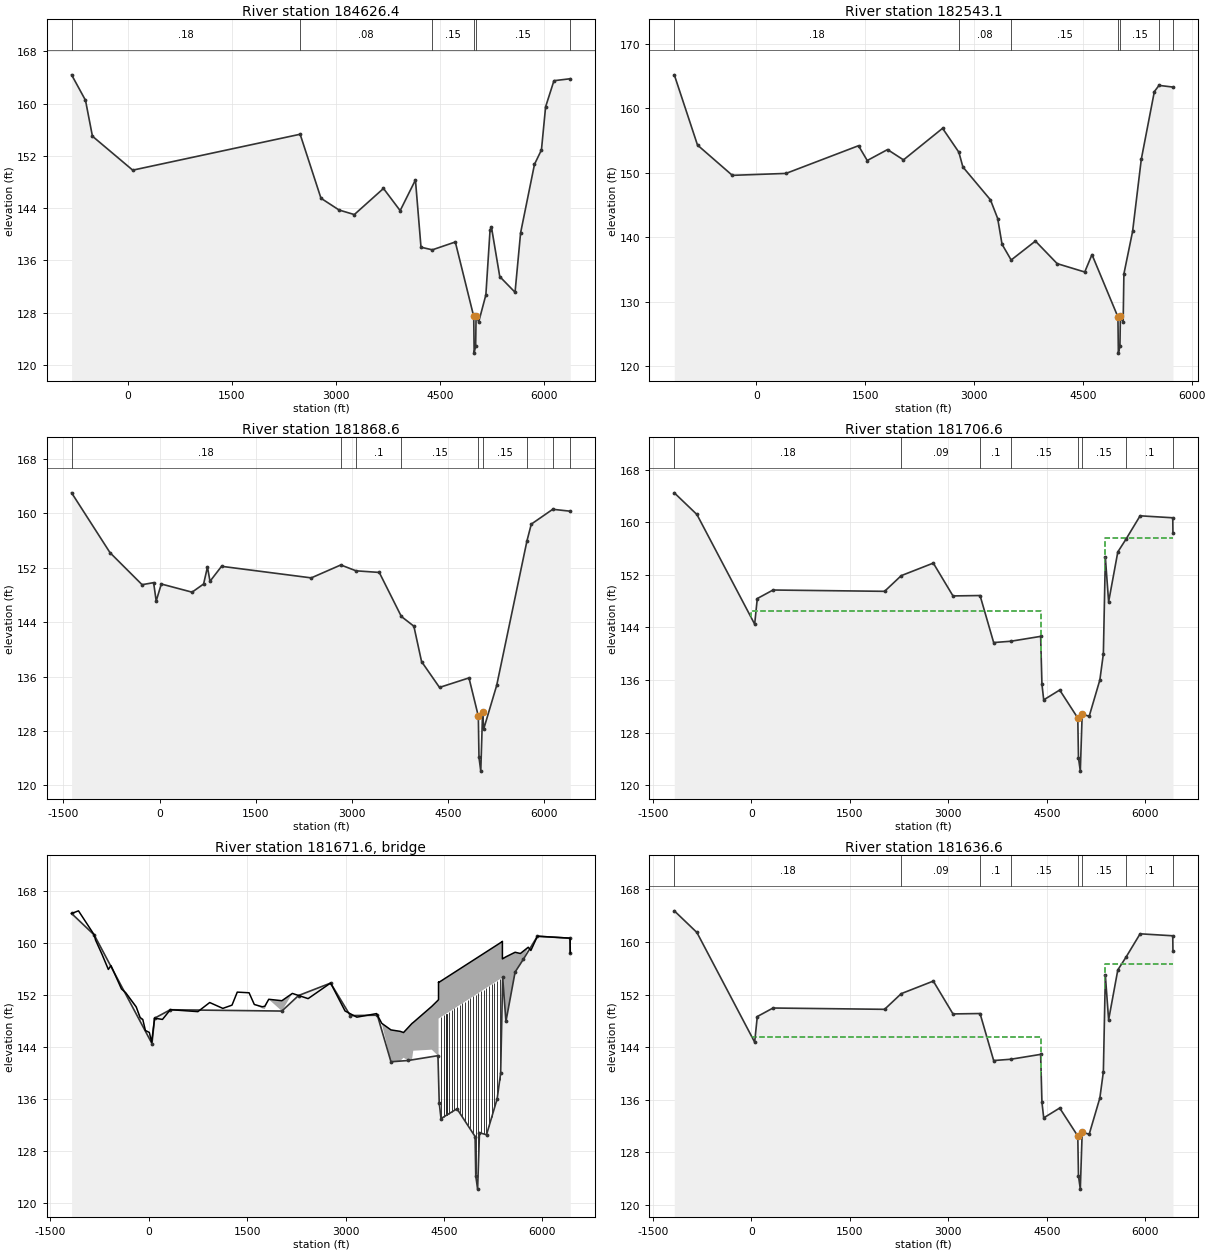
Type RM Length L Ch R = 1 ,184626.4,1395.02,2083.3,1782.64
BEGIN DESCRIPTION:
Cross Section XS137
END DESCRIPTION:
XS GIS Cut Line= 4
    3041620.9499    13981096.893    3041900.3285   13977818.5508
    3041870.3458   13975704.7667    3042012.7638   13973935.7842
#Sta/Elev= 30
  -805.9   164.4  -605.9   160.5  -505.9     155    74.1   149.8  2484.3   155.3
  2784.3   145.5  3044.3   143.7  3264.3     143  3684.3     147  3924.3   143.6
  4144.3   148.3  4224.3     138  4387.4   137.6  4718.3   138.8  4983.4   127.4
  4989.6  121.78  5011.2  122.88  5017.4  127.47  5055.5  126.58  5158.3   130.7
  5218.3   140.6  5238.3   141.1  5358.3   133.5  5578.3   131.1  5658.3   140.2
  5858.3   150.7  5958.3   152.9  6018.3   159.5  6138.3   163.5    6373   163.8
#Mann= 6 ,-1 , 0
  -805.9     .18       0  2484.3     .08       0  4387.4     .15       0
  4983.4     .07       0  5017.4     .15       0    6373      .2       0
Bank Sta=4983.4,5017.4
XS Rating Curve= 0
Exp/Cntr=.3,.1

Type RM Length L Ch R = 1 ,182543.1,549.91,674.5,531.09
BEGIN DESCRIPTION:
Cross Section XS136
END DESCRIPTION:
XS GIS Cut Line= 4
    3041735.8783   13981115.4362    3042591.8954    13977578.626
    3042702.3672   13977316.3397    3043864.1989   13974602.9005
#Sta/Elev= 30
 -1133.2   165.2  -813.2   154.3  -333.2   149.6   406.8   149.9  1406.8   154.2
  1526.8   151.9  1806.8   153.6  2026.8     152  2565.7   156.9  2790.3  153.19
  2845.7   150.9  3225.7   145.8  3325.7   142.9  3385.7   138.9  3511.4  136.46
  3845.7   139.4  4145.7   135.9  4525.7   134.6  4625.7   137.3  4983.4  127.63
  4989.6  122.01  5011.2  123.11  5017.4   127.7  5055.5  126.81  5065.7   134.3
  5185.7   140.9  5305.7   152.1  5485.7   162.6    5550  163.56    5742   163.3
#Mann= 7 ,-1 , 0
 -1133.2     .18       0  2790.3     .08       0  3511.4     .15       0
  4983.4     .07       0  5017.4     .15       0    5550     .14       0
    5742      .2       0
Bank Sta=4983.4,5017.4
XS Rating Curve= 0
Exp/Cntr=.3,.1

Type RM Length L Ch R = 1 ,181868.6,245.58,162,92.36
BEGIN DESCRIPTION:
Cross Section XS135- Bridge 6- Con
END DESCRIPTION:
XS GIS Cut Line= 5
    3042765.0278   13981874.8681    3043350.3543   13977714.6195
     3043909.173   13975742.2451    3044066.5825   13975532.3658
    3044487.7621   13974336.3999
#Sta/Elev= 30
 -1373.5     163  -773.5   154.2  -273.5   149.5   -93.5   149.8   -53.5   147.1
    26.5   149.6   506.5   148.4   686.5   149.6   746.5   152.1   786.5     150
   966.5   152.2  2366.5   150.5  2827.7   152.4  3064.7  151.54  3427.7   151.3
  3772.2  144.83  3967.7   143.4  4087.7   138.2  4367.7   134.4  4827.7   135.8
  4973.4  130.19  4983.6  124.14  5011.8   122.1  5040.3  130.77  5057.7   128.3
  5260.1   134.7  5732.8  155.95  5800.1   158.4  6134.9  160.58    6408   160.3
#Mann= 9 ,-1 , 0
 -1373.5     .18       0  2827.7     .08       0  3064.7      .1       0
  3772.2     .15       0  4973.4     .07       0  5040.3     .15       0
  5732.8     .14       0  6134.9     .07       0    6408      .2       0
Bank Sta=4973.4,5040.3
XS Rating Curve= 0
Exp/Cntr=.5,.3

Type RM Length L Ch R = 1 ,181706.6,70,70,70
BEGIN DESCRIPTION:
Upstream Section of FM 2978
END DESCRIPTION:
XS GIS Cut Line= 5
    3043453.3421   13981827.7653    3043851.5479   13978061.0327
     3044056.095   13975818.1334    3044189.5891   13975453.3121
    3044592.3115   13974352.7255
#Sta/Elev= 30
 -1176.4   164.5  -831.5   161.2    48.5   144.5    88.5   148.4   328.5   149.7
  2028.5   149.5  2282.9  151.89  2771.2   153.8  3071.2   148.8  3483.8  148.86
  3691.2   141.7  3954.4   141.9  4407.3  142.64  4426.9  135.38  4453.9  132.97
  4697.7  134.47  4973.4  130.21  4983.6  124.16  5011.8  122.12  5040.3  130.79
  5147.3  130.48  5309.7     136  5363.2  139.98  5393.4  154.67  5443.4   147.9
  5583.4   155.5    5708  157.44  5923.4     161  6420.9   160.7  6423.7   158.4
#Mann= 8 ,-1 , 0
 -1176.4     .18       0  2282.9     .09       0  3483.8      .1       0
  3954.4     .15       0  4973.4     .07       0  5040.3     .15       0
    5708      .1       0  6423.7      .2       0
#XS Ineff= 2 , 0
       0    4416   146.5    5389       0   157.6
Permanent Ineff=
       F       F
Bank Sta=4973.4,5040.3
XS Rating Curve= 0
Exp/Cntr=.5,.3

Type RM Length L Ch R = 3 ,181671.6,,,
BEGIN DESCRIPTION:
FM 2978
Structure ID: J100-00-00-06
Square  nose piers
END DESCRIPTION:
Node Name=FM 2978
Bridge Culvert--1,0,-1,-1, 0
Deck Dist Width WeirC Skew NumUp NumDn MinLoCord MaxHiCord MaxSubmerge Is_Ogee
10,50,2.6,0, 60, 60, , , .95, 0, 1,1,,
 -1176.4 -1071.5  -831.5  -811.5  -711.5  -616.4  -576.4  -416.4  -351.5  -191.5
  -131.5   -91.5   -51.5     8.5    43.6    88.5   208.5   328.5   748.5   928.5
  1128.5  1268.5  1348.5  1528.5  1608.5  1728.5  1768.5  1828.5  2028.5  2188.5
  2428.5  2771.2  2991.2  3171.2  3471.2  3551.2  3691.2  3831.2  3882.8  4011.2
  4031.2  4313.3  4407.3 4415.99  4416.1 4416.41  4416.5 5389.09  5389.2  5389.6
 5389.71  5393.4  5443.4  5583.4  5663.4  5783.4  5823.4  5923.4  6420.9  6423.7
   164.5  164.91  161.21  160.42  158.19   155.9   156.5   152.9  152.32  150.14
   148.5  148.21  146.51  146.21  144.72  148.41  148.21  149.71  149.41  150.81
  149.91  150.41  152.41  152.31  150.51  150.16  150.24  151.31  151.09  152.21
  151.41  153.81  149.51  148.56  149.11  147.61   146.6  146.38   146.2  147.59
  147.75  150.22  151.15  151.27  153.97  153.92  153.88  160.19  160.22  160.22
  157.52  157.54  157.84  158.54  158.35  159.31  158.81  161.01  160.71   158.4
   164.5   164.9   161.2   159.6   156.9   155.3  154.82  151.72   150.2   149.9
     148   148.2   146.5   146.2  144.71   148.4   148.2   149.7   149.4   150.8
   149.9   150.4   152.4   152.3   150.5   149.9   149.8   151.3   149.5   152.2
   151.4   153.8   149.5   148.5   149.1   147.6   141.7   141.2  142.32   141.2
   143.4  143.56  142.64  139.42  139.38  139.27  148.34  154.65  152.63  152.82
  152.88  154.67   147.9   155.5   156.1   159.3   158.8     161   160.7   158.4
 -1176.4 -1071.5  -831.5  -811.5  -711.5  -616.4  -576.4  -351.5  -191.5  -131.5
   -91.5   -51.5     8.5    48.5    88.5   208.5   328.5   748.5   928.5  1128.5
  1268.5  1348.5  1528.5  1608.5  1728.5  1768.5  1828.5  2028.5  2188.5  2428.5
  2771.2  3071.2  3471.2  3551.2  3691.2  3782.8  3831.2  3911.2  4011.2  4031.2
  4313.3  4407.3 4415.99  4416.1 4416.41  4416.5 5389.09  5389.2  5389.6 5389.71
  5393.4  5443.4  5583.4  5663.4    5708  5783.4  5823.4  5923.4  6420.9  6423.7
  164.78  165.18  161.48  160.42  158.19   155.9   156.5  152.32  150.18   148.5
  148.48  146.78  146.48  144.78  148.68  148.48  149.98  149.68  151.08  150.18
  150.68  152.68  152.58  150.78  150.18  150.24  151.58  151.09  152.48  151.68
  154.08  149.08  149.38  147.88   146.6   146.2  146.38   146.7  147.59  147.75
  150.22  151.15  151.27  153.97  153.92  153.88  160.19  160.22  160.22  157.52
  157.54  157.84  158.54  158.35  158.25  159.58  159.08  161.28  160.98  158.68
  164.78  165.18  161.48  159.88  157.18  155.58   155.1  150.48  150.18  148.28
  148.48  146.78  146.48  144.78  148.68  148.48  149.98  149.68  151.08  150.18
  150.68  152.68  152.58  150.78  150.18  150.08  151.58  149.78  152.48  151.68
  154.08  149.08  149.38  147.88  141.98  141.65  141.48  142.88  141.48  143.68
  143.84  142.92   139.7  139.66  139.55  148.62  154.93  152.91   153.1  153.16
  154.95  148.18  155.78  156.38  157.72  159.58  159.08  161.28  160.98  158.68
Pier Skew, UpSta & Num, DnSta & Num=  ,4456.9, 2 ,4456.9, 2 , 0 , 0 , 0 ,,
     1.3     1.3
  132.02  149.56
     1.3     1.3
   132.3  149.84
Pier Skew, UpSta & Num, DnSta & Num=  ,4497, 2 ,4497, 2 , 0 , 0 , 0 ,,
     1.3     1.3
  132.92  149.94
     1.3     1.3
   133.2  150.22
Pier Skew, UpSta & Num, DnSta & Num=  ,4537.2, 2 ,4537.2, 2 , 0 , 0 , 0 ,,
     1.3     1.3
  132.74  150.21
     1.3     1.3
  133.02  150.49
Pier Skew, UpSta & Num, DnSta & Num=  ,4577.5, 2 ,4577.5, 2 , 0 , 0 , 0 ,,
     1.3     1.3
  132.71  150.49
     1.3     1.3
  132.99  150.77
Pier Skew, UpSta & Num, DnSta & Num=  ,4617.9, 2 ,4617.9, 2 , 0 , 0 , 0 ,,
     1.3     1.3
  132.88  150.77
     1.3     1.3
  133.16  151.05
Pier Skew, UpSta & Num, DnSta & Num=  ,4658.3, 2 ,4658.3, 2 , 0 , 0 , 0 ,,
     1.3     1.3
   133.2  151.05
     1.3     1.3
  133.48  151.33
Pier Skew, UpSta & Num, DnSta & Num=  ,4698.9, 2 ,4698.9, 2 , 0 , 0 , 0 ,,
     1.3     1.3
  133.45   151.3
     1.3     1.3
  133.73  151.58
Pier Skew, UpSta & Num, DnSta & Num=  ,4739.3, 2 ,4739.3, 2 , 0 , 0 , 0 ,,
     1.3     1.3
  133.06  151.55
     1.3     1.3
  133.34  151.83
Pier Skew, UpSta & Num, DnSta & Num=  ,4779.9, 2 ,4779.9, 2 , 0 , 0 , 0 ,,
     1.3     1.3
  132.84  151.82
     1.3     1.3
  133.12   152.1
Pier Skew, UpSta & Num, DnSta & Num=  ,4820.5, 2 ,4820.5, 2 , 0 , 0 , 0 ,,
     1.3     1.3
  132.54  152.08
     1.3     1.3
  132.82  152.36
Pier Skew, UpSta & Num, DnSta & Num=  ,4861.2, 2 ,4861.2, 2 , 0 , 0 , 0 ,,
     1.3     1.3
  132.38  152.35
     1.3     1.3
  132.66  152.63
Pier Skew, UpSta & Num, DnSta & Num=  ,4901.9, 2 ,4901.9, 2 , 0 , 0 , 0 ,,
     1.3     1.3
  131.62   152.6
     1.3     1.3
   131.9  152.88
Pier Skew, UpSta & Num, DnSta & Num=  ,4942.5, 2 ,4942.5, 2 , 0 , 0 , 0 ,,
     1.3     1.3
  130.29  152.87
     1.3     1.3
  130.57  153.15
Pier Skew, UpSta & Num, DnSta & Num=  ,4983.1, 2 ,4983.1, 2 , 0 , 0 , 0 ,,
     1.3     1.3
  123.13  153.13
     1.3     1.3
  123.41  153.41
Pier Skew, UpSta & Num, DnSta & Num=  ,5023.8, 2 ,5023.8, 2 , 0 , 0 , 0 ,,
     1.3     1.3
   125.7  153.38
     1.3     1.3
  125.98  153.66
Pier Skew, UpSta & Num, DnSta & Num=  ,5064.4, 2 ,5064.4, 2 , 0 , 0 , 0 ,,
     1.3     1.3
  130.27  153.63
     1.3     1.3
  130.55  153.91
Pier Skew, UpSta & Num, DnSta & Num=  ,5105, 2 ,5105, 2 , 0 , 0 , 0 ,,
     1.3     1.3
  130.15  153.88
     1.3     1.3
  130.43  154.16
Pier Skew, UpSta & Num, DnSta & Num=  ,5145.6, 2 ,5145.6, 2 , 0 , 0 , 0 ,,
     1.3     1.3
   129.5  154.12
     1.3     1.3
  129.78   154.4
Pier Skew, UpSta & Num, DnSta & Num=  ,5186.1, 2 ,5186.1, 2 , 0 , 0 , 0 ,,
     1.3     1.3
  131.18  154.37
     1.3     1.3
  131.46  154.65
Pier Skew, UpSta & Num, DnSta & Num=  ,5226.6, 2 ,5226.6, 2 , 0 , 0 , 0 ,,
     1.3     1.3
  131.91  154.62
     1.3     1.3
  132.19   154.9
Pier Skew, UpSta & Num, DnSta & Num=  ,5267.1, 2 ,5267.1, 2 , 0 , 0 , 0 ,,
     1.3     1.3
  132.44  154.88
     1.3     1.3
  132.72  155.16
Pier Skew, UpSta & Num, DnSta & Num=  ,5307.5, 2 ,5307.5, 2 , 0 , 0 , 0 ,,
     1.3     1.3
  134.81  155.14
     1.3     1.3
  135.09  155.42
Pier Skew, UpSta & Num, DnSta & Num=  ,5348.1, 2 ,5348.1, 2 , 0 , 0 , 0 ,,
     1.3     1.3
  137.83  155.31
     1.3     1.3
  138.11  155.59
Abutment Skew #Up #Dn= , 2 , 2
  4416.3  4456.5
  148.34  133.03
  4416.3  4456.5
  148.62  133.31
Abutment Skew #Up #Dn= , 2 , 2
  5348.9 5389.29
  138.94  154.65
  5348.9 5389.29
  139.22  154.93
BR Coef= 1 , 1 , 1 ,1.25, 0 ,,,.8,0,2,0,
WSPro=,,,, 1 ,,,, 0 ,,,, 0 ,,,,-1 ,-1 ,-1 , 0 , 0 , 0 , 0 , 0
BR U #Sta/Elev= 30
 -1176.4   164.5  -831.5   161.2    48.5   144.5    88.5   148.4   328.5   149.7
  2028.5   149.5  2282.9  151.89  2771.2   153.8  3071.2   148.8  3483.8  148.86
  3691.2   141.7  3954.4   141.9  4407.3  142.64  4426.9  135.38  4453.9  132.97
  4697.7  134.47  4973.4  130.21  4983.6  124.16  5011.8  122.12  5040.3  130.79
  5147.3  130.48  5309.7     136  5363.2  139.98  5393.4  154.67  5443.4   147.9
  5583.4   155.5    5708  157.44  5923.4     161  6420.9   160.7  6423.7   158.4
BR U #Mann= 7
 -1176.4     .18  2282.9     .09  3483.8      .1  3954.4     .15  4973.4    .065
  5040.3     .15    5708      .1
BR U Banks=4973.4,5040.3
BR D #Sta/Elev= 30
 -1176.4  164.78  -831.5  161.48    48.5  144.78    88.5  148.68   328.5  149.98
  2028.5  149.78  2282.9  152.17  2771.2  154.08  3071.2  149.08  3483.8  149.14
  3691.2  141.98  3954.4  142.18  4407.3  142.92  4426.9  135.66  4453.9  133.25
  4697.7  134.75  4973.4  130.49  4983.6  124.44  5011.8   122.4  5040.3  131.07
  5147.3  130.76  5309.7  136.28  5363.2  140.26  5393.4  154.95  5443.4  148.18
  5583.4  155.78    5708  157.72  5923.4  161.28  6420.9  160.98  6423.7  158.68
BR D #Mann= 7
 -1176.4     .18  2282.9     .09  3483.8      .1  3954.4     .15  4973.4    .065
  5040.3     .15    5708      .1
BR D Banks=4973.4,5040.3
BC Design=,, 0 ,, 0 ,,,,,,
BC HTab HWMax=164.9

Type RM Length L Ch R = 1 ,181636.6,354.9,354.9,354.9
BEGIN DESCRIPTION:
Downstream Section of FM 2978
END DESCRIPTION:
XS GIS Cut Line= 5
    3043706.6262   13981852.3742    3044021.0693    13978407.446
    3044125.8429   13975845.3103    3044283.9574   13975367.4607
    3044733.6987   13974393.0212
#Sta/Elev= 30
 -1176.4  164.75  -831.5  161.45    48.5  144.75    88.5  148.65   328.5  149.95
  2028.5  149.75  2282.9  152.14  2771.2  154.05  3071.2  149.05  3483.8  149.11
  3691.2  141.95  3954.4  142.15  4407.3  142.89  4426.9  135.63  4453.9  133.22
  4697.7  134.72  4973.4  130.46  4983.6  124.41  5011.8  122.37  5040.3  131.04
  5147.3  130.73  5309.7  136.25  5363.2  140.23  5393.4  154.92  5443.4  148.15
  5583.4  155.75    5708  157.69  5923.4  161.25  6420.9  160.95  6423.7  158.65
#Mann= 8 ,-1 , 0
 -1176.4     .18       0  2282.9     .09       0  3483.8      .1       0
  3954.4     .15       0  4973.4     .07       0  5040.3     .15       0
    5708      .1       0  6423.7      .2       0
#XS Ineff= 2 , 0
       0    4416   145.5    5389       0   156.6
Permanent Ineff=
       F       F
Bank Sta=4973.4,5040.3
XS Rating Curve= 0
Exp/Cntr=.5,.3

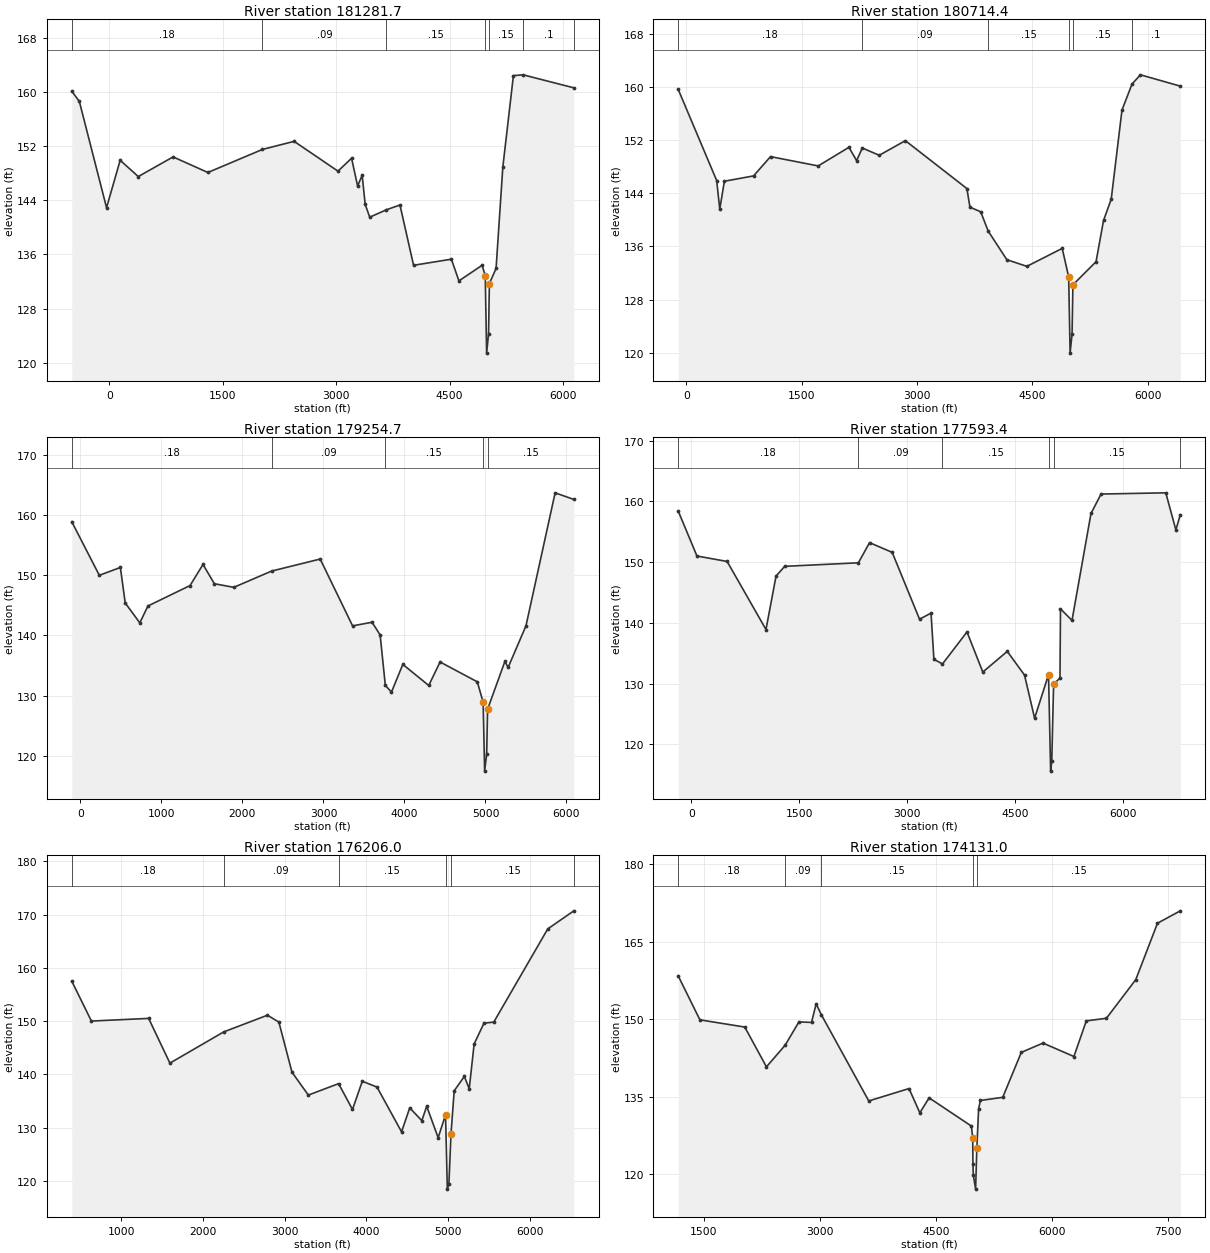
Type RM Length L Ch R = 1 ,181281.7,305.39,567.3,255.02
BEGIN DESCRIPTION:
Cross Section XS134- Bridge 6 Exp
END DESCRIPTION:
XS GIS Cut Line= 5
    3044093.6983   13981013.5428    3044220.0726   13978495.8919
    3044321.4359    13975697.271    3044523.8194   13975195.0599
    3044853.6297   13974490.4652
#Sta/Elev= 30
  -497.3   160.1  -397.3   158.6   -37.3   142.9   142.7   149.9   382.7   147.5
   842.7   150.4  1302.7   148.1  2023.5   151.5  2443.5   152.7  3023.5   148.3
  3203.5   150.2  3283.5   146.1  3343.5   147.7  3383.5   143.4  3443.5   141.5
  3665.3   142.6  3843.5   143.3  4023.5   134.4  4523.5   135.3  4623.5   132.1
  4930.1   134.4  4971.5  132.86  4989.8  121.43  5015.2  124.27  5026.3   131.7
  5114.8  133.94    5204   148.9    5344   162.4  5472.4  162.52  6143.4   160.6
#Mann= 7 ,-1 , 0
  -497.3     .18       0  2023.5     .09       0  3665.3     .15       0
  4971.5     .07       0  5026.3     .15       0  5472.4      .1       0
  6143.4      .2       0
Bank Sta=4971.5,5026.3
XS Rating Curve= 0
Exp/Cntr=.3,.1

Type RM Length L Ch R = 1 ,180714.4,645.25,1459.7,721.49
BEGIN DESCRIPTION:
Cross Section XS133
END DESCRIPTION:
XS GIS Cut Line= 4
    3044199.7812   13981045.2491    3044431.8927    13978662.701
    3044636.9521   13975612.4429    3045008.6222   13974599.9623
#Sta/Elev= 30
  -106.4   159.6   393.6   145.9   433.6   141.6   493.6   145.8   873.6   146.6
  1093.6   149.5  1713.6   148.1  2113.6   150.9  2213.6   148.9  2287.5   150.8
  2507.4   149.7  2847.4   151.9  3647.4   144.7  3687.4   141.9  3827.4   141.2
  3925.1  138.29  4167.4     134  4427.4     133  4887.4   135.7  4971.5  131.38
  4989.8  119.95  5015.2  122.79  5026.3  130.22  5327.4   133.7  5424.6   139.9
  5524.6   143.1  5664.6   156.5  5795.4  160.42  5904.6   161.8  6423.1   160.1
#Mann= 6 ,-1 , 0
  -106.4     .18       0  2287.5     .09       0  3925.1     .15       0
  4971.5     .08       0  5026.3     .15       0  5795.4      .1       0
Bank Sta=4971.5,5026.3
XS Rating Curve= 0
Exp/Cntr=.3,.1

Type RM Length L Ch R = 1 ,179254.7,855.84,1661.3,1338.45
BEGIN DESCRIPTION:
Cross Section XS132
END DESCRIPTION:
XS GIS Cut Line= 3
    3044271.4168   13981095.5495    3044758.1834   13978677.7853
    3045508.4544   13975022.8972
#Sta/Elev= 30
  -106.3   158.9   233.7     150   493.7   151.3   553.7   145.4   733.7   142.1
   833.7   144.9  1353.7   148.3  1513.7   151.8  1653.7   148.6  1893.7     148
  2359.9   150.7    2960   152.7    3360   141.6    3600   142.2    3700   140.1
  3764.2  131.71    3840   130.6    3980   135.2    4300   131.7    4440   135.6
    4900   132.3  4971.5   128.9  4989.8  117.47  5015.2  120.31  5026.3  127.74
    5240   135.7    5280   134.7    5500   141.6    5860   163.7  6091.1   162.6
#Mann= 5 ,-1 , 0
  -106.3     .18       0  2359.9     .09       0  3764.2     .15       0
  4971.5     .08       0  5026.3     .15       0
Bank Sta=4971.5,5026.3
XS Rating Curve= 0
Exp/Cntr=.3,.1

Type RM Length L Ch R = 1 ,177593.4,1076.63,1387.4,1415.9
BEGIN DESCRIPTION:
Cross Section XS131
END DESCRIPTION:
XS GIS Cut Line= 4
    3044306.9605   13981111.9509     3045204.394   13978275.7327
    3046636.2809   13975958.4806    3046610.6485   13974676.8595
#Sta/Elev= 30
  -183.4   158.4    76.6     151   496.6   150.1  1036.6   138.9  1176.6   147.7
  1296.6   149.3  2321.5  149.88  2476.6   153.2  2791.4   151.6  3171.4   140.6
  3331.4   141.6  3371.4     134  3490.8  133.23  3831.4   138.5  4051.4   131.9
  4391.4   135.3  4631.4   131.4  4771.4   124.3    4965  131.47  4994.3  115.59
  5010.1  117.21  5035.6   129.9  5124.3  130.92  5131.4   142.3  5291.4   140.4
  5555.4     158  5695.4   161.2  6595.4   161.4  6735.4   155.3  6797.3   157.8
#Mann= 6 ,-1 , 0
  -183.4     .18       0  2321.5     .09       0  3490.8     .15       0
    4965     .08       0  5035.6     .15       0  6797.3      .2       0
Bank Sta=4965,5035.6
XS Rating Curve= 0
Exp/Cntr=.3,.1

Type RM Length L Ch R = 1 ,176206.0,1663.42,2075,1991.4
BEGIN DESCRIPTION:
Cross Section XS130
END DESCRIPTION:
XS GIS Cut Line= 4
      3044380.78   13981120.1471    3045439.7613   13978996.8377
    3046738.8106   13977739.9338    3048340.8369   13976612.1073
#Sta/Elev= 30
   396.4   157.5   636.4     150  1336.4   150.5  1596.4   142.1    2254  147.96
  2789.1   151.1  2929.1   149.8  3089.1   140.4  3289.1   136.1    3659  138.25
  3829.1   133.4  3949.1   138.7  4129.1   137.6  4429.1   129.2  4529.1   133.7
  4676.7   131.3  4736.7     134  4876.7   128.1  4967.2  132.41  4988.7  118.44
  5008.1  119.41  5033.9  128.87  5072.8   136.9  5196.7   139.6  5256.7   137.3
  5316.7   145.7  5436.7   149.6  5556.7   149.8  6216.7   167.3  6535.9   170.7
#Mann= 6 ,-1 , 0
   396.4     .18       0    2254     .09       0    3659     .15       0
  4967.2     .08       0  5033.9     .15       0  6535.9      .2       0
Bank Sta=4967.2,5033.9
XS Rating Curve= 0
Exp/Cntr=.3,.1

Type RM Length L Ch R = 1 ,174131.0,1330.2,1164.1,754.45
BEGIN DESCRIPTION:
Cross Section XS129
END DESCRIPTION:
XS GIS Cut Line= 5
    3044394.4582   13981221.3052    3045650.3877   13980162.5886
    3047490.9835   13979409.9746    3047952.6279   13979268.0631
    3049853.6695    13977844.452
#Sta/Elev= 30
  1169.7   158.4  1449.7   149.9  2029.7   148.5  2309.7   140.8  2551.2  144.98
  2729.7   149.5  2892.3   149.4  2952.3     153  3019.4  150.88  3632.3   134.2
  4152.3   136.6  4292.3   131.9  4412.3   134.8  4958.1  129.34  4975.9  127.04
  4978.5  122.01  4983.5  119.87  5013.1  117.13  5028.8  125.02  5052.1  132.67
    5075  134.29  5363.8   134.9  5603.8   143.6  5883.8   145.4  6283.8   142.8
  6443.8   149.7  6703.8   150.2  7083.8   157.7  7363.8   168.6  7658.8     171
#Mann= 5 ,-1 , 0
  1169.7     .18       0  2551.2     .09       0  3019.4     .15       0
  4975.9     .08       0  5028.8     .15       0
Bank Sta=4975.9,5028.8
XS Rating Curve= 0
Exp/Cntr=.3,.1