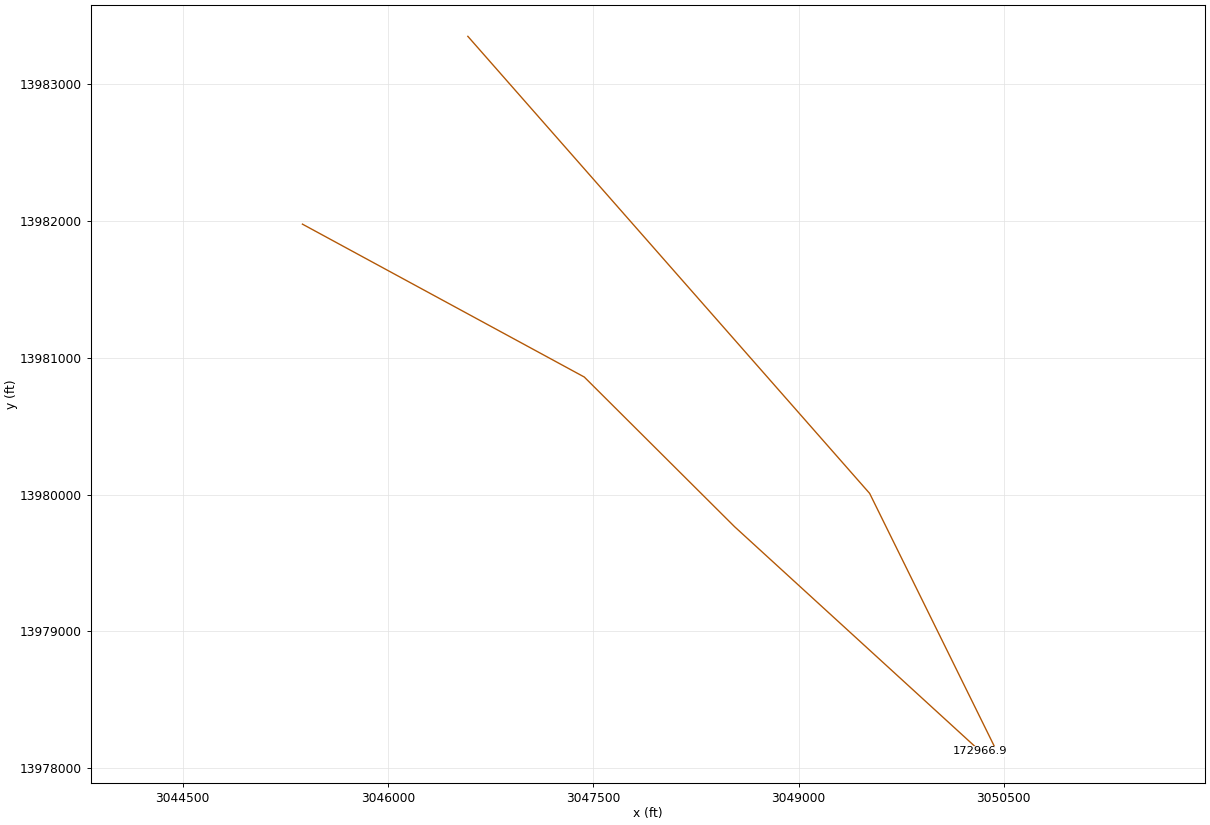
HEC-RAS study J100-00-00.prj: J100-00-00

--- J100-00-00.g01 (geometry) --- (continued)

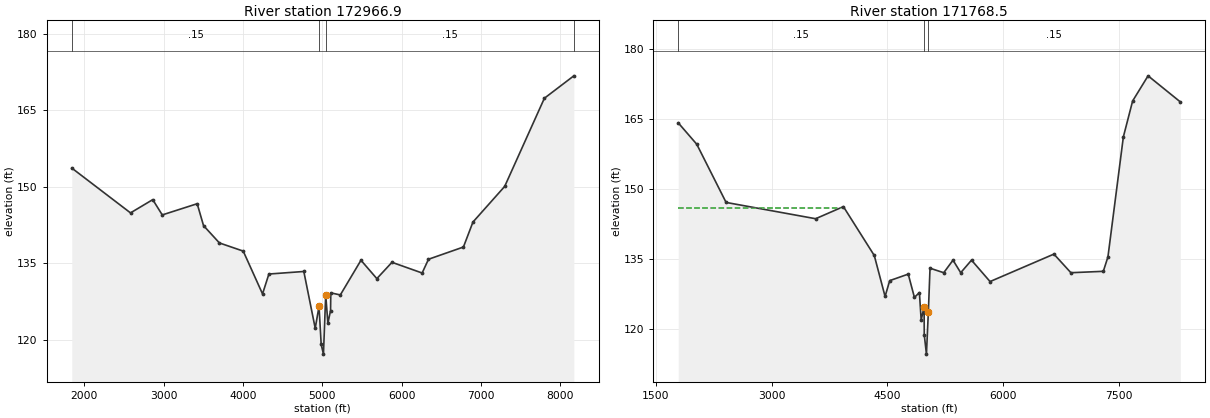
Type RM Length L Ch R = 1 ,172966.9,1011.7,1198.4,909.82
BEGIN DESCRIPTION:
Cross Section XS128
Ineffective at Sta 3400 based on topo upstream of the cross section
END DESCRIPTION:
XS GIS Cut Line= 4
    3045374.5029   13981976.3964    3047434.2688   13980859.0895
    3048533.0801   13979764.8951    3050327.3495   13978124.4201
#Sta/Elev= 30
  1843.7   153.7  2583.7   144.9  2863.7   147.5  2983.7   144.5  3423.7   146.7
  3503.7   142.4  3703.7     139  4003.7   137.4    4247     129    4327   132.9
    4767   133.4  4910.7  122.26  4958.7  126.56  4985.9  119.08  5014.3  117.18
  5042.9  128.84  5070.3  123.24  5103.9  125.73    5107   129.2    5227   128.8
    5487   135.6    5687     132  5877.7   135.2  6257.7   133.1  6337.7   135.8
  6777.7   138.2  6897.7   143.1  7297.7   150.1  7797.7   167.4  8168.8   171.8
#Mann= 4 ,-1 , 0
  1843.7     .15       0  4958.7     .08       0  5042.9     .15       0
  8168.8      .2       0
#XS Ineff= 2 , 0
       0    3400     146               0
Permanent Ineff=
       F       F
Bank Sta=4958.7,5042.9
XS Rating Curve= 0
Exp/Cntr=.3,.1

Type RM Length L Ch R = 1 ,171768.5,1289.05,1400.8,993.26
BEGIN DESCRIPTION:
Cross Section XS127
Ineffective at Sta 3900 based on topo upstream of the cross section
END DESCRIPTION:
XS GIS Cut Line= 3
    3046583.4149   13983348.7923    3049519.9283   13980008.4031
    3050429.8792   13978162.8688
#Sta/Elev= 30
    1789   164.2  2029.1   159.6  2409.1   147.1  3569.1   143.6  3929.1   146.2
  4329.1   135.7  4469.1   126.9  4529.1   130.3  4769.1   131.7  4849.1   126.7
  4913.7  127.73  4936.8  121.85  4974.6  124.63  4976.8  118.68    5005  114.51
    5030  123.66  5051.5  132.97  5229.1     132  5349.1   134.7  5449.1     132
  5589.1   134.7  5829.1   130.1  6656.7     136  6876.7     132  7296.7   132.3
  7356.7   135.4  7556.7   161.2  7676.7   168.9  7876.7   174.3  8294.4   168.7
#Mann= 3 ,-1 , 0
    1789     .15       0  4974.6     .08       0    5030     .15       0
#XS Ineff= 2 , 0
       0    3900     146               0
Permanent Ineff=
       F       F
Bank Sta=4974.6,5030
XS Rating Curve= 0
Exp/Cntr=.3,.1