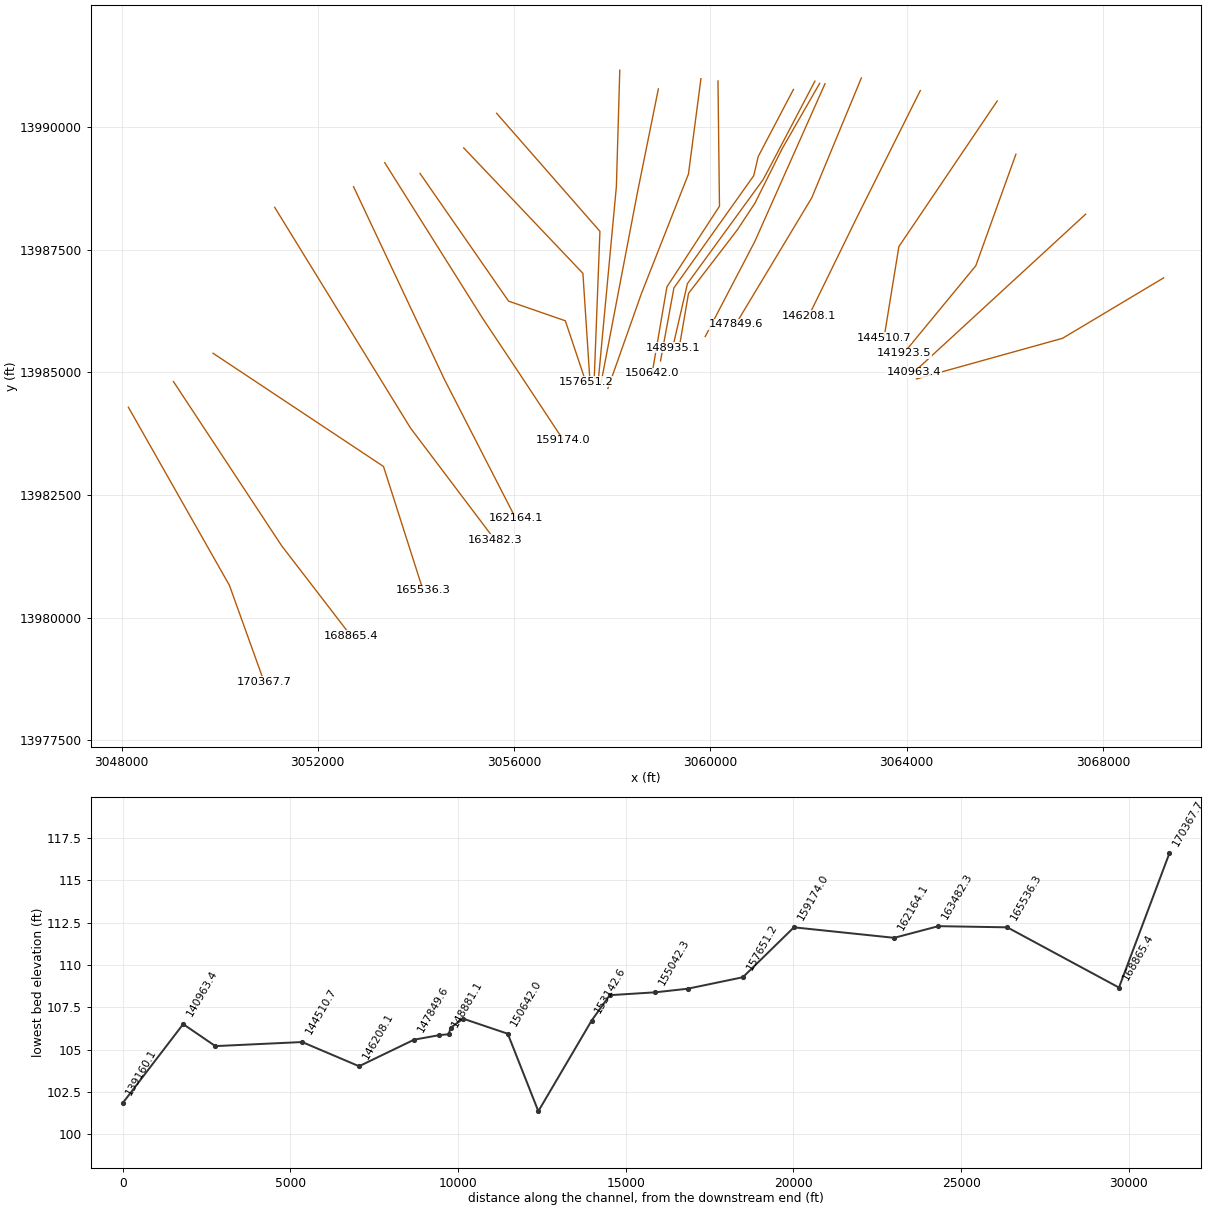
HEC-RAS study J100-00-00.prj: J100-00-00

--- J100-00-00.g01 (geometry) --- (continued)

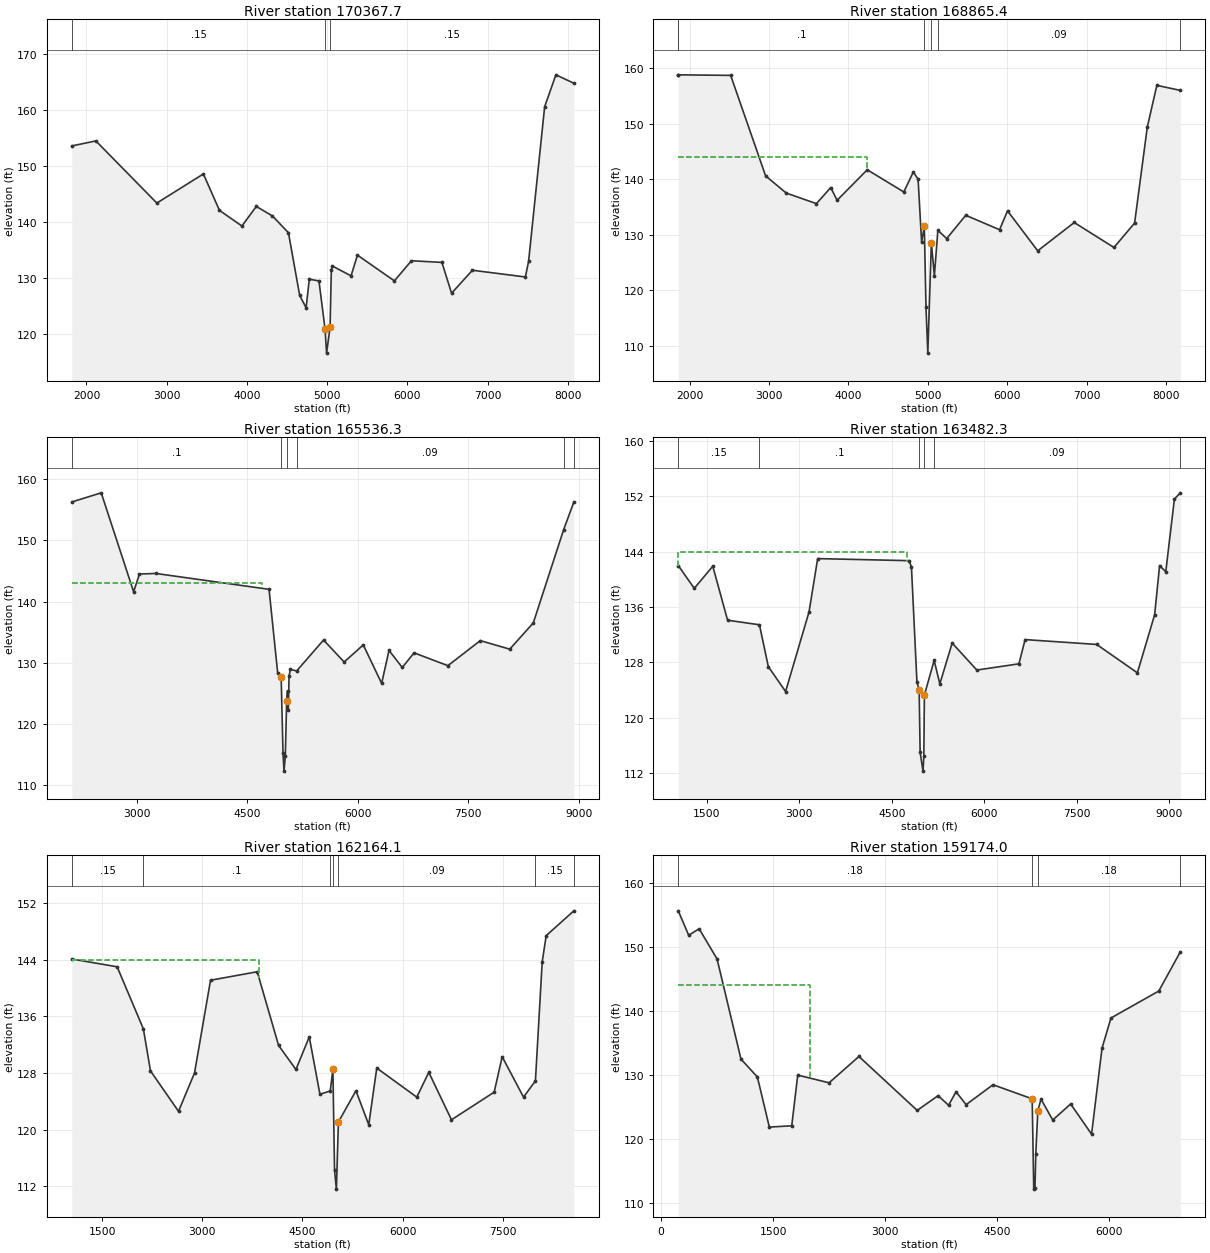
Type RM Length L Ch R = 1 ,170367.7,1252.84,1502.3,1337.97
BEGIN DESCRIPTION:
Cross Section XS126
Ineffective at Sta 3500 based on topo upstream of the cross section
END DESCRIPTION:
XS GIS Cut Line= 3
    3048140.3593   13984291.1534    3050199.1874   13980662.0298
     3050904.079   13978701.1496
#Sta/Elev= 30
  1816.9   153.6  2116.9   154.5  2876.9   143.4  3456.9   148.6  3656.9   142.1
  3936.9   139.3  4116.9   142.8  4316.9   141.1  4516.9   138.1  4656.9   126.9
  4736.9   124.7  4776.9   129.8  4896.9   129.5  4972.9  120.92  4991.8   116.6
  5035.3  121.18  5051.1  131.42  5062.8  132.17  5296.9   130.4  5376.9   134.1
  5836.9   129.5  6049.3   133.1  6429.3   132.8  6549.3   127.3  6809.3   131.4
  7469.3   130.2  7509.3     133  7709.3   160.6  7849.3   166.3  8073.1   164.8
#Mann= 3 ,-1 , 0
  1816.9     .15       0  4972.9     .08       0  5035.3     .15       0
#XS Ineff= 2 , 0
       0    3500     146               0
Permanent Ineff=
       F       F
Bank Sta=4972.9,5035.3
XS Rating Curve= 0
Exp/Cntr=.3,.1

Type RM Length L Ch R = 1 ,168865.4,1806.02,3329.1,2699.45
BEGIN DESCRIPTION:
Cross Section XS125
Ineffective at Sta 4230 based on topo upstream of the cross section
END DESCRIPTION:
XS GIS Cut Line= 3
    3049058.5447   13984814.4819    3051262.9329    13981469.451
    3052674.6186   13979633.9775
#Sta/Elev= 30
    1857   158.8  1857.1   158.8  2517.1   158.7  2957.1   140.6  3217.1   137.5
  3597.1   135.6  3777.1   138.5  3857.1   136.2  4237.1   141.7  4697.1   137.7
  4817.1   141.3  4877.1     140  4921.3  128.69  4955.3  131.51  4976.5  116.94
  4999.4  108.67    5044  128.58    5082  122.61  5126.1   130.8  5237.1   129.3
  5477.1   133.5  5903.2   130.9  6003.2   134.3  6383.2   127.1  6843.2   132.2
  7343.2   127.7  7603.2   132.1  7763.2   149.4  7883.2   156.9  8178.7     156
#Mann= 6 ,-1 , 0
    1857      .2       0  1857.1      .1       0  4955.3     .08       0
    5044      .1       0  5126.1     .09       0  8178.7      .2       0
#XS Ineff= 2 , 0
       0    4230     144               0
Permanent Ineff=
       F       F
Bank Sta=4955.3,5044
XS Rating Curve= 0
Exp/Cntr=.3,.1

Type RM Length L Ch R = 1 ,165536.3,1909.16,2054,927.1
BEGIN DESCRIPTION:
Cross Section XS124
Ineffective at Sta 4700 based on ineffective flow line
END DESCRIPTION:
XS GIS Cut Line= 3
    3049865.9659   13985391.2114     3053339.159   13983084.2935
    3054146.5802   13980559.5001
#Sta/Elev= 30
  2114.4   156.3  2514.4   157.8  2954.4   141.6  3034.4   144.5  3254.4   144.6
  4794.4     142  4911.7  128.31  4958.9   127.6 4983.91  115.21  4997.4  112.23
  5015.3  114.68  5033.3  123.64  5045.1  125.38  5055.5  122.17  5066.1  127.81
  5084.1   128.9  5169.5  128.63  5534.4   133.7  5814.4   130.1  6074.4   132.9
  6323.9   126.6  6423.9     132  6603.9   129.2  6763.9   131.6  7223.9   129.5
  7663.9   133.6  8063.9   132.2  8383.9   136.5  8795.9  151.76  8934.7   156.3
#Mann= 6 ,-1 , 0
  2114.4      .1       0  4958.9     .08       0  5033.3      .1       0
  5169.5     .09       0  8795.9     .15       0  8934.7      .2       0
#XS Ineff= 2 , 0
       0    4700     143               0
Permanent Ineff=
       F       F
Bank Sta=4958.9,5033.3
XS Rating Curve= 0
Exp/Cntr=.3,.1

Type RM Length L Ch R = 1 ,163482.3,1288.59,1318.2,1040.95
BEGIN DESCRIPTION:
Cross Section XS123
Ineffective at Sta 4750 based on ineffective flow line
END DESCRIPTION:
XS GIS Cut Line= 3
    3051121.9546   13988364.5722     3053890.256   13983866.0824
    3055610.9612   13981586.9867
#Sta/Elev= 30
  1038.7     142  1298.7   138.7  1598.7   141.9  1838.7   134.1    2355  133.44
  2498.7   127.4  2778.7   123.8  3158.7   135.3  3298.7     143  4778.7   142.7
  4818.7   141.8  4907.4  125.22  4943.7  123.98  4959.4  115.03  5006.3   112.3
  5019.7   114.5  5028.4  123.28  5186.6   128.3  5278.7   124.9  5478.7   130.8
  5878.7   126.9  6560.7   127.8  6660.7   131.3  7820.7   130.6  8480.7   126.5
  8760.7   134.9  8840.7     142  8940.7   141.1  9080.7   151.6  9176.5   152.5
#Mann= 6 ,-1 , 0
  1038.7     .15       0    2355      .1       0  4943.7     .08       0
  5028.4      .1       0  5186.6     .09       0  9176.5      .2       0
#XS Ineff= 2 , 0
       0    4750     144               0
Permanent Ineff=
       F       F
Bank Sta=4943.7,5028.4
XS Rating Curve= 0
Exp/Cntr=.3,.1

Type RM Length L Ch R = 1 ,162164.1,1145.45,2990.1,1441.23
BEGIN DESCRIPTION:
Cross Section XS122
Ineffective at Sta 3850 based on ineffective flow line
END DESCRIPTION:
XS GIS Cut Line= 3
    3052729.2482   13988784.4404    3054585.5318    13984848.444
    3056034.3408   13982024.0237
#Sta/Elev= 30
  1041.6   144.1  1721.6     143    2115  134.23  2221.6   128.3  2641.6   122.6
  2881.6     128  3121.6   141.1  3821.6   142.3  4141.6   131.9  4401.6   128.5
  4601.6   133.1  4761.6     125  4916.3  125.47    4956  128.52  4980.4  114.27
  5008.4  111.61  5038.5  121.09  5301.6   125.5  5493.4   120.7  5613.4   128.7
  6213.4   124.6  6393.4   128.1  6733.4   121.4  7373.4   125.3  7493.4   130.3
  7813.4   124.6  7991.7  126.89  8093.4   143.7  8153.4   147.4  8567.7   150.9
#Mann= 7 ,-1 , 0
  1041.6     .15       0    2115      .1       0  4916.3     .09       0
    4956     .08       0  5038.5     .09       0  7991.7     .15       0
  8567.7      .2       0
#XS Ineff= 2 , 0
       0    3850     144               0
Permanent Ineff=
       F       F
Bank Sta=4956,5038.5
XS Rating Curve= 0
Exp/Cntr=.3,.1

Type RM Length L Ch R = 1 ,159174.0,606.18,1522.8,1439.14
BEGIN DESCRIPTION:
Cross Section XS121
Ineffective at Sta 2000 based on ineffective flow line
END DESCRIPTION:
XS GIS Cut Line= 4
    3053364.7914   13989274.5232    3055364.1202    13986096.103
    3056107.4604   13984981.0927    3057004.0167   13983621.9404
#Sta/Elev= 30
   230.6   155.6   370.6   151.8   510.6   152.8   750.6   148.1  1070.6   132.5
  1290.6   129.7  1450.6   121.9  1750.6   122.1  1830.6     130  2250.6   128.8
  2650.6   132.9  3430.6   124.5  3710.6   126.8  3850.6   125.3  3950.6   127.4
  4085.6   125.4  4445.6   128.5  4970.3   126.3  4991.2  112.23  5007.3  112.33
  5018.8  117.76  5045.8  124.41  5088.2  126.26  5245.6     123  5485.6   125.5
  5765.6   120.8  5905.6   134.2  6025.6   138.9  6665.6   143.1  6953.9   149.2
#Mann= 4 ,-1 , 0
   230.6     .18       0  4970.3     .07       0  5045.8     .18       0
  6953.9      .2       0
#XS Ineff= 2 , 0
       0    2000     144               0
Permanent Ineff=
       F       F
Bank Sta=4970.3,5045.8
XS Rating Curve= 0
Exp/Cntr=.3,.1

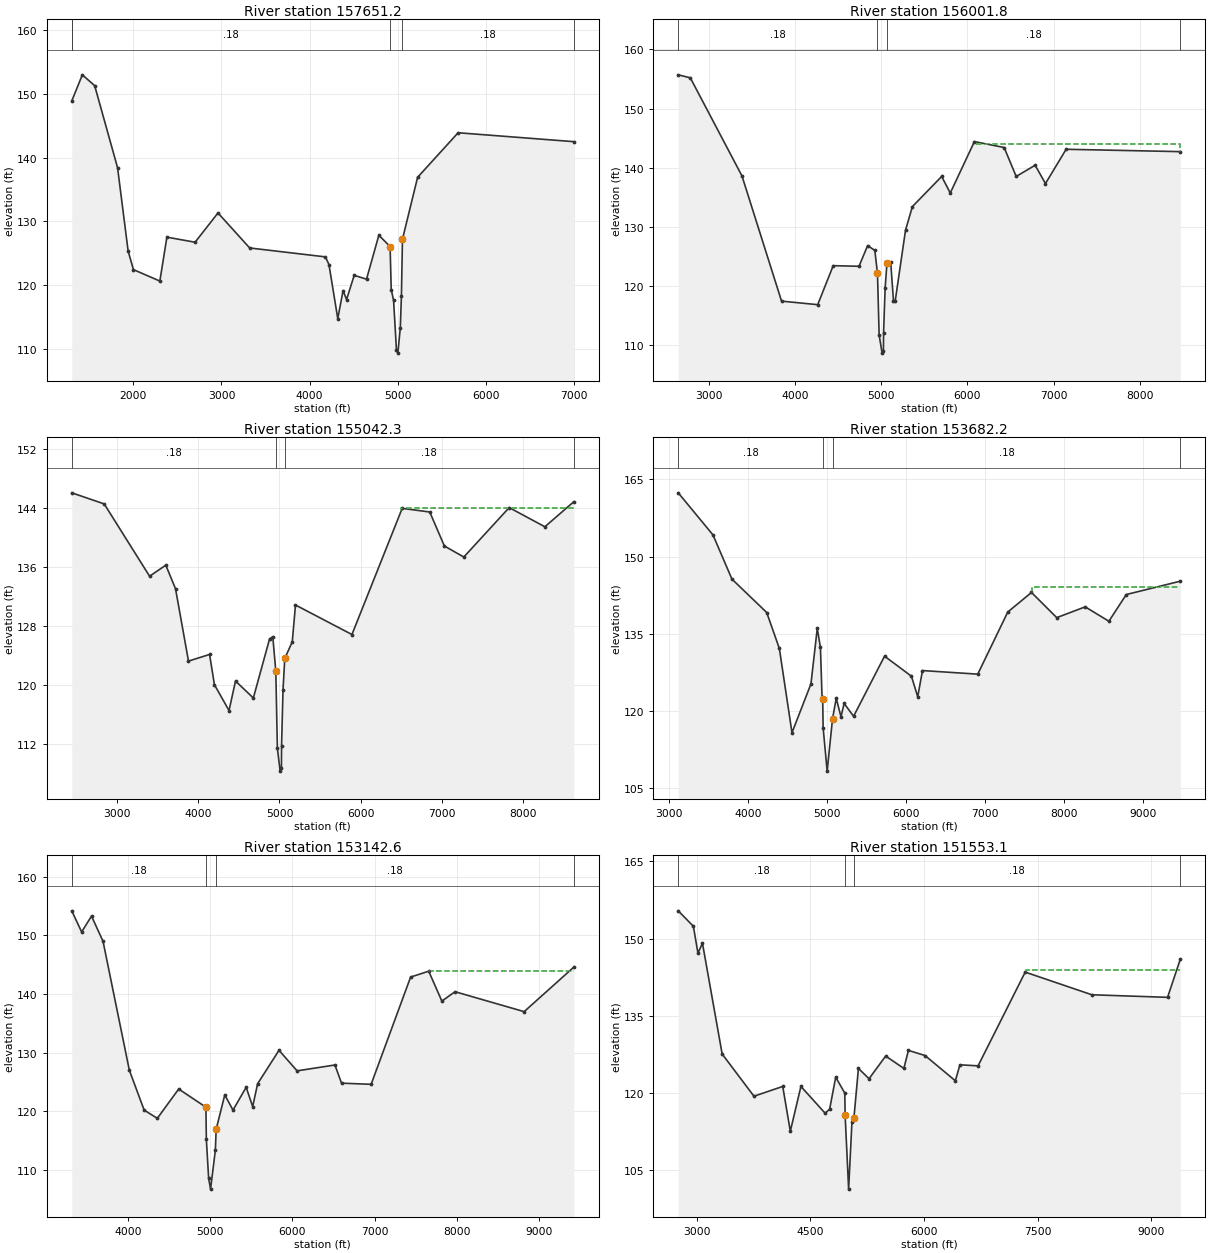
Type RM Length L Ch R = 1 ,157651.2,1377.08,1649.4,1349.87
BEGIN DESCRIPTION:
Cross Section XS120
END DESCRIPTION:
XS GIS Cut Line= 4
    3054083.7315   13989055.7376    3055887.8596   13986453.6298
     3057044.989   13986052.9589    3057460.6892   13984811.4106
#Sta/Elev= 30
  1300.2   148.9  1420.2     153  1560.2   151.3  1820.2   138.4  1940.2   125.3
  2000.2   122.4  2300.2   120.6  2380.2   127.5  2700.2   126.7  2960.2   131.3
  3320.2   125.8  4180.2   124.4  4220.2   123.2  4320.2   114.7  4380.2   119.1
  4420.2   117.7  4506.6   121.5  4646.6   120.9  4786.6   127.8  4914.3  126.02
  4927.1  119.27  4953.9  117.55  4986.4  109.79  5002.5  109.28  5030.3  113.27
  5042.6  118.19  5054.6  127.17  5226.6   136.9  5686.6   143.9  7000.4   142.5
#Mann= 5 , 1 , 0
  1300.2      .2       0  1300.2     .18       0  4914.3     .07       0
  5054.6     .18       0  7000.4      .2       0
Bank Sta=4914.3,5054.6
XS Rating Curve= 0
Exp/Cntr=.3,.1

Type RM Length L Ch R = 1 ,156001.8,898.69,959.5,763.89
BEGIN DESCRIPTION:
Cross Section XS119
Ineffective at Sta 6100 based on topo downstream of the cross section
END DESCRIPTION:
XS GIS Cut Line= 3
    3054974.2306   13989576.1591    3057402.8646    13987020.311
    3057553.2086   13984718.8912
#Sta/Elev= 30
  2640.8   155.7  2780.8   155.2  3380.8   138.6  3840.8   117.4  4260.8   116.8
  4440.8   123.4  4740.8   123.3  4840.8   126.8  4924.3  125.98  4955.1  122.13
  4974.4  111.69  5008.8   108.6  5024.3  109.01  5025.8  111.97  5043.8  119.57
  5065.7  123.88  5108.7     124  5140.8   117.5  5160.8   117.4  5280.8   129.4
  5360.8   133.4  5700.8   138.5  5800.8   135.7  6080.8   144.4  6426.5   143.4
  6566.5   138.5  6786.5   140.4  6906.5   137.3  7146.5   143.1  8472.8   142.7
#Mann= 4 ,-1 , 0
  2640.8     .18       0  4955.1     .07       0  5065.7     .18       0
  8472.8      .2       0
#XS Ineff= 2 , 0
       0                    6100       0     144
Permanent Ineff=
       F       F
Bank Sta=4955.1,5065.7
XS Rating Curve= 0
Exp/Cntr=.3,.1

Type RM Length L Ch R = 1 ,155042.3,1559.11,1360.1,263.61
BEGIN DESCRIPTION:
Cross Section XS118
Ineffective at Sta 6500 based on topo upstream of the cross section
END DESCRIPTION:
XS GIS Cut Line= 3
    3055644.9962   13990281.6195    3057749.8123   13987876.1154
     3057634.163   13984880.8002
#Sta/Elev= 30
  2437.9   146.1  2837.9   144.6  3397.9   134.8  3597.9   136.3  3717.9   133.1
  3877.9   123.3  4137.9   124.2  4197.9   120.1  4377.9   116.6  4457.9   120.6
  4677.9   118.3  4877.9   126.3  4917.9   126.6  4955.1  121.92  4974.4  111.48
  5008.8  108.39  5024.3   108.8  5025.8  111.76  5043.8  119.36  5065.7  123.67
  5157.9   125.9  5197.9   130.9  5894.3   126.9  6514.3     144  6854.3   143.5
  7034.3   138.9  7274.3   137.4  7834.3   144.1  8274.3   141.5  8631.8   144.9
#Mann= 4 ,-1 , 0
  2437.9     .18       0  4955.1     .07       0  5065.7     .18       0
  8631.8      .2       0
#XS Ineff= 2 , 0
       0                    6500       0     144
Permanent Ineff=
       F       F
Bank Sta=4955.1,5065.7
XS Rating Curve= 0
Exp/Cntr=.3,.1

Type RM Length L Ch R = 1 ,153682.2,610.27,539.6,349.21
BEGIN DESCRIPTION:
Cross Section XS117
Ineffective at Sta 7600 based on topo upstream of the cross section
END DESCRIPTION:
XS GIS Cut Line= 3
    3058154.5846   13991160.5537    3058085.1951   13988789.7443
    3057715.1175   13984822.9755
#Sta/Elev= 30
  3119.1   162.4  3559.1   154.2  3799.1   145.6  4239.1   139.1  4399.1   132.1
  4559.1   115.7  4799.1   125.2  4879.1     136  4919.1   132.3  4939.5  122.71
  4947.9   122.2  4953.3  116.69  5004.3  108.22  5072.4  118.42  5119.1   122.4
  5179.1   118.8  5219.1   121.4  5339.1   118.9  5730.9   130.6  6070.9   126.7
  6150.9   122.7  6210.9   127.8  6910.9   127.1  7290.9   139.2  7590.9     143
  7910.9   138.1  8270.9   140.2  8570.9   137.4  8790.9   142.6  9474.9   145.2
#Mann= 4 ,-1 , 0
  3119.1     .18       0  4947.9     .07       0  5072.4     .18       0
  9474.9      .2       0
#XS Ineff= 2 , 0
       0                    7600       0     144
Permanent Ineff=
       F       F
Bank Sta=4947.9,5072.4
XS Rating Curve= 0
Exp/Cntr=.3,.1

Type RM Length L Ch R = 1 ,153142.6,917.63,1589.5,665.22
BEGIN DESCRIPTION:
Cross Section XS116
Ineffective at Sta 7650 based on topo upstream of the cross section
END DESCRIPTION:
XS GIS Cut Line= 3
    3058940.9994   13990778.9112    3058513.0972   13988662.5302
    3057772.9421   13984788.2808
#Sta/Elev= 30
  3317.1   154.2  3437.1   150.6  3557.1   153.3  3697.1     149  4017.1     127
  4197.1   120.2  4357.1   118.8  4617.1   123.8  4947.9   120.7  4953.3  115.19
  4981.2  108.55  5004.3  106.72  5062.7  113.39  5072.4  116.92  5177.1   122.8
  5277.1   120.2  5437.1   124.1  5516.3   120.8  5576.3   124.7  5836.3   130.4
  6056.3   126.9  6516.3   127.9  6596.3   124.8  6956.3   124.6  7436.3   142.9
  7656.3   143.9  7816.3   138.8  7976.3   140.4  8816.3     137  9420.6   144.6
#Mann= 4 ,-1 , 0
  3317.1     .18       0  4947.9     .07       0  5072.4     .18       0
  9420.6      .2       0
#XS Ineff= 2 , 0
       0                    7650       0     144
Permanent Ineff=
       F       F
Bank Sta=4947.9,5072.4
XS Rating Curve= 0
Exp/Cntr=.3,.1

Type RM Length L Ch R = 1 ,151553.1,557.2,911.1,1266.52
BEGIN DESCRIPTION:
Cross Section XS115
Ineffective at Sta 7350 based on topo upstream of the cross section
END DESCRIPTION:
XS GIS Cut Line= 4
    3059808.3687   13990987.0798    3059553.9403   13989044.1726
    3058594.0517   13986603.9738    3057911.7212   13984672.6315
#Sta/Elev= 30
  2753.5   155.4  2953.5   152.4  3013.5   147.2  3073.5   149.1  3333.5   127.6
  3753.5   119.4  4133.5   121.3  4233.5   112.6  4373.5   121.3  4693.5   116.1
    4753   116.9    4833   123.1    4953     120  4957.5  115.69  5003.6  101.36
  5047.6  114.43  5073.1  115.13    5133   124.8    5273   122.8    5493   127.2
    5733   124.8    5793   128.3    6013   127.3    6413   122.4    6473   125.5
    6713   125.3  7335.2   143.5  8215.2   139.1  9215.2   138.6  9383.5     146
#Mann= 4 ,-1 , 0
  2753.5     .18       0  4957.5     .07       0  5073.1     .18       0
  9383.5      .2       0
#XS Ineff= 2 , 0
       0                    7350       0     144
Permanent Ineff=
       F       F
Bank Sta=4957.5,5073.1
XS Rating Curve= 0
Exp/Cntr=.3,.1

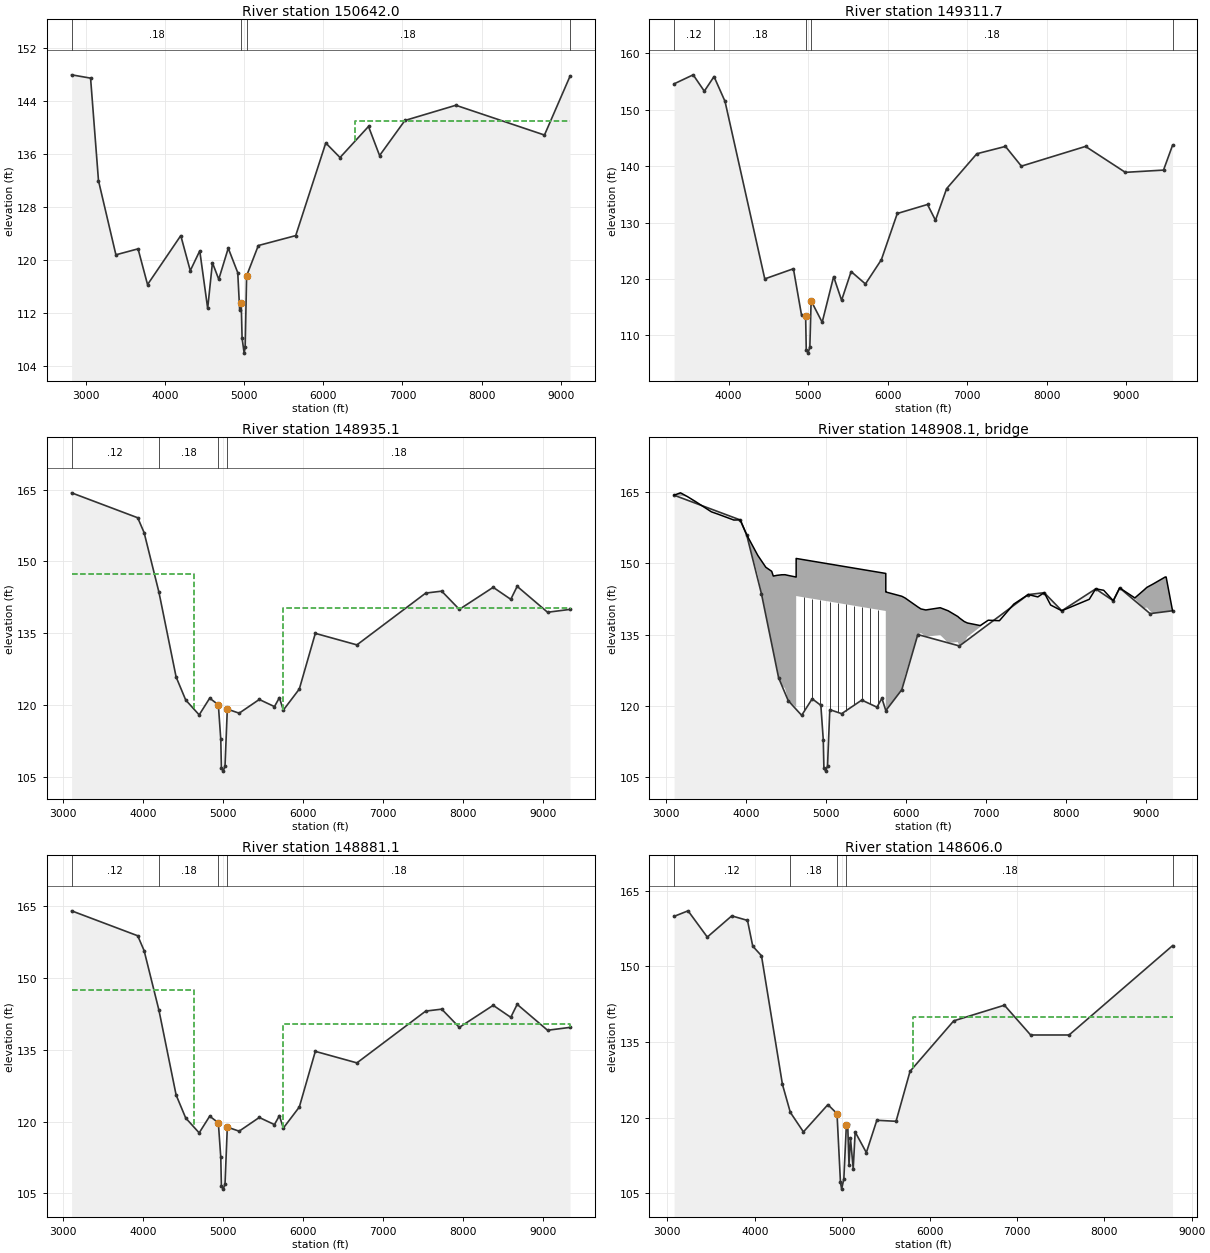
Type RM Length L Ch R = 1 ,150642.0,987.25,1330.3,406.44
BEGIN DESCRIPTION:
Cross Section XS114
Ineffective at Sta 6400 based on topo downstream of the cross section
END DESCRIPTION:
XS GIS Cut Line= 4
    3060155.3164   13990940.8201    3060186.1927   13988388.3756
    3059114.4733   13986742.7528    3058813.7852   13984984.8845
#Sta/Elev= 30
  2818.9     148  3058.9   147.5  3158.9     132  3378.9   120.8  3658.9   121.7
  3778.9   116.3  4198.9   123.7  4318.9   118.4  4438.9   121.4  4538.9   112.7
  4598.9   119.6  4678.9   117.1  4798.9   121.8  4918.9   118.1  4943.5  112.39
  4962.8  113.46  4973.8   108.2  4999.8  105.94  5012.5   106.8    5031  117.62
  5178.9   122.2  5651.5   123.7  6031.5   137.7  6211.5   135.5  6571.5   140.2
  6711.5   135.8  7031.5   141.1  7675.4   143.4  8795.4   138.9  9118.8   147.8
#Mann= 4 ,-1 , 0
  2818.9     .18       0  4962.8     .07       0    5031     .18       0
  9118.8      .2       0
#XS Ineff= 2 , 0
       0                    6400       0     141
Permanent Ineff=
       F       F
Bank Sta=4962.8,5031
XS Rating Curve= 0
Exp/Cntr=.3,.1

Type RM Length L Ch R = 1 ,149311.7,239.2,376.6,186.34
BEGIN DESCRIPTION:
Cross Section XS113-Bridge 5 -Con
END DESCRIPTION:
XS GIS Cut Line= 5
    3061693.4512   13990767.3463     3060976.426   13989402.6853
    3060883.9066   13989009.4779     3059257.489   13986722.1719
    3058984.3408   13985233.5145
#Sta/Elev= 30
  3315.1   154.6  3555.1   156.2  3695.1   153.3  3817.1  155.89  3955.1   151.5
  4455.1     120  4815.1   121.8  4916.7   113.6  4968.6  113.45  4976.5  107.43
  4999.8  106.83  5021.7  107.94  5037.7  116.11  5176.7   112.3  5320.6   120.4
  5420.6   116.2  5540.6   121.3  5720.6   119.1  5920.6   123.4  6120.6   131.6
  6500.6   133.2  6600.6   130.4  6740.6     136  7120.6   142.2  7480.6   143.5
  7680.6     140  8487.2   143.5  8987.2   138.9  9467.2   139.3  9580.7   143.7
#Mann= 5 ,-1 , 0
  3315.1     .12       0  3817.1     .18       0  4968.6     .07       0
  5037.7     .18       0  9580.7      .2       0
Bank Sta=4968.6,5037.7
XS Rating Curve= 0
Exp/Cntr=.5,.3

Type RM Length L Ch R = 1 ,148935.1,54,54,54
BEGIN DESCRIPTION:
Upstream Section of Kuykendahl
END DESCRIPTION:
XS GIS Cut Line= 5
    3062131.0774   13990936.9429    3061249.5797   13989256.7623
    3061075.0484   13988929.2144     3059532.957   13986810.6067
     3059232.269   13985503.7703
#Sta/Elev= 30
  3103.8  164.31  3930.4  159.11  4010.4  156.01  4195.9  143.57  4410.4  125.91
  4530.4  121.11  4698.5  118.02  4830.1   121.5  4938.2  120.12  4968.6  112.91
  4976.5  106.89  4999.8  106.29  5021.7   107.4  5050.2  119.22  5198.3  118.37
  5449.9  121.23  5639.5  119.74  5701.3  121.61  5750.3  119.01  5950.3  123.41
  6150.3  135.01  6670.3  132.61  7530.3  143.41  7730.3  143.81  7950.3  140.01
  8373.4  144.61  8593.4  142.11  8673.4  144.81  9053.4  139.41  9334.3  140.01
#Mann= 4 ,-1 , 0
  3103.8     .12       0  4195.9     .18       0  4938.2     .07       0
  5050.2     .18       0
#XS Ineff= 2 , 0
       0    4629   147.4    5750       0   140.3
Permanent Ineff=
       F       F
#Block Obstruct= 2 , 0
       0                    6512       0   140.3
Bank Sta=4938.2,5050.2
XS Rating Curve= 0
Exp/Cntr=.5,.3

Type RM Length L Ch R = 3 ,148908.1,,,
BEGIN DESCRIPTION:
KUYKENDAHL
Structure ID: J100-00-00-05
Square nose piers
END DESCRIPTION:
Node Name=Kuykendahl
Bridge Culvert--1,0,-1,-1, 0
Deck Dist Width WeirC Skew NumUp NumDn MinLoCord MaxHiCord MaxSubmerge Is_Ogee
10,34,2.6,0, 60, 60, , , .95, 0, 1,1,,
  3103.8  3183.8  3270.4  3370.4  3570.4  3650.4  3850.4  3930.4  4010.4  4150.4
  4250.4  4323.8  4343.8  4390.4  4410.4  4450.4  4490.4  4530.4 4629.49  4629.6
 4629.81  4629.9    4630 5749.79 5749.89    5750  5750.1 5750.21  5950.3  5990.3
  6150.3  6190.3  6250.3  6430.3  6530.3  6650.3  6670.3  6730.3  6770.3  6930.3
  7030.3  7170.3  7350.3  7530.3  7650.3  7730.3  7810.3  7949.6  8293.4  8373.4
  8473.4  8593.4  8673.4  8862.7  8973.4  9013.4  9093.4  9242.7  9254.1  9334.3
   164.3   164.8  164.01  162.98   160.8  160.33  159.08  159.11  156.01  151.64
  149.15   148.3   147.3  147.45  147.49  147.57  147.58  147.43  147.09  150.99
     151     151     151  147.85  147.85  147.85  143.95  143.95  143.05   142.7
  140.81  140.38  140.17  140.64  139.99  138.79  138.49  137.74  137.43  136.89
  138.01  137.91  141.41  143.41  142.91  143.81  141.21     140  142.41  144.61
  144.31  142.11  144.81   142.7  144.31  144.92  145.65   147.1   147.1     140
   164.3  164.16     164   161.4   159.9   160.3   158.8   159.1     156   147.5
   139.5  132.53  130.93   128.1   125.9   124.1   123.7   121.1  119.74  119.73
  119.72  119.72   143.1  139.95  119.02  119.02  119.01     119   123.4   126.4
     135   135.3   134.1   134.9   132.1   133.4   132.6     133   134.5   136.6
     138   137.9   141.4   143.4   142.9   143.8   141.2     140   142.4   144.6
   144.3   142.1   144.8  142.51     140   140.7   139.2  139.63  139.66     140
  3103.8  3183.8  3270.4  3370.4  3570.4  3650.4  3850.4  3930.4  4010.4  4150.4
  4250.4  4323.8  4343.8  4390.4  4410.4  4450.4  4490.4  4530.4 4629.49  4629.6
 4629.81  4629.9    4630 5749.79 5749.89    5750  5750.1 5750.21  5950.3  5990.3
  6150.3  6190.3  6250.3  6430.3  6530.3  6650.3  6670.3  6730.3  6770.3  6930.3
  7030.3  7170.3  7350.3  7530.3  7650.3  7730.3  7810.3  7949.6  8293.4  8373.4
  8473.4  8593.4  8673.4  8862.7  8973.4  9013.4  9093.4  9242.7  9254.1  9334.3
   164.3   164.8  164.01  162.98   160.8  160.33  159.08  159.11  156.01  151.64
  149.15   148.3   147.3  147.45  147.49  147.57  147.58  147.43  147.09  150.99
     151     151     151  147.85  147.85  147.85  143.95  143.95  143.05   142.7
  140.81  140.38  140.17  140.64  139.99  138.79  138.49  137.74  137.43  136.89
  138.01  137.91  141.41  143.41  142.91  143.81  141.21     140  142.41  144.61
  144.31  142.11  144.81   142.7  144.31  144.92  145.65   147.1   147.1     140
  163.93  163.79  163.63  161.03  159.53  159.93  158.43  158.73  155.63  147.13
  139.13  132.16  130.56  127.73  125.53  123.73  123.33  120.73  119.37  119.36
  119.35  119.35  142.73  139.58  118.65  118.65  118.64  118.63  123.03  126.03
  134.63  134.93  133.73  134.53  131.73  133.03  132.23  132.63  134.13  136.23
  137.63  137.53  141.03  143.03  142.53  143.43  140.83  139.63  142.03  144.23
  143.93  141.73  144.43  142.14  139.63  140.33  138.83  139.26  139.29  139.63
Pier Skew, UpSta & Num, DnSta & Num=  ,4730, 2 ,4730, 2 , 0 , 0 , 0 ,,
     1.6     1.6
  118.46  144.02
     1.6     1.6
  118.09  143.65
Pier Skew, UpSta & Num, DnSta & Num=  ,4830.3, 2 ,4830.3, 2 , 0 , 0 , 0 ,,
     1.6     1.6
  120.48   143.9
     1.6     1.6
  120.11  143.53
Pier Skew, UpSta & Num, DnSta & Num=  ,4930.7, 2 ,4930.7, 2 , 0 , 0 , 0 ,,
     1.6     1.6
  119.44  143.52
     1.6     1.6
  119.07  143.15
Pier Skew, UpSta & Num, DnSta & Num=  ,5050.3, 2 ,5050.3, 2 , 0 , 0 , 0 ,,
     1.6     1.6
  118.01  143.17
     1.6     1.6
  117.64   142.8
Pier Skew, UpSta & Num, DnSta & Num=  ,5149.9, 2 ,5149.9, 2 , 0 , 0 , 0 ,,
     1.6     1.6
  117.36  142.76
     1.6     1.6
  116.99  142.39
Pier Skew, UpSta & Num, DnSta & Num=  ,5250, 2 ,5250, 2 , 0 , 0 , 0 ,,
     1.6     1.6
  118.07  142.49
     1.6     1.6
   117.7  142.12
Pier Skew, UpSta & Num, DnSta & Num=  ,5350, 2 ,5350, 2 , 0 , 0 , 0 ,,
     1.6     1.6
  119.07  142.26
     1.6     1.6
   118.7  141.89
Pier Skew, UpSta & Num, DnSta & Num=  ,5449.9, 2 ,5449.9, 2 , 0 , 0 , 0 ,,
     1.6     1.6
  120.21  141.96
     1.6     1.6
  119.84  141.59
Pier Skew, UpSta & Num, DnSta & Num=  ,5550.1, 2 ,5550.1, 2 , 0 , 0 , 0 ,,
     1.6     1.6
  119.59  141.61
     1.6     1.6
  119.22  141.24
Pier Skew, UpSta & Num, DnSta & Num=  ,5650.3, 2 ,5650.3, 2 , 0 , 0 , 0 ,,
     1.6     1.6
  119.26  141.31
     1.6     1.6
  118.89  140.94
BR Coef= 1 , 1 , 1 ,1.25, 0 ,,,.8,0,2,0,
WSPro=,,,, 1 ,,,, 0 ,,,, 0 ,,,,-1 ,-1 ,-1 , 0 , 0 , 0 , 0 , 0
BR U #Sta/Elev= 30
  3103.8   164.3  3930.4   159.1  4010.4     156  4195.9  143.56  4410.4   125.9
  4530.4   121.1  4698.5  118.01  4830.1  121.49  4938.2  120.11  4968.6   112.9
  4976.5  106.88  4999.8  106.28  5021.7  107.39  5050.2  119.21  5198.3  118.36
  5449.9  121.22  5639.5  119.73  5701.3   121.6  5750.3     119  5950.3   123.4
  6150.3     135  6670.3   132.6  7530.3   143.4  7730.3   143.8  7950.3     140
  8373.4   144.6  8593.4   142.1  8673.4   144.8  9053.4   139.4  9334.3     140
BR U #Mann= 4
  3103.8     .12  4195.9     .18  4938.2    .065  5050.2     .18
BR U Banks=4938.2,5050.2
BR D #Sta/Elev= 30
  3103.8  163.93  3930.4  158.73  4010.4  155.63  4195.9  143.19  4410.4  125.53
  4530.4  120.73  4698.5  117.64  4830.1  121.12  4938.2  119.74  4968.6  112.53
  4976.5  106.51  4999.8  105.91  5021.7  107.02  5050.2  118.84  5198.3  117.99
  5449.9  120.85  5639.5  119.36  5701.3  121.23  5750.3  118.63  5950.3  123.03
  6150.3  134.63  6670.3  132.23  7530.3  143.03  7730.3  143.43  7950.3  139.63
  8373.4  144.23  8593.4  141.73  8673.4  144.43  9053.4  139.03  9334.3  139.63
BR D #Mann= 4
  3103.8     .12  4195.9     .18  4938.2    .065  5050.2     .18
BR D Banks=4938.2,5050.2
BC Design=,, 0 ,, 0 ,,,,,,
BC HTab HWMax=164.31

Type RM Length L Ch R = 1 ,148881.1,275.1,275.1,275.1
BEGIN DESCRIPTION:
Downstream Section of Kuykendahl
END DESCRIPTION:
XS GIS Cut Line= 6
    3062226.9324   13990890.3654    3061463.6474   13989560.3992
    3060908.5311   13988450.1665    3060550.0185   13987906.6151
     3059555.435   13986611.3437    3059356.8321   13985456.9641
#Sta/Elev= 30
  3103.8  163.93  3930.4  158.73  4010.4  155.63  4195.9  143.19  4410.4  125.53
  4530.4  120.73  4698.5  117.64  4830.1  121.12  4938.2  119.74  4968.6  112.53
  4976.5  106.51  4999.8  105.91  5021.7  107.02  5050.2  118.84  5198.3  117.99
  5449.9  120.85  5639.5  119.36  5701.3  121.23  5750.3  118.63  5950.3  123.03
  6150.3  134.63  6670.3  132.23  7530.3  143.03  7730.3  143.43  7950.3  139.63
  8373.4  144.23  8593.4  141.73  8673.4  144.43  9053.4  139.03  9334.3  139.63
#Mann= 4 ,-1 , 0
  3103.8     .12       0  4195.9     .18       0  4938.2     .07       0
  5050.2     .18       0
#XS Ineff= 2 , 0
       0    4629   147.4    5750       0   140.3
Permanent Ineff=
       F       F
#Block Obstruct= 2 , 0
       0                    6600       0   140.3
Bank Sta=4938.2,5050.2
XS Rating Curve= 0
Exp/Cntr=.5,.3

Type RM Length L Ch R = 1 ,148606.0,701.81,756.4,627.65
BEGIN DESCRIPTION:
Cross Section XS112-Bridge 5-Exp
Ineffective at Sta 6800 based on topo upstream of the cross section
END DESCRIPTION:
XS GIS Cut Line= 3
    3062336.9329   13990884.3756    3060905.8082    13987668.554
    3059895.6024   13985732.3263
#Sta/Elev= 30
  3076.8   159.9  3236.8     161  3456.8   155.8  3736.8     160  3916.8   159.1
  3976.8     154  4076.8   152.1  4316.8   126.6  4406.9  121.07  4556.8   117.2
  4836.8   122.6  4941.2  120.82  4980.8  107.19    4994  105.86  5019.2  107.87
  5048.2  118.56    5063  118.85  5078.5  110.69  5095.1  115.96  5126.5  109.91
  5148.9  117.18  5276.8   113.1  5396.8   119.5  5616.8   119.3  5776.8   129.2
  6276.8   139.2  6856.7   142.3  7156.7   136.4  7596.7   136.4  8780.6   154.1
#Mann= 5 ,-1 , 0
  3076.8     .12       0  4406.9     .18       0  4941.2     .07       0
  5048.2     .18       0  8780.6      .2       0
#XS Ineff= 2 , 0
       0                    5814       0     140
Permanent Ineff=
       F       F
Bank Sta=4941.2,5048.2
XS Rating Curve= 0
Exp/Cntr=.3,.1

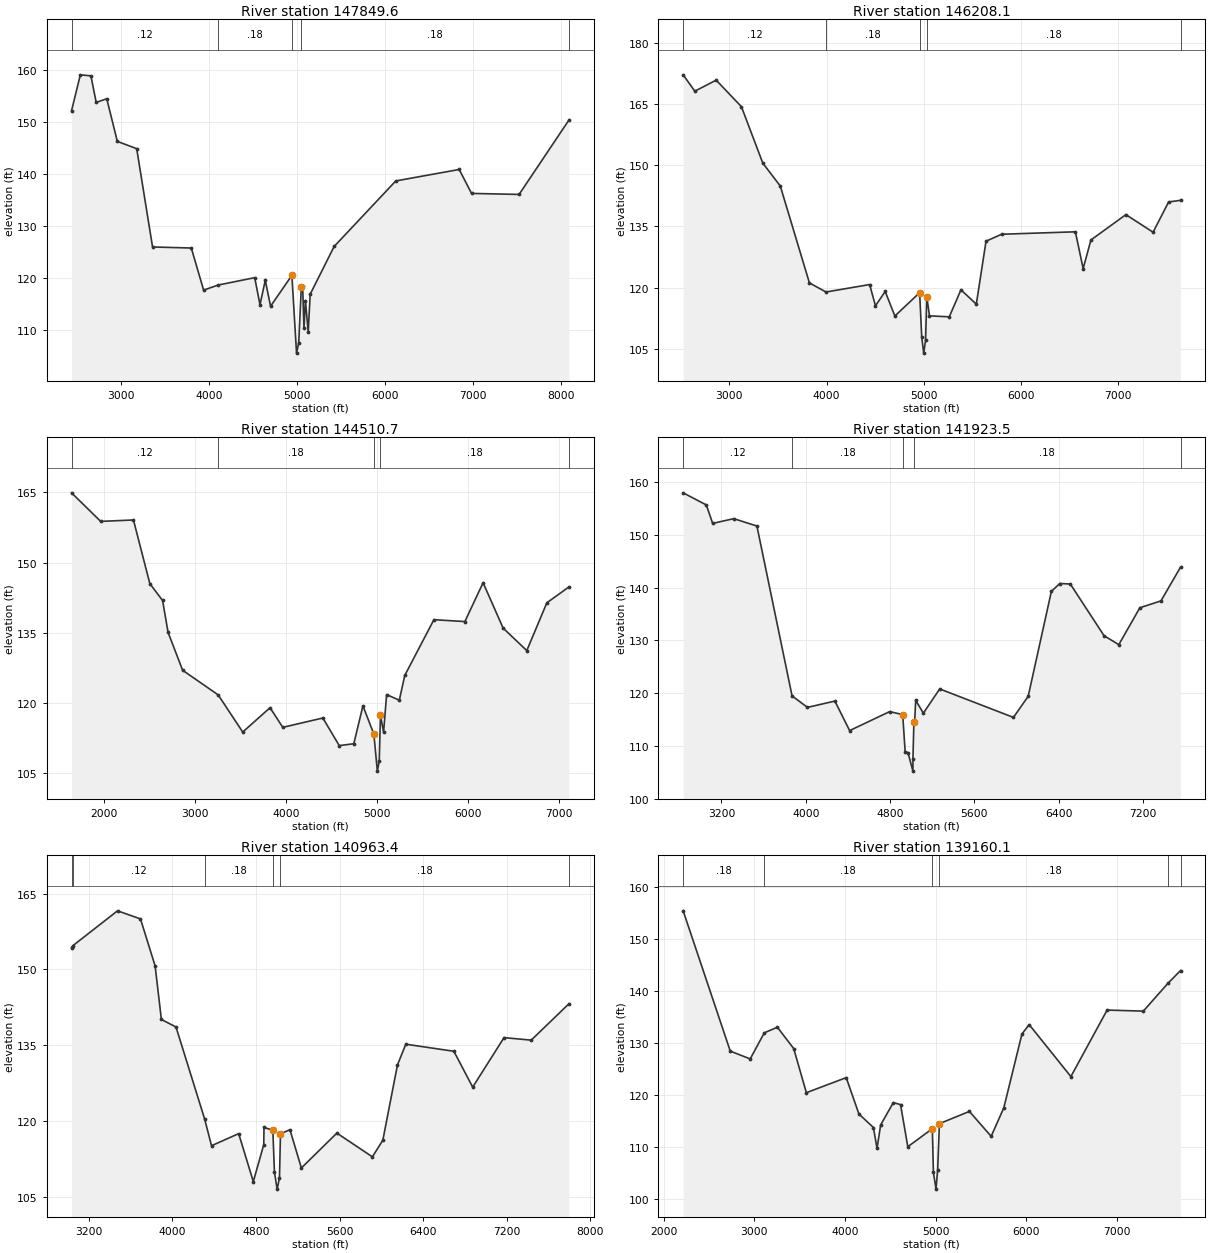
Type RM Length L Ch R = 1 ,147849.6,1081.21,1641.5,1091.32
BEGIN DESCRIPTION:
Cross Section XS111
Ineffective at Sta 6500 based on topo upstream of the cross section
END DESCRIPTION:
XS GIS Cut Line= 3
    3063077.7505   13991002.2329    3062067.5447   13988560.9024
    3060518.5626   13985984.8777
#Sta/Elev= 30
    2439   152.2    2539   159.1    2659   158.9    2719   153.8    2839   154.5
    2959   146.3    3179   144.9    3359     126    3799   125.8    3939   117.7
  4103.8  118.68    4519   120.1    4579   114.9    4639   119.6    4699   114.6
  4941.2  120.55    4994  105.59  5019.2   107.6  5048.2  118.29    5063  118.58
  5078.5  110.42  5095.1  115.69  5126.5  109.64  5148.9  116.91  5421.1   126.1
  6121.1   138.7  6841.1   140.9  6981.1   136.3  7521.1   136.1    8087   150.4
#Mann= 5 ,-1 , 0
    2439     .12       0  4103.8     .18       0  4941.2     .07       0
  5048.2     .18       0    8087      .2       0
#XS Ineff= 2 , 0
       0                    6500       0     136
Permanent Ineff=
       F       F
Bank Sta=4941.2,5048.2
XS Rating Curve= 0
Exp/Cntr=.3,.1

Type RM Length L Ch R = 1 ,146208.1,1174.58,1697.4,1139
BEGIN DESCRIPTION:
Cross Section XS110
Ineffective at Sta 7200 based on topo upstream of the cross section
END DESCRIPTION:
XS GIS Cut Line= 3
    3064278.9525   13990744.8394    3062991.6627     13988170.26
    3062006.6062   13986155.3717
#Sta/Elev= 30
  2523.8   172.1  2643.8   168.1  2863.8   170.8  3123.8   164.3  3343.8   150.5
  3523.8   144.9  3823.8   121.2    3995  118.97  4443.8   120.8  4503.8   115.6
  4603.8   119.1  4703.8   113.1  4958.7  118.81  4980.1  107.99  5000.4  104.02
  5019.8  107.13  5032.2  117.85    5060  113.14  5263.8   112.9  5383.8   119.5
  5542.3     116  5642.3   131.4  5802.3   133.1  6562.3   133.7  6642.3   124.7
  6722.3   131.7  7082.3   137.9  7362.3   133.6  7522.3     141  7645.1   141.4
#Mann= 5 ,-1 , 0
  2523.8     .12       0    3995     .18       0  4958.7     .07       0
  5032.2     .18       0  7645.1      .2       0
#XS Ineff= 2 , 0
       0                    7200       0     136
Permanent Ineff=
       F       F
Bank Sta=4958.7,5032.2
XS Rating Curve= 0
Exp/Cntr=.3,.1

Type RM Length L Ch R = 1 ,144510.7,1343.92,2587.2,1313.21
BEGIN DESCRIPTION:
Cross Section XS109
Ineffective at Sta 6000 based on topo upstream of the cross section
END DESCRIPTION:
XS GIS Cut Line= 3
    3065846.0878   13990532.1568    3063842.3933   13987565.7935
    3063540.1601   13985707.6188
#Sta/Elev= 30
  1642.8   164.9  1962.8   158.8  2322.8   159.1  2502.8   145.5  2642.8   141.9
  2702.8   135.1  2862.8     127  3253.3  121.73  3522.8   113.8  3822.8     119
  3962.8   114.8  4402.8   116.8  4582.8   110.9  4742.8   111.3  4842.8   119.4
    4963  113.36  5001.3  105.45    5022  107.62  5035.5  117.38  5069.9  113.78
  5102.8   121.8  5242.5   120.6  5302.5   125.9  5622.5   137.8  5962.5   137.4
  6162.5   145.7  6382.5     136  6642.5   131.2  6862.5   141.4  7105.1   144.8
#Mann= 5 ,-1 , 0
  1642.8     .12       0  3253.3     .18       0    4963     .07       0
  5035.5     .18       0  7105.1      .2       0
#XS Ineff= 2 , 0
       0                    6000       0     134
Permanent Ineff=
       F       F
Bank Sta=4963,5035.5
XS Rating Curve= 0
Exp/Cntr=.3,.1

Type RM Length L Ch R = 1 ,141923.5,1152.76,960.1,682.7
BEGIN DESCRIPTION:
Cross Section XS108
Ineffective at Sta 6600 based on topo upstream of the cross section
END DESCRIPTION:
XS GIS Cut Line= 3
    3066226.6778   13989446.3559    3065409.5286   13987174.0097
    3063943.1377   13985394.1917
#Sta/Elev= 30
  2836.6     158  3056.6   155.7  3116.6   152.2  3316.6   153.1  3536.6   151.7
  3870.2  119.48  4016.6   117.3  4276.6   118.5  4416.6   112.9  4796.6   116.5
  4920.4  115.93  4943.6   108.9  4970.2  108.73  5017.5  105.21  5017.7  107.57
  5026.5  114.58  5033.7  114.51  5043.7  118.64  5116.6   116.2  5271.4   120.8
  5971.4   115.4  6111.4   119.4  6331.4   139.3  6411.4   140.8  6511.4   140.7
  6831.4   130.9  6971.4   129.2  7171.4   136.2  7371.4   137.5  7557.5   143.9
#Mann= 5 ,-1 , 0
  2836.6     .12       0  3870.2     .18       0  4920.4     .07       0
  5026.5     .18       0  7557.5      .2       0
#XS Ineff= 2 , 0
       0                    6600       0     134
Permanent Ineff=
       F       F
Bank Sta=4920.4,5026.5
XS Rating Curve= 0
Exp/Cntr=.3,.1

Type RM Length L Ch R = 1 ,140963.4,1679.71,1803.3,1082.1
BEGIN DESCRIPTION:
Cross Section XS107
Ineffective at Sta 6300 based on topo upstream of the cross section
END DESCRIPTION:
XS GIS Cut Line= 2
    3067648.2934   13988226.2291    3064144.6266   13985002.4079
#Sta/Elev= 30
  3033.6   154.3  3047.7  154.72  3473.6   161.6  3693.6     160  3833.6   150.7
  3893.6   140.1  4033.6   138.6  4308.5  120.33  4373.6   115.1  4633.6   117.5
  4773.6     108  4873.6   115.3  4875.9  118.73  4960.7  118.16 4975.91  109.87
  5001.9  106.51  5024.1  108.74  5033.7  117.45  5124.3  118.28  5233.6   110.7
  5573.6   117.6  5913.6   112.9  6013.6   116.2  6153.6   131.1  6233.6   135.2
  6693.6   133.8  6873.6   126.7  7173.6   136.5  7433.6     136  7794.8   143.2
#Mann= 6 ,-1 , 0
  3033.6      .2       0  3047.7     .12       0  4308.5     .18       0
  4960.7     .07       0  5033.7     .18       0  7794.8      .2       0
#XS Ineff= 2 , 0
       0                    6300       0     134
Permanent Ineff=
       F       F
Bank Sta=4960.7,5033.7
XS Rating Curve= 0
Exp/Cntr=.3,.1

Type RM Length L Ch R = 1 ,139160.1,953.05,1504.1,1146.6
BEGIN DESCRIPTION:
Cross Section XS106
Ineffective at Sta 6050 based on topo upstream of the cross section
END DESCRIPTION:
XS GIS Cut Line= 3
    3069237.8163   13986927.7456    3067178.1528    13985696.425
    3064200.5957    13984868.082
#Sta/Elev= 30
  2214.5   155.4  2734.5   128.4  2954.5   126.9    3110  131.92  3254.5     133
  3434.5   128.9  3574.5   120.4  4014.5   123.3  4154.5   116.3  4314.5   113.7
  4354.5   109.7  4394.5   114.2  4534.5   118.5  4614.2   118.1  4694.2     110
  4965.1  113.47  4976.8  105.08  5005.6  101.84  5023.6  105.51  5043.1  114.44
  5374.2   116.8  5614.2     112  5754.2   117.5  5954.2   131.7  6034.2   133.5
  6494.2   123.5  6894.2   136.3  7294.2   136.1  7565.4  141.45  7704.8   143.9
#Mann= 6 ,-1 , 0
  2214.5     .18       0    3110     .18       0  4965.1     .07       0
  5043.1     .18       0  7565.4     .18       0  7704.8      .2       0
#XS Ineff= 2 , 0
       0                    6050       0     133
Permanent Ineff=
       F       F
Bank Sta=4965.1,5043.1
XS Rating Curve= 0
Exp/Cntr=.3,.1