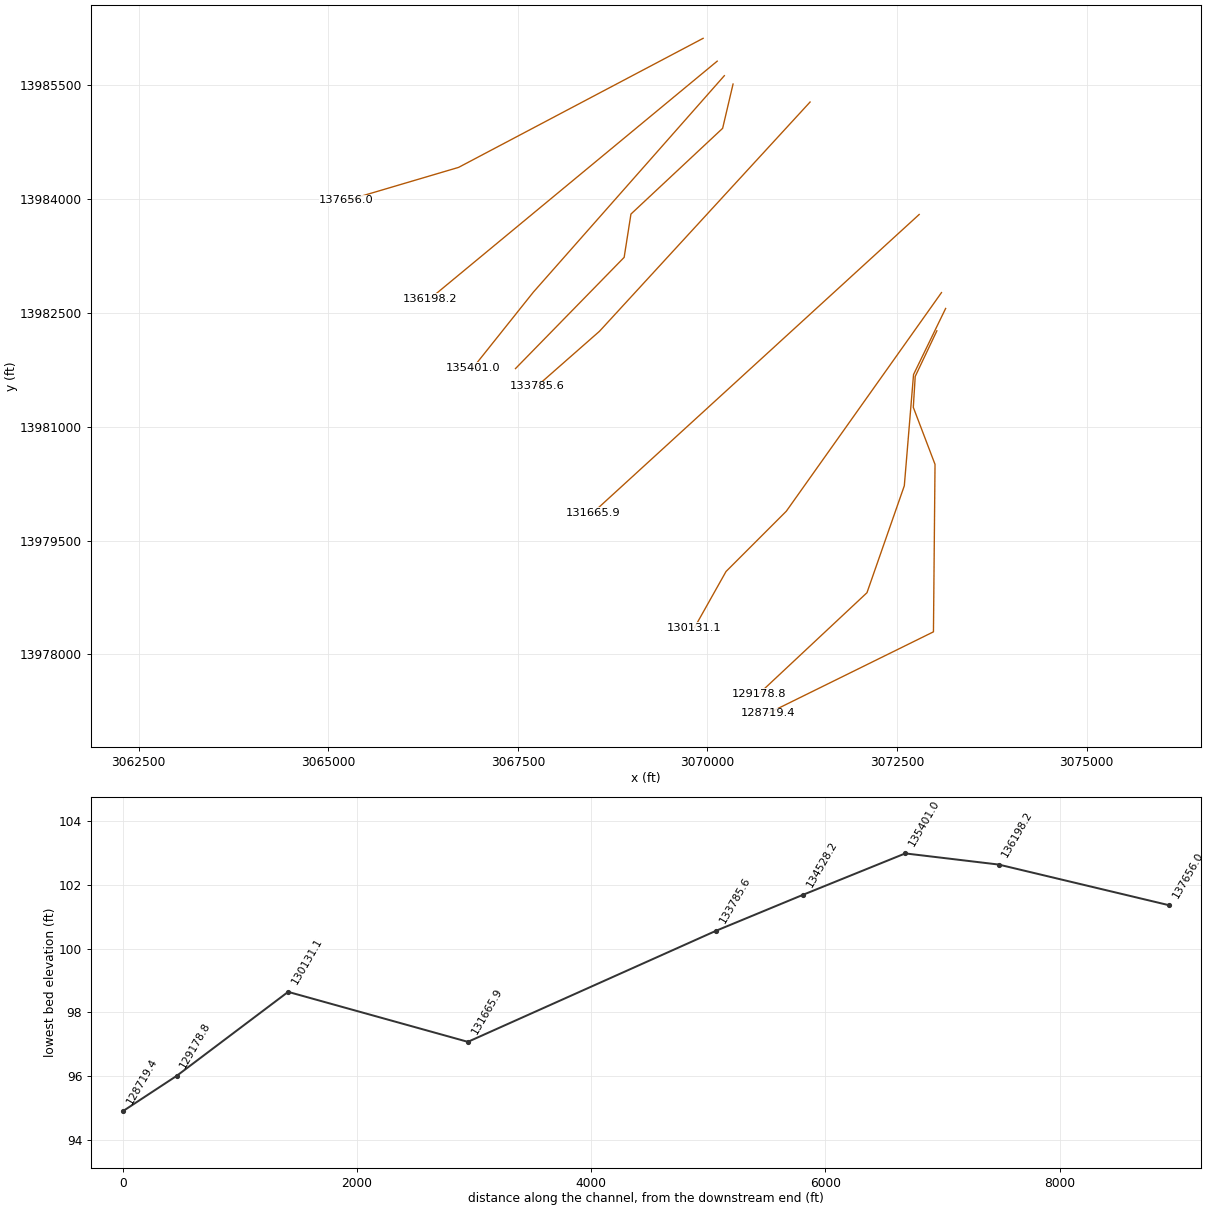
HEC-RAS study J100-00-00.prj: J100-00-00

--- J100-00-00.g01 (geometry) --- (continued)

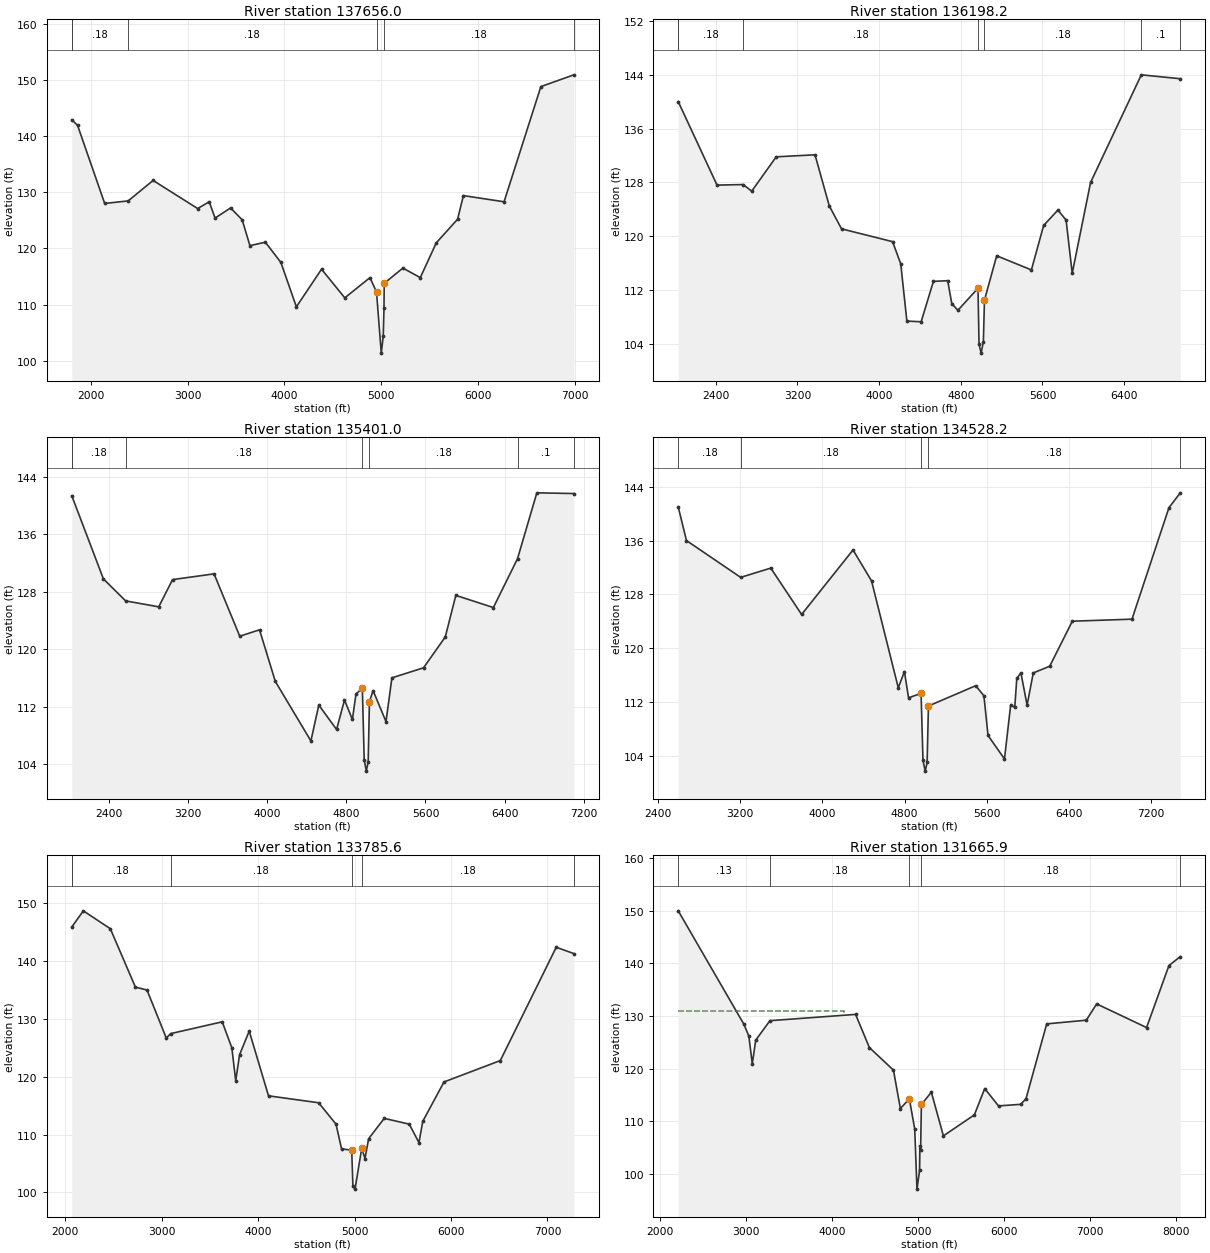
Type RM Length L Ch R = 1 ,137656.0,757.32,1457.8,1108.48
BEGIN DESCRIPTION:
Cross Section XS105
END DESCRIPTION:
XS GIS Cut Line= 3
    3069943.0272   13986121.7903     3066719.206   13984420.3291
    3065241.6213   13983983.7699
#Sta/Elev= 30
  1803.3   142.9  1863.3   141.9  2143.3     128  2386.3  128.46  2643.3   132.1
  3103.3   127.1  3223.3   128.3  3283.3   125.4  3443.3   127.2  3563.3   125.1
  3643.3   120.5  3803.3   121.1  3963.3   117.5  4123.3   109.6  4383.3   116.3
  4623.3   111.2  4883.3   114.8    4951  112.26  5000.2  101.36  5020.6  104.36
  5028.1  109.31  5030.6  113.79  5223.3   116.5  5403.3   114.8  5568.6     121
  5788.6   125.2  5848.6   129.4  6268.6   128.3  6648.6   148.8  6989.3   150.9
#Mann= 6 , 1 , 0
  1803.3      .2       0  1803.3     .18       0  2386.3     .18       0
    4951     .07       0  5030.6     .18       0  6989.3      .2       0
Bank Sta=4951,5030.6
XS Rating Curve= 0
Exp/Cntr=.3,.1

Type RM Length L Ch R = 1 ,136198.2,503.01,797.2,762.13
BEGIN DESCRIPTION:
Cross Section XS104
END DESCRIPTION:
XS GIS Cut Line= 2
    3070128.7853    13985820.783     3066338.616   13982685.2864
#Sta/Elev= 30
  2031.7     140  2411.7   127.6  2667.7  127.68  2751.7   126.7  2991.7   131.8
  3371.7   132.1  3511.7   124.5  3631.7   121.1  4131.7   119.2  4211.7   115.9
  4271.7   107.4  4411.7   107.3  4531.7   113.3  4671.7   113.4  4711.7     110
  4771.7     109  4968.7  112.29 4978.61  103.96  4999.6  102.64  5021.3  104.35
  5031.9  110.52  5151.7   117.1  5491.7     115  5611.7   121.6  5751.7   123.9
  5831.7   122.4  5891.7   114.5  6071.7     128  6568.8  143.98  6950.7   143.4
#Mann= 7 , 1 , 0
  2031.7      .2       0  2031.7     .18       0  2667.7     .18       0
  4968.7     .07       0  5031.9     .18       0  6568.8      .1       0
  6950.7      .2       0
Bank Sta=4968.7,5031.9
XS Rating Curve= 0
Exp/Cntr=.3,.1

Type RM Length L Ch R = 1 ,135401.0,310.55,872.8,611.86
BEGIN DESCRIPTION:
Cross Section XS103
END DESCRIPTION:
XS GIS Cut Line= 3
    3070222.8728    13985629.262    3067704.2625    13982774.837
     3066909.501   13981778.5867
#Sta/Elev= 30
  2020.4   141.4  2340.4   129.8  2565.5  126.73  2900.4   125.9  3040.4   129.7
  3460.4   130.5  3720.4   121.8  3920.4   122.7  4080.4   115.5  4440.4   107.2
  4520.4   112.2  4700.4   108.8  4780.4   112.9  4860.4   110.2  4896.6  113.74
  4961.2  114.56  4979.8   104.6  5001.2  102.99  5020.1  104.28  5032.8  112.68
    5070  114.21  5200.4   109.9  5260.4     116  5580.4   117.4  5800.4   121.7
  5907.1   127.5  6287.1   125.8  6531.3  132.61  6727.1   141.8  7101.5   141.7
#Mann= 7 , 1 , 0
  2020.4      .2       0  2020.4     .18       0  2565.5     .18       0
  4961.2     .07       0  5032.8     .18       0  6531.3      .1       0
  7101.5      .2       0
Bank Sta=4961.2,5032.8
XS Rating Curve= 0
Exp/Cntr=.3,.1

Type RM Length L Ch R = 1 ,134528.2,753.34,742.6,471.66
BEGIN DESCRIPTION:
Cross Section XS102
END DESCRIPTION:
XS GIS Cut Line= 5
     3070337.874   13985519.3034    3070200.4852   13984935.2449
    3068991.5522   13983804.6687    3068902.0016   13983233.7837
    3067469.1922   13981767.3928
#Sta/Elev= 30
  2599.3     141  2679.3     136  3206.6  130.52  3499.3   131.9  3799.3     125
  4299.3   134.6  4479.3     130  4739.3   114.1  4799.3   116.5  4839.3   112.6
  4961.2  113.26  4979.8   103.3  5001.2  101.69  5020.1  102.98  5032.8  111.38
  5492.4   114.4  5572.4   112.9  5612.4     107  5772.4   103.5  5832.4   111.5
  5872.4   111.2  5892.4   115.5  5932.4   116.3  5992.4   111.5  6052.4   116.3
  6212.4   117.3  6432.4     124  7012.4   124.3  7372.4   140.9  7482.6   143.1
#Mann= 5 ,-1 , 0
  2599.3     .18       0  3206.6     .18       0  4961.2     .07       0
  5032.8     .18       0  7482.6      .2       0
Bank Sta=4961.2,5032.8
XS Rating Curve= 0
Exp/Cntr=.3,.1

Type RM Length L Ch R = 1 ,133785.6,1885.85,2119.7,1757.46
BEGIN DESCRIPTION:
Cross Section XS101
END DESCRIPTION:
XS GIS Cut Line= 3
     3071353.449   13985282.2535    3068577.3807   13982259.9211
    3067749.0378   13981532.3225
#Sta/Elev= 30
    2067   145.9    2187   148.7    2467   145.6    2727   135.5    2847     135
    3047   126.7  3092.8  127.46    3627   129.5    3727     125    3767   119.3
    3807   123.8    3907   127.9    4107   116.7    4627   115.5    4807   111.8
  4864.4  107.53    4970  107.29  4982.2  101.17  5004.3  100.56  5074.2  107.68
  5107.4  105.85  5145.6  109.29    5307   112.8    5567   111.8    5667   108.6
    5707   112.3    5927   119.1  6510.8   122.8  7090.8   142.4  7273.3   141.3
#Mann= 6 , 1 , 0
    2067      .2       0    2067     .18       0  3092.8     .18       0
    4970     .07       0  5074.2     .18       0  7273.3      .2       0
Bank Sta=4970,5074.2
XS Rating Curve= 0
Exp/Cntr=.3,.1

Type RM Length L Ch R = 1 ,131665.9,1274.6,1534.8,1643.85
BEGIN DESCRIPTION:
Cross Section XS100
Ineffective at Sta 4140 based on topo upstream of the cross section
Ineffective at Sta 7140 based on topo upstream of the cross section
END DESCRIPTION:
XS GIS Cut Line= 2
    3072791.9797   13983799.4867    3068487.8302   13979864.4428
#Sta/Elev= 30
    2216     150    2976   128.5    3036   126.2    3076   120.9    3116   125.4
  3281.2  129.11    4276   130.3    4436     124    4716   119.7    4796   112.4
  4900.5  114.24  4963.1  108.48  4988.9   97.07  5019.4  100.65  5023.1  105.23
  5031.2  104.43  5040.3  113.17    5156   115.5    5296   107.2    5656   111.2
    5776   116.2    5936   112.9    6196   113.2    6256   114.3    6496   128.5
    6956   129.2    7076   132.3    7656   127.8    7916   139.6  8047.8   141.3
#Mann= 5 ,-1 , 0
    2216     .13       0  3281.2     .18       0  4900.5     .07       0
  5040.3     .18       0  8047.8      .2       0
#XS Ineff= 2 , 0
       0    4140     131    7140       0     131
Permanent Ineff=
       F       F
Bank Sta=4900.5,5040.3
XS Rating Curve= 0
Exp/Cntr=.3,.1

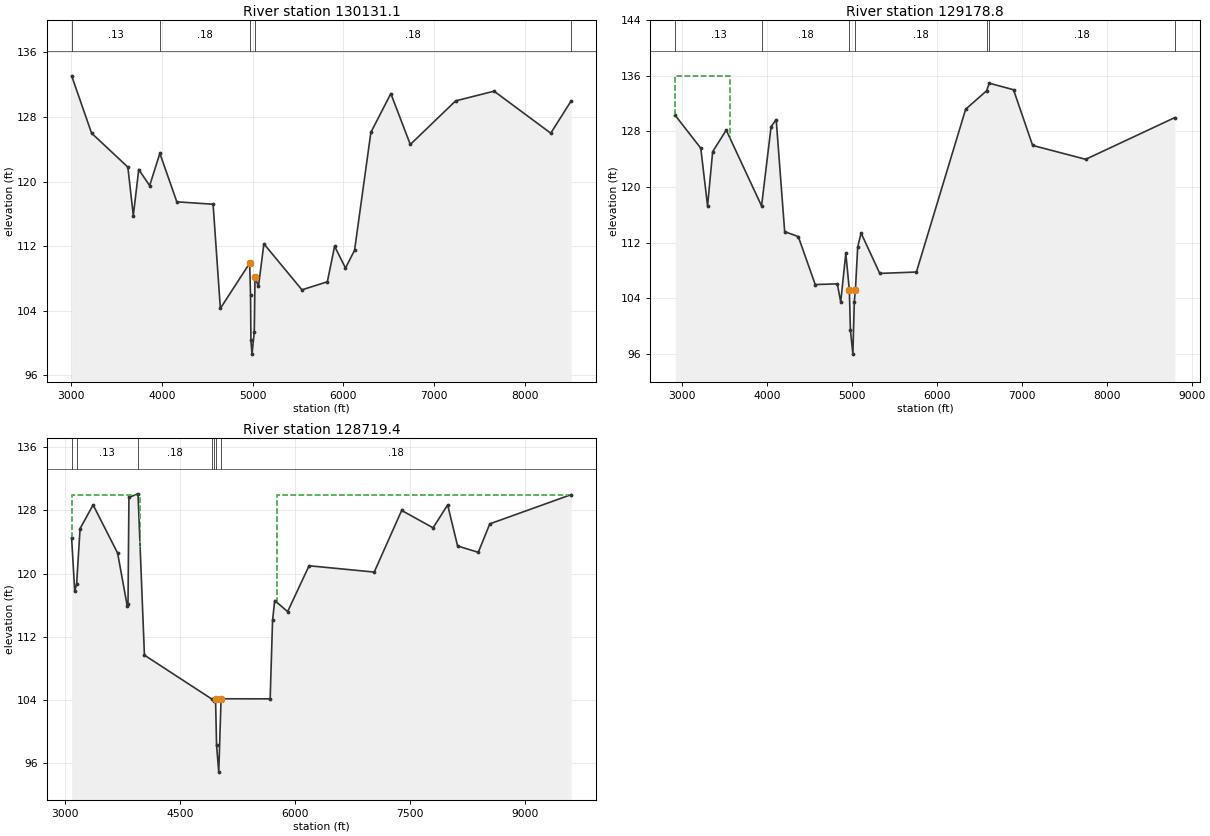
Type RM Length L Ch R = 1 ,130131.1,528.08,952.3,1161.7
BEGIN DESCRIPTION:
Cross Section XS99
END DESCRIPTION:
XS GIS Cut Line= 4
    3073086.0052   13982769.3205     3071040.022   13979886.8305
    3070245.2605    13979092.069     3069828.812   13978351.0759
#Sta/Elev= 30
  3004.5   133.1  3224.5     126  3624.5   121.8  3684.5   115.8  3744.5   121.5
  3864.5   119.5  3977.5   123.5  4164.5   117.5  4564.5   117.2  4644.5   104.3
  4967.6   109.9  4977.3  106.01  4981.6  100.33  4993.6   98.64  5018.8   101.4
    5027  108.16  5064.7  107.02  5124.5   112.3  5544.5   106.6  5824.5   107.6
  5904.5     112  6024.5   109.3  6124.5   111.5  6304.5   126.1  6524.5   130.9
  6739.3   124.6  7239.3     130  7663.3   131.2  8288.3     126  8513.3     130
#Mann= 5 ,-1 , 0
  3004.5     .13       0  3977.5     .18       0  4967.6     .07       0
    5027     .18       0  8513.3      .2       0
Bank Sta=4967.6,5027
XS Rating Curve= 0
Exp/Cntr=.3,.1

Type RM Length L Ch R = 1 ,129178.8,190.39,459.4,439.4
BEGIN DESCRIPTION:
Cross Section XS98-Bridge 4-Con
END DESCRIPTION:
XS GIS Cut Line= 5
    3073140.5843   13982560.1003    3072717.5611   13981689.1197
    3072595.9634   13980222.6452    3072103.4352   13978812.2234
    3070679.7211   13977479.7302
#Sta/Elev= 30
  2917.4   130.3  3217.4   125.6  3297.4   117.3  3357.4   125.1  3517.4   128.2
  3933.3   117.3  4045.7   128.7  4105.7   129.7  4205.7   113.6  4365.7   112.9
  4565.7     106  4825.7   106.1  4865.7   103.5  4925.7   110.5  4967.5  105.19
  4980.1   99.43  5009.1      96  5025.7  103.51  5039.2  105.28  5065.7   111.4
  5105.7   113.4  5325.7   107.6  5757.2   107.8  6337.2   131.2  6583.9  133.85
  6615.1  134.94  6901.1     134  7126.1     126  7751.1     124  8801.1     130
#Mann= 7 ,-1 , 0
  2917.4     .13       0  3933.3     .18       0  4967.5     .07       0
  5039.2     .18       0  6583.9     .18       0  6615.1     .18       0
  8801.1      .2       0
#XS Ineff= 2 , 0
       0    3565     136               0
Permanent Ineff=
       F       F
Bank Sta=4967.5,5039.2
XS Rating Curve= 0
Exp/Cntr=.5,.3

Type RM Length L Ch R = 1 ,128719.4,82.7,82.7,82.7
BEGIN DESCRIPTION:
Upstream Section of Gosling Road
END DESCRIPTION:
XS GIS Cut Line= 6
      3073024.97      13982265.3      3072739.63     13981664.05
      3072714.48     13981256.59      3073000.83     13980504.49
       3072980.1      13978296.5      3070798.61     13977221.45
#Sta/Elev= 30
  3089.2   124.5  3129.2   117.8  3154.2   118.7  3199.2   125.7  3369.2   128.7
  3689.2   122.6  3814.7   115.9  3824.7   116.2  3836.8  129.65  3955.3   130.1
    4039  109.69  4921.1  104.12  4948.3  103.94  4967.5  104.08  4980.1   98.32
  5009.1   94.89  5039.2  104.17  5679.8  104.16  5711.1  114.08  5739.1   116.6
  5907.7   115.2  6187.7     121  7037.7   120.2  7395.8     128  7805.8   125.8
  7995.8   128.7  8125.8   123.5  8395.8   122.7  8545.8   126.3  9607.8     130
#Mann= 7 ,-1 , 0
  3089.2     .13       0  3154.2     .13       0  3955.3     .18       0
  4921.1     .18       0  4948.3     .18       0  4967.5     .07       0
  5039.2     .18       0
#XS Ineff= 2 , 0
       0    3985     130    5775       0     130
Permanent Ineff=
       F       F
Bank Sta=4967.5,5039.2
XS Rating Curve= 0
Exp/Cntr=.5,.3