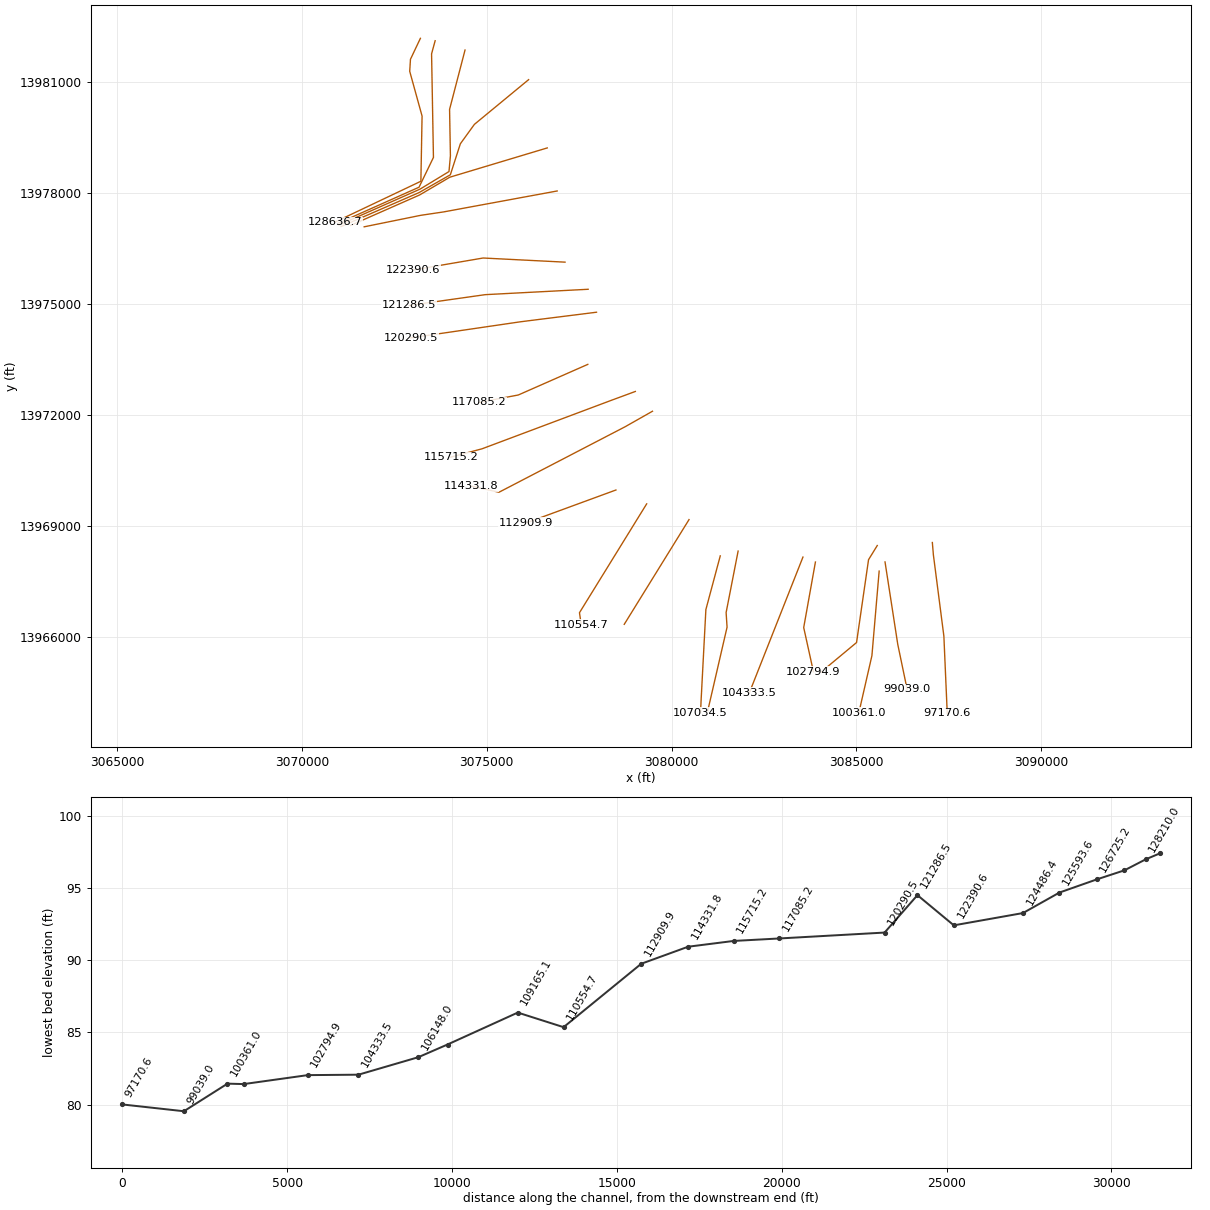
HEC-RAS study J100-00-00.prj: J100-00-00

--- J100-00-00.g01 (geometry) --- (continued)

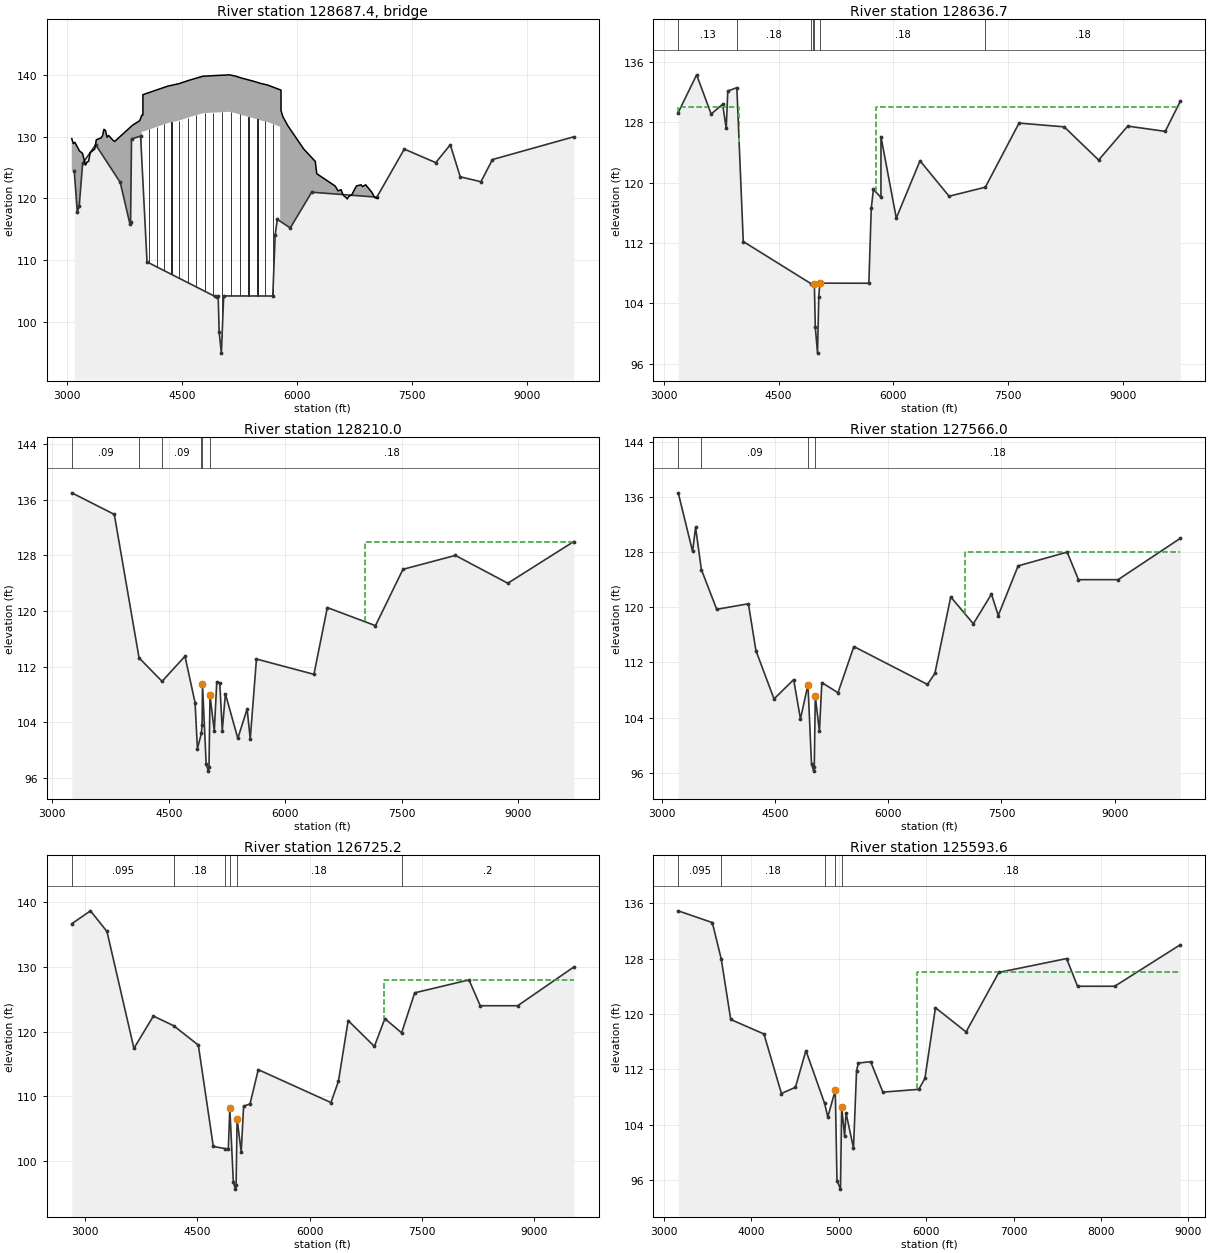
Type RM Length L Ch R = 3 ,128687.4,,,
BEGIN DESCRIPTION:
GOSLING ROAD
Structure ID: J100-00-00-04
Circular piers, twin-cylinder piers without diaphragm
END DESCRIPTION:
Node Name=Gosling Road
Bridge Culvert--1,0,-1,-1, 0
Deck Dist Width WeirC Skew NumUp NumDn MinLoCord MaxHiCord MaxSubmerge Is_Ogee
10,44,2.6,0, 163, 163, , , .95, 0, 1,1,,
  3057.2  3077.2  3097.2  3154.2  3157.2  3197.2  3237.2  3257.2  3277.2  3297.2
  3357.2  3377.2  3437.2  3457.2  3477.2  3497.2  3517.2  3537.2  3597.2  3617.2
  3637.2  3677.2  3697.2  3836.8  3848.4  3864.5  3916.1  3943.8  3955.3  3964.8
  3972.1 3972.21  3972.3 3985.09  3985.2 3985.31  4010.8  4019.9    4039  4067.3
  4081.6  4144.5  4164.6  4184.4  4261.4    4265  4306.5  4320.6  4359.1  4420.9
  4451.5  4456.4  4515.6  4568.4  4598.8  4639.2  4680.2  4742.7  4770.1  4792.2
  4855.2    4904  4921.1  4935.2  4948.3  4967.5  4970.8  4976.5  4978.2  4980.1
  4991.9  4998.6  5009.1  5012.6  5017.1  5019.7  5021.8  5025.7  5039.2  5057.9
    5114  5114.4  5131.4  5174.7    5193  5245.3  5247.2  5273.6  5305.1  5362.2
  5363.3  5404.4  5414.3    5477  5479.3  5521.8  5526.2  5579.7  5583.4  5608.7
  5640.9  5675.9  5678.8  5679.8    5688  5688.1  5711.1  5739.1 5775.99  5776.1
  5781.5  5786.6 5787.19  5787.3 5787.41  5811.6  5837.9  5851.1  5875.7  5931.1
  5951.1  5971.1  5974.2  6011.1  6051.1  6071.1  6084.2  6111.1  6151.1  6171.1
  6234.2  6254.2  6311.1  6391.1  6431.1  6491.1  6494.2  6531.1  6570.1  6571.1
  6590.1  6610.1  6611.1  6630.1  6631.1  6651.1  6671.1  6690.1  6711.1  6750.1
  6770.1  6771.1  6810.1  6831.1  6851.1  6870.1  6891.1  6930.1  6950.1  6971.1
  6990.1  7011.1  7051.1
   129.7   128.9   129.1  127.78  127.71  127.31  125.41  125.91  126.01  127.41
  128.01  129.51  129.81  130.11  131.21  131.01  129.91  130.21  129.41  129.24
  129.47  129.92  130.15  131.73  131.86  131.99  132.39  132.61  132.98  133.29
  133.53  133.53  133.53  133.53  136.83  136.83  136.94  136.98  137.06  137.18
  137.24  137.51   137.6  137.68  138.01  138.02   138.2  138.24  138.35  138.52
   138.6  138.62  138.87  139.08  139.21  139.36   139.5  139.73  139.83  139.84
  139.88  139.92  139.93  139.94  139.94  139.96  139.96  139.96  139.96  139.96
  139.97  139.98  139.98  139.99  139.99  139.99  139.99  139.99     140  140.01
  140.05  140.05     140  139.89  139.84  139.63  139.62  139.52  139.42  139.23
  139.23  139.09  139.06  138.82  138.81  138.65  138.64  138.49  138.48  138.41
  138.26  138.09  138.08  138.07  138.04  138.04  137.93  137.79  137.62  137.62
  137.59  137.57  137.54  137.54  134.24  133.26  132.66  132.36   131.8  130.79
  130.42  130.06     130  129.33   128.6  128.24     128  127.64  127.11  126.84
     126     124  123.53  122.86  122.53  122.03     122  121.22   121.4  121.41
  120.75   120.4  120.37   120.2  120.21  119.91  120.31  120.45  120.61  121.52
  121.99  122.01  122.14  122.21  121.91  122.05  122.21  121.62  121.33  121.01
  120.58  120.11  120.01
                                                                                
                                                                                
                                                                                
                  130.83  130.83  130.83  130.83  130.94  130.98  131.06  131.18
  131.24  131.51   131.6  131.68  132.01  132.02   132.2  132.24  132.35  132.52
   132.6  132.62  132.87  133.08  133.21  133.36   133.5  133.73  133.83  133.84
  133.88  133.92  133.93  133.94  133.94  133.96  133.96  133.96  133.96  133.96
  133.97  133.98  133.98  133.99  133.99  133.99  133.99  133.99     134  134.01
  134.05  134.05     134  133.89  133.84  133.63  133.62  133.52  133.42  133.23
  133.23  133.09  133.06  132.82  132.81  132.65  132.64  132.49  132.48  132.41
  132.26  132.09  132.08  132.07  132.04  132.04  131.93  131.79  131.62
                                                                                
                                                                                
                                                                                
                                                                                
                                                                                
                        
  3057.2  3077.2  3097.2  3154.2  3157.2  3197.2  3237.2  3257.2  3277.2  3297.2
  3357.2  3377.2  3437.2  3457.2  3477.2  3497.2  3517.2  3537.2  3597.2  3617.2
  3637.2  3677.2  3697.2  3836.8  3848.4  3864.5  3916.1  3943.8  3955.3  3964.8
  3972.1 3972.21  3972.3 3985.09  3985.2 3985.31  4010.8  4019.9    4039  4067.3
  4081.6  4144.5  4164.6  4184.4  4261.4    4265  4306.5  4320.6  4359.1  4420.9
  4451.5  4456.4  4515.6  4568.4  4598.8  4639.2  4680.2  4742.7  4770.1  4792.2
  4855.2    4904  4921.1  4935.2  4948.3  4967.5  4970.8  4976.5  4978.2  4980.1
  4991.9  4998.6  5009.1  5012.6  5017.1  5019.7  5021.8  5025.7  5039.2  5057.9
    5114  5114.4  5131.4  5174.7    5193  5245.3  5247.2  5273.6  5305.1  5362.2
  5363.3  5404.4  5414.3    5477  5479.3  5521.8  5526.2  5579.7  5583.4  5608.7
  5640.9  5675.9  5678.8  5679.8    5688  5688.1  5711.1  5739.1 5775.99  5776.1
  5781.5  5786.6 5787.19  5787.3 5787.41  5811.6  5837.9  5851.1  5875.7  5931.1
  5951.1  5971.1  5974.2  6011.1  6051.1  6071.1  6084.2  6111.1  6151.1  6171.1
  6234.2  6254.2  6311.1  6391.1  6431.1  6491.1  6494.2  6531.1  6570.1  6571.1
  6590.1  6610.1  6611.1  6630.1  6631.1  6651.1  6671.1  6690.1  6711.1  6750.1
  6770.1  6771.1  6810.1  6831.1  6851.1  6870.1  6891.1  6930.1  6950.1  6971.1
  6990.1  7011.1  7051.1
   129.7   128.9   129.1  127.78  127.71  127.31  125.41  125.91  126.01  127.41
  128.01  129.51  129.81  130.11  131.21  131.01  129.91  130.21  129.41  129.24
  129.47  129.92  130.15  131.73  131.86  131.99  132.39  132.61  132.98  133.29
  133.53  133.53  133.53  133.53  136.83  136.83  136.94  136.98  137.06  137.18
  137.24  137.51   137.6  137.68  138.01  138.02   138.2  138.24  138.35  138.52
   138.6  138.62  138.87  139.08  139.21  139.36   139.5  139.73  139.83  139.84
  139.88  139.92  139.93  139.94  139.94  139.96  139.96  139.96  139.96  139.96
  139.97  139.98  139.98  139.99  139.99  139.99  139.99  139.99     140  140.01
  140.05  140.05     140  139.89  139.84  139.63  139.62  139.52  139.42  139.23
  139.23  139.09  139.06  138.82  138.81  138.65  138.64  138.49  138.48  138.41
  138.26  138.09  138.08  138.07  138.04  138.04  137.93  137.79  137.62  137.62
  137.59  137.57  137.54  137.54  134.24  133.26  132.66  132.36   131.8  130.79
  130.42  130.06     130  129.33   128.6  128.24     128  127.64  127.11  126.84
     126     124  123.53  122.86  122.53  122.03     122  121.22   121.4  121.41
  120.75   120.4  120.37   120.2  120.21  119.91  120.31  120.45  120.61  121.52
  121.99  122.01  122.14  122.21  121.91  122.05  122.21  121.62  121.33  121.01
  120.58  120.11  120.01
                                                                                
                                                                                
                                                                                
                  130.83  130.83  130.83  130.83  130.94  130.98  131.06  131.18
  131.24  131.51   131.6  131.68  132.01  132.02   132.2  132.24  132.35  132.52
   132.6  132.62  132.87  133.08  133.21  133.36   133.5  133.73  133.83  133.84
  133.88  133.92  133.93  133.94  133.94  133.96  133.96  133.96  133.96  133.96
  133.97  133.98  133.98  133.99  133.99  133.99  133.99  133.99     134  134.01
  134.05  134.05     134  133.89  133.84  133.63  133.62  133.52  133.42  133.23
  133.23  133.09  133.06  132.82  132.81  132.65  132.64  132.49  132.48  132.41
  132.26  132.09  132.08  132.07  132.04  132.04  131.93  131.79  131.62
                                                                                
                                                                                
                                                                                
                                                                                
                                                                                
                        
Pier Skew, UpSta & Num, DnSta & Num=  ,4067.3, 2 ,4067.3, 2 , 0 , 0 , 0 ,,
     2.5     2.5
  108.67  132.19
     2.5     2.5
  108.67  132.19
Pier Skew, UpSta & Num, DnSta & Num=  ,4164.5, 2 ,4164.5, 2 , 0 , 0 , 0 ,,
     2.5     2.5
   107.5   132.6
     2.5     2.5
   107.5   132.6
Pier Skew, UpSta & Num, DnSta & Num=  ,4261.4, 2 ,4261.4, 2 , 0 , 0 , 0 ,,
     2.5     2.5
   106.8  133.01
     2.5     2.5
   106.8  133.01
Pier Skew, UpSta & Num, DnSta & Num=  ,4359.1, 2 ,4359.1, 2 , 0 , 0 , 0 ,,
     2.5     2.5
  105.06  133.35
     2.5     2.5
  105.06  133.35
Pier Skew, UpSta & Num, DnSta & Num=  ,4456.4, 2 ,4456.4, 2 , 0 , 0 , 0 ,,
     2.5     2.5
  105.22  133.63
     2.5     2.5
  105.22  133.63
Pier Skew, UpSta & Num, DnSta & Num=  ,4568.4, 2 ,4568.4, 2 , 0 , 0 , 0 ,,
     2.5     2.5
  104.12  134.09
     2.5     2.5
  104.12  134.09
Pier Skew, UpSta & Num, DnSta & Num=  ,4680.2, 2 ,4680.2, 2 , 0 , 0 , 0 ,,
     2.5     2.5
   103.5   134.5
     2.5     2.5
   103.5   134.5
Pier Skew, UpSta & Num, DnSta & Num=  ,4792.2, 2 ,4792.2, 2 , 0 , 0 , 0 ,,
     2.5     2.5
   103.7  134.84
     2.5     2.5
   103.7  134.84
Pier Skew, UpSta & Num, DnSta & Num=  ,4904, 2 ,4904, 2 , 0 , 0 , 0 ,,
     2.5     2.5
  103.22  134.92
     2.5     2.5
  103.22  134.92
Pier Skew, UpSta & Num, DnSta & Num=  ,5017.1, 2 ,5017.1, 2 , 0 , 0 , 0 ,,
     2.5     2.5
   97.88  134.99
     2.5     2.5
   97.88  134.99
Pier Skew, UpSta & Num, DnSta & Num=  ,5131.4, 2 ,5131.4, 2 , 0 , 0 , 0 ,,
     2.5     2.5
  104.36     135
     2.5     2.5
  104.36     135
Pier Skew, UpSta & Num, DnSta & Num=  ,5247.2, 2 ,5247.2, 2 , 0 , 0 , 0 ,,
     2.5     2.5
  104.39  134.63
     2.5     2.5
  104.39  134.63
Pier Skew, UpSta & Num, DnSta & Num=  ,5363.3, 2 ,5363.3, 2 , 0 , 0 , 0 ,,
     2.5     2.5
   103.8  134.23
     2.5     2.5
   103.8  134.23
Pier Skew, UpSta & Num, DnSta & Num=  ,5479.3, 2 ,5479.3, 2 , 0 , 0 , 0 ,,
     2.5     2.5
  102.91  133.82
     2.5     2.5
  102.91  133.82
Pier Skew, UpSta & Num, DnSta & Num=  ,5579.6, 2 ,5579.6, 2 , 0 , 0 , 0 ,,
     2.5     2.5
  103.52  133.49
     2.5     2.5
  103.52  133.49
Pier Skew, UpSta & Num, DnSta & Num=  ,5678.8, 2 ,5678.8, 2 , 0 , 0 , 0 ,,
     2.5     2.5
  103.01  133.08
     2.5     2.5
  103.01  133.08
Abutment Skew #Up #Dn= , 2 , 2
  3972.1  4019.9
  130.83  115.13
  3972.1  4019.9
  130.83  115.13
Abutment Skew #Up #Dn= , 2 , 2
  5688.1 5776.19
  105.46  131.62
  5688.1 5776.19
  105.46  131.62
BR Coef= 1 , 1 , 1 ,1.05, 0 ,,,.8,0,1.2,0,
WSPro=,,,, 1 ,,,, 0 ,,,, 0 ,,,,-1 ,-1 ,-1 , 0 , 0 , 0 , 0 , 0
BR U #Sta/Elev= 30
  3089.2   124.5  3129.2   117.8  3154.2   118.7  3199.2   125.7  3369.2   128.7
  3689.2   122.6  3814.7   115.9  3824.7   116.2  3836.8  129.65  3955.3   130.1
    4039  109.69  4921.1  104.12  4948.3  103.94  4967.5  104.08  4980.1   98.32
  5009.1   94.89  5039.2  104.17  5679.8  104.16  5711.1  114.08  5739.1   116.6
  5907.7   115.2  6187.7     121  7037.7   120.2  7395.8     128  7805.8   125.8
  7995.8   128.7  8125.8   123.5  8395.8   122.7  8545.8   126.3  9607.8     130
BR U #Mann= 7
  3089.2     .13  3154.2     .13  3955.3     .18  4921.1     .18  4948.3     .18
  4967.5    .065  5039.2     .18
BR D #Sta/Elev= 30
  3189.4   129.3  3429.4   134.3  3619.4   129.1  3769.4   130.4  3816.3   127.2
  3836.8  132.15  3955.3   132.6    4039  112.19  4921.1  106.62  4948.3  106.44
  4967.5  106.58  4980.1  100.82  5009.1   97.39  5025.7   104.9  5039.2  106.67
  5679.8  106.66  5711.1  116.58  5739.1   119.1  5837.9  118.05    5838   126.1
    6038   115.3    6348   122.9    6728   118.2  7201.8   119.4  7641.8   127.9
  8231.8   127.4  8681.8     123  9061.8   127.5  9551.8   126.8  9748.8   130.8
BR D #Mann= 7
  3189.4     .13  3955.3     .18  4921.1     .18  4948.3     .18  4967.5    .065
  5039.2     .18  7201.8      .2
BC Design=,, 0 ,, 0 ,,,,,,
BC HTab HWMax=131.23

Type RM Length L Ch R = 1 ,128636.7,540,426.7,295
BEGIN DESCRIPTION:
Downstream Section of Gosling Road
END DESCRIPTION:
XS GIS Cut Line= 6
      3073205.66     13982179.55      3072936.87     13981613.19
      3072916.76     13981287.38      3073250.89     13980077.13
       3073218.8     13978313.59      3070891.09     13977207.85
#Sta/Elev= 30
  3189.4   129.3  3429.4   134.3  3619.4   129.1  3769.4   130.4  3816.3   127.2
  3836.8  132.15  3955.3   132.6    4039  112.19  4921.1  106.62  4948.3  106.44
  4967.5  106.58  4980.1  100.82  5009.1   97.39  5025.7   104.9  5039.2  106.67
  5679.8  106.66  5711.1  116.58  5739.1   119.1  5837.9  118.05    5838   126.1
    6038   115.3    6348   122.9    6728   118.2  7201.8   119.4  7641.8   127.9
  8231.8   127.4  8681.8     123  9061.8   127.5  9551.8   126.8  9748.8   130.8
#Mann= 7 ,-1 , 0
  3189.4     .13       0  3955.3     .18       0  4921.1     .18       0
  4948.3     .18       0  4967.5     .07       0  5039.2     .18       0
  7201.8     .18       0
#XS Ineff= 2 , 0
       0    3985     130    5775       0     130
Permanent Ineff=
       F       F
Bank Sta=4967.5,5039.2
XS Rating Curve= 0
Exp/Cntr=.5,.3

Type RM Length L Ch R = 1 ,128210.0,610.77,644,619.67
BEGIN DESCRIPTION:
Cross Section XS97-Bridge 4- Exp
END DESCRIPTION:
XS GIS Cut Line= 5
    3073604.5073   13982114.3704     3073508.056    13981759.671
    3073558.6323   13978957.7431    3073169.3513   13978153.1214
    3070977.6162   13977175.2171
#Sta/Elev= 30
  3251.7     137  3799.3   133.9  4117.9  113.27  4413.8  109.89  4709.3   113.5
  4839.3   106.8  4869.3   100.2  4920.1   102.4  4929.3   103.6 4934.61   109.5
  4981.7   98.03  5010.1   96.98  5018.4   97.56  5031.5  107.86  5086.5  102.74
  5118.5  109.82  5157.3   109.6  5189.3   102.8  5229.3   108.1  5389.3   101.7
  5509.3   105.9  5549.3   101.6  5629.3   113.1  6369.3   110.9  6541.7   120.5
  7161.7   117.9  7515.5     126  8190.5     128  8865.5     124  9715.5     130
#Mann= 6 ,-1 , 0
  3251.7     .09       0  4117.9     .18       0  4413.8     .09       0
  4920.1     .18       0 4934.61     .07       0  5031.5     .18       0
#XS Ineff= 2 , 0
       0                    7030       0     130
Permanent Ineff=
       F       F
Bank Sta=4934.61,5031.5
XS Rating Curve= 0
Exp/Cntr=.3,.1

Type RM Length L Ch R = 1 ,127566.0,1057.89,840.8,317.09
BEGIN DESCRIPTION:
Cross Section XS96
END DESCRIPTION:
XS GIS Cut Line= 6
    3074413.0053   13981862.7297    3073994.8937   13980258.2263
    3074017.5791   13979002.5184    3073979.1089    13978576.238
    3073198.5318   13978102.0556    3071004.2794   13977129.8126
#Sta/Elev= 30
    3215   136.6    3405   128.1    3445   131.6  3521.6  125.47    3725   119.7
    4145   120.5    4245   113.7    4485   106.7    4745   109.5    4835   103.8
 4934.61  108.74  4981.7   97.27  5010.1   96.22  5018.4    96.8  5031.5   107.1
  5086.5  101.98  5118.5  109.06  5333.1   107.6  5543.1   114.3    6519   108.8
    6617   110.4    6827   121.5    7127   117.6    7367   121.9    7457   118.8
  7720.3     126  8370.3     128  8520.3     124  9045.3     124  9870.3     130
#Mann= 4 ,-1 , 0
    3215    .095       0  3521.6     .09       0 4934.61     .07       0
  5031.5     .18       0
#XS Ineff= 2 , 0
       0                    7017       0     128
Permanent Ineff=
       F       F
Bank Sta=4934.61,5031.5
XS Rating Curve= 0
Exp/Cntr=.3,.1

Type RM Length L Ch R = 1 ,126725.2,1296.94,1131.6,424.51
BEGIN DESCRIPTION:
Cross Section XS95.5
END DESCRIPTION:
XS GIS Cut Line= 6
    3076133.2117   13981062.1819    3074666.8208    13979853.249
    3074286.2308   13979327.1393    3074015.5845   13978488.6967
    3073169.3513   13978007.2192    3071060.9007   13977088.2872
#Sta/Elev= 30
  2823.9   136.7  3073.9   138.7  3293.9   135.5  3653.9   117.4  3913.9   122.4
  4183.4  120.91  4513.9   117.9  4713.9   102.2    4867  101.88  4914.4   101.8
 4934.61  108.11  4981.7   96.64  5010.1   95.59  5018.4   96.17  5031.5  106.47
  5086.5  101.35  5118.5  108.43  5204.4   108.8  5314.4   114.1  6284.8     109
  6384.8   112.3  6514.8   121.7  6864.8   117.7  7004.8     122  7228.4   119.8
  7403.4     126  8128.4     128  8278.4     124  8778.4     124  9528.4     130
#Mann= 6 ,-1 , 0
  2823.9    .095       0  4183.4     .18       0    4867     .18       0
 4934.61     .07       0  5031.5     .18       0  7228.4      .2       0
#XS Ineff= 2 , 0
       0                    6995       0     128
Permanent Ineff=
       F       F
Bank Sta=4934.61,5031.5
XS Rating Curve= 0
Exp/Cntr=.3,.1

Type RM Length L Ch R = 1 ,125593.6,1064.47,1107.2,948.15
BEGIN DESCRIPTION:
Cross Section XS95
END DESCRIPTION:
XS GIS Cut Line= 4
    3076636.9338    13979215.201    3074002.3377   13978423.8205
    3073183.9416   13977942.7304    3071316.4927   13977119.1311
#Sta/Elev= 30
  3165.5   134.9  3555.5   133.2  3657.9   127.9  3765.5   119.2  4145.5   117.1
  4345.5   108.5  4505.5   109.4  4625.5   114.7  4839.5  107.06  4875.5   105.1
  4961.4  108.98  4980.7    95.9  5020.8   94.68  5034.2   106.5  5067.8  102.36
  5083.9   105.7  5169.5   100.6  5204.5  111.82  5225.5   112.9  5365.5   113.1
  5505.5   108.7  5916.4   109.1  5986.4   110.7  6106.4   120.9  6456.4   117.4
  6831.4     126  7606.4     128  7731.4     124  8156.4     124  8906.4     130
#Mann= 5 ,-1 , 0
  3165.5    .095       0  3657.9     .18       0  4839.5     .18       0
  4961.4     .07       0  5034.2     .18       0
#XS Ineff= 2 , 0
       0                    5900       0     126
Permanent Ineff=
       F       F
Bank Sta=4961.4,5034.2
XS Rating Curve= 0
Exp/Cntr=.3,.1

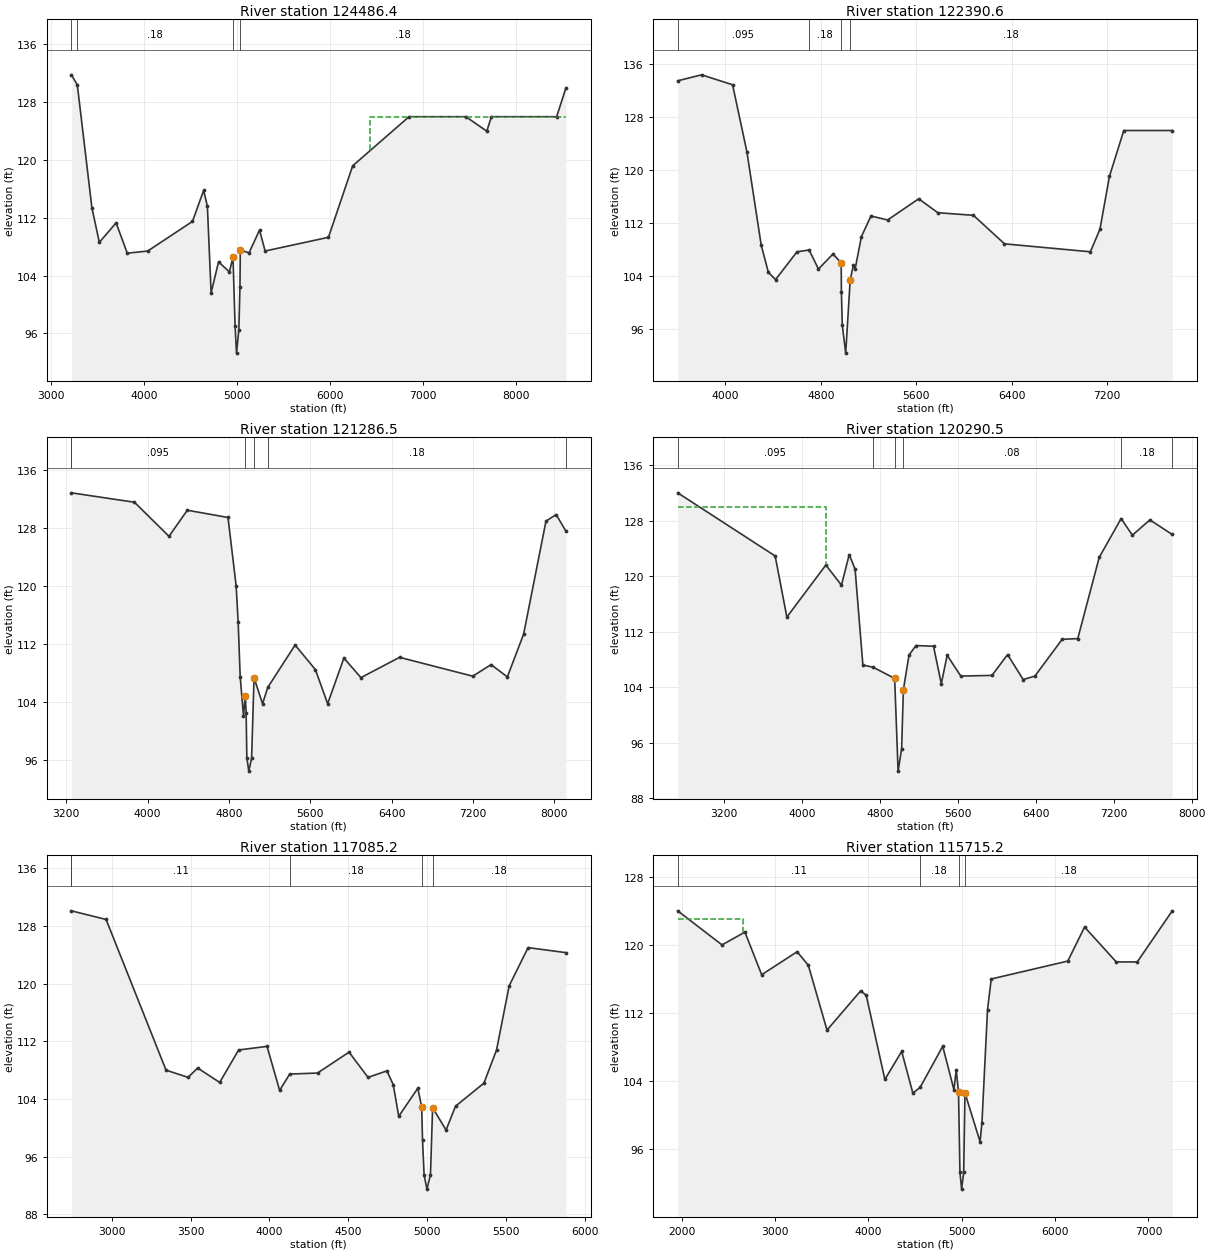
Type RM Length L Ch R = 1 ,124486.4,1725.3,2095.8,1421.71
BEGIN DESCRIPTION:
Cross Section XS94
END DESCRIPTION:
XS GIS Cut Line= 4
    3076905.5856   13978051.0434    3073833.0449   13977484.4756
    3073211.9548   13977391.8034    3071685.1394   13977081.6439
#Sta/Elev= 30
  3222.2   131.8  3285.7  130.42  3442.2   113.4  3522.2   108.6  3702.2   111.3
  3822.2   107.1  4042.2   107.4  4522.2   111.5  4642.2   115.8  4682.2   113.6
  4722.2   101.6  4802.2   105.9  4918.5  104.51  4957.3  106.56  4979.6   97.03
    4995   93.26  5020.1    96.5  5031.9  102.39  5035.8  107.54  5129.6  107.15
  5242.2   110.3  5302.2   107.4  5982.2   109.3  6242.2   119.2  6847.1     126
  7457.1     126  7682.1     124  7732.1     126  8432.1     126  8532.1     130
#Mann= 4 ,-1 , 0
  3222.2    .095       0  3285.7     .18       0  4957.3     .07       0
  5035.8     .18       0
#XS Ineff= 2 , 0
       0                  6432.1       0     126
Permanent Ineff=
       F       F
Bank Sta=4957.3,5035.8
XS Rating Curve= 0
Exp/Cntr=.3,.1

Type RM Length L Ch R = 1 ,122390.6,878.76,1104.1,997.74
BEGIN DESCRIPTION:
Cross Section XS93
No effective flow beyond limits of cross section
END DESCRIPTION:
XS GIS Cut Line= 4
    3077118.2682   13976125.7057    3074901.8911   13976237.6439
    3073200.4299   13975946.6045 3073003.293119813975912.8837368
#Sta/Elev= 30
  3600.3   133.5  3800.3   134.4  4060.3   132.9  4180.3   122.8  4300.3   108.7
  4360.3   104.6  4420.3   103.5  4600.3   107.7    4702  107.97  4780.3   105.1
  4901.5  107.36  4970.6  106.04  4972.5  101.62  4979.8   96.66  5008.6   92.41
  5046.2  103.46  5073.2   105.7  5087.3  105.08  5140.3     110  5220.3   113.1
  5360.3   112.5  5620.3   115.7  5780.3   113.6  6079.5   113.2  6339.5   108.9
  7059.5   107.7  7139.5   111.1  7219.5   119.1  7339.5     126  7745.7     126
#Mann= 4 ,-1 , 0
  3600.3    .095       0    4702     .18       0  4970.6     .07       0
  5046.2     .18       0
Bank Sta=4970.6,5046.2
XS Rating Curve= 0
Exp/Cntr=.3,.1

Type RM Length L Ch R = 1 ,121286.5,774.35,996,868.79
BEGIN DESCRIPTION:
Cross Section XS92
END DESCRIPTION:
XS GIS Cut Line= 3
    3077743.4278   13975392.0358      3074959.89   13975246.4913
    3072904.0746   13974955.4024
#Sta/Elev= 30
  3251.2   132.9  3871.2   131.6  4211.2   126.9  4391.2   130.5  4791.2   129.5
  4871.2   120.1  4891.2   115.1  4911.2   107.5  4943.6  102.17  4961.6  104.87
  4969.7  102.52  4976.6   96.35  4995.9    94.5  5023.4   96.28  5047.3  107.38
  5131.2   103.8  5182.2  106.05  5451.2   111.9  5651.2   108.5  5771.2   103.8
  5931.2   110.1  6098.5   107.4  6478.5   110.2  7198.5   107.6  7378.5   109.2
  7538.5   107.5  7698.5   113.4  7918.5     129  8018.5   129.9  8114.9   127.6
#Mann= 6 , 1 , 0
  3251.2      .2       0  3251.2    .095       0  4961.6     .07       0
  5047.3    .095       0  5182.2     .18       0  8114.9      .2       0
Bank Sta=4961.6,5047.3
XS Rating Curve= 0
Exp/Cntr=.3,.1

Type RM Length L Ch R = 1 ,120290.5,1856.54,3205.3,1980.65
BEGIN DESCRIPTION:
Ineffective at Sta 4250 based on transition with upstream cross section
Cross Section XS91
END DESCRIPTION:
XS GIS Cut Line= 3
    3077968.9988    13974771.253    3075920.5291   13974513.7951
     3072942.972    13974077.236
#Sta/Elev= 30
    2727     132    3727   122.9    3847   114.1    4247   121.6    4407   118.7
    4487   123.1    4547     121    4627   107.2  4732.1  106.87    4953  105.27
  4988.3   91.91  5024.4   95.14  5042.5  103.65  5100.2  108.63  5171.6     110
  5351.6   109.9  5431.6   104.5  5491.6   108.6  5631.6   105.6  5951.6   105.7
  6111.6   108.7  6271.6   105.1  6391.6   105.6  6671.6   110.9  6831.6     111
  7051.6   122.7  7276.6   128.3  7391.6   125.9  7571.6   128.1    7801     126
#Mann= 6 ,-1 , 0
    2727    .095       0  4732.1     .08       0    4953     .07       0
  5042.5     .08       0  7276.6     .18       0    7801      .2       0
#XS Ineff= 2 , 0
       0    4250     130               0
Permanent Ineff=
       F       F
Bank Sta=4953,5042.5
XS Rating Curve= 0
Exp/Cntr=.3,.1

Type RM Length L Ch R = 1 ,117085.2,1073.94,1370,1102.2
BEGIN DESCRIPTION:
Cross Section XS90
END DESCRIPTION:
XS GIS Cut Line= 3
    3077733.9285   13973360.8313    3075853.3661   13972532.4883
    3074792.6272    13972331.808
#Sta/Elev= 30
  2744.3   130.1  2964.3   128.9  3344.3     108  3484.3     107  3544.3   108.3
  3684.3   106.3  3804.3   110.8  3984.3   111.3  4064.3   105.2  4128.2  107.46
  4304.3   107.6  4504.3   110.5  4624.3     107  4744.3   107.9  4784.3     106
  4819.2   101.6    4940  105.49  4964.7  102.92  4970.1   98.26    4980    93.5
  4997.9    91.5  5020.3   93.48  5033.9  102.79  5119.2    99.7  5179.2     103
  5359.2   106.2  5439.2   110.8  5519.2   119.7  5639.2     125  5879.2   124.3
#Mann= 5 , 1 , 0
  2744.3      .2       0  2744.3     .11       0  4128.2     .18       0
  4964.7     .07       0  5033.9     .18       0
Bank Sta=4964.7,5033.9
XS Rating Curve= 0
Exp/Cntr=.3,.1

Type RM Length L Ch R = 1 ,115715.2,993.03,1383.4,1149.99
BEGIN DESCRIPTION:
Cross Section XS89
END DESCRIPTION:
XS GIS Cut Line= 4
    3079019.4516   13972628.0807    3078362.7481   13972385.7164
    3074875.4147   13971077.9663     3074030.207   13970851.5839
#Sta/Elev= 30
  1955.6     124  2430.6     120  2675.6   121.5  2855.6   116.5  3235.6   119.2
  3355.6   117.6  3555.6     110  3915.6   114.6  3975.6   114.1  4175.6   104.2
  4355.6   107.5  4475.6   102.6  4553.2  103.27  4795.6   108.1  4915.6     103
    4940  105.32  4964.7  102.75    4980   93.33  4997.9   91.33  5020.3   93.31
  5033.9  102.62  5195.6    96.9  5215.6    99.1  5275.6   112.4  5315.6     116
  6135.6   118.1  6315.6   122.1  6655.1     118  6880.1     118  7255.1     124
#Mann= 4 ,-1 , 0
  1955.6     .11       0  4553.2     .18       0  4964.7     .07       0
  5033.9     .18       0
#XS Ineff= 2 , 0
       0  2655.6     123               0
Permanent Ineff=
       F       F
Bank Sta=4964.7,5033.9
XS Rating Curve= 0
Exp/Cntr=.3,.1

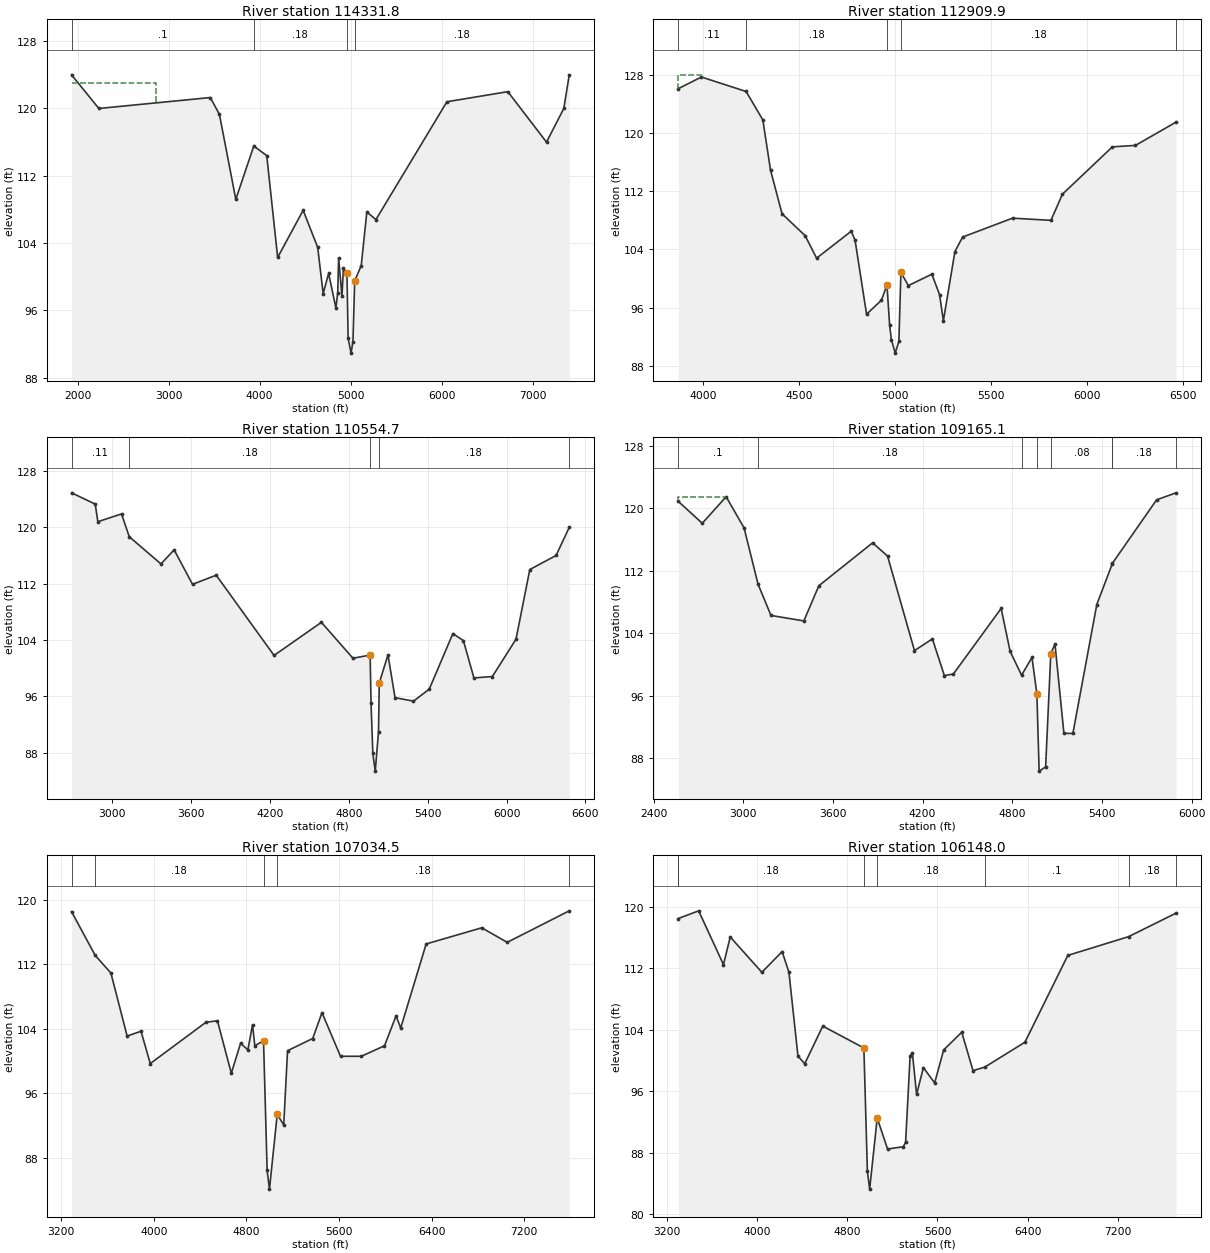
Type RM Length L Ch R = 1 ,114331.8,1324.61,1421.9,1196
BEGIN DESCRIPTION:
Cross Section XS88
END DESCRIPTION:
XS GIS Cut Line= 4
    3079483.0573   13972092.8358    3078747.9768   13971676.0846
    3075331.6065   13969902.0051    3074575.2679   13970071.0519
#Sta/Elev= 30
  1933.6     124  2233.6     120  3458.6   121.3  3558.6   119.3  3738.6   109.2
  3936.2  115.54  4078.6   114.4  4198.6   102.3  4478.6   107.9  4638.6   103.5
  4698.6      98  4758.6   100.4  4838.6    96.3  4858.6    98.1  4868.6  102.25
    4905   97.68  4921.1  101.03  4960.2  100.45  4973.1    92.7  5005.5   90.93
    5026   92.31  5045.2   99.51    5117  101.33  5178.6   107.7  5278.6   106.8
  6058.6   120.8  6728.1     122  7153.1     116  7343.1     120  7403.1     124
#Mann= 4 ,-1 , 0
  1933.6      .1       0  3936.2     .18       0  4960.2     .07       0
  5045.2     .18       0
#XS Ineff= 2 , 0
       0  2858.6     123               0
Permanent Ineff=
       F       F
Bank Sta=4960.2,5045.2
XS Rating Curve= 0
Exp/Cntr=.3,.1

Type RM Length L Ch R = 1 ,112909.9,1662.74,2355.2,2424.76
BEGIN DESCRIPTION:
Upstream of Confluence with Willow Creek (M100-00-00)
Cross section not extended right to avoid crossing M100-00-00
Cross Section XS87
END DESCRIPTION:
XS GIS Cut Line= 2
    3078494.5369   13969962.8307    3076061.5135   13969070.7221
#Sta/Elev= 30
  3870.9   126.1  3990.9   127.7  4223.9  125.71  4310.9   121.8  4350.9   114.9
  4410.9   108.9  4530.9   105.9  4590.9   102.8  4770.9   106.5  4790.9   105.3
  4850.9    95.1  4928.3   97.02  4957.2   99.12    4971    93.6    4980   91.62
  5000.2   89.75  5019.2   91.38  5029.8  100.84  5068.5   99.03  5190.9   100.6
  5230.9    97.8  5250.9    94.2  5310.9   103.7  5350.9   105.7  5610.9   108.3
  5810.9     108  5870.9   111.6  6130.9   118.1  6250.9   118.3  6462.3   121.5
#Mann= 5 ,-1 , 0
  3870.9     .11       0  4223.9     .18       0  4957.2     .07       0
  5029.8     .18       0  6462.3      .2       0
#XS Ineff= 2 , 0
       0    4000     128               0
Permanent Ineff=
       F       F
Bank Sta=4957.2,5029.8
XS Rating Curve= 0
Exp/Cntr=.3,.1

Type RM Length L Ch R = 1 ,110554.7,1203.91,1389.6,1218.38
BEGIN DESCRIPTION:
Downstream of Confluence with Willow Creek (M100-00-00)
Cross section not extended right to avoid crossing M101-00-00
Cross Section XS86
END DESCRIPTION:
XS GIS Cut Line= 3
    3079325.8198   13969587.7396    3077508.4081   13966643.5325
    3077555.0786    13966321.901
#Sta/Elev= 30
  2691.6   124.9  2871.6   123.3  2891.6   120.8  3071.6   121.9  3130.6  118.66
  3371.6   114.8  3471.6   116.8  3611.6   111.9  3791.6   113.2  4231.6   101.8
  4591.6   106.5  4831.6   101.4  4962.3  101.85    4969   95.08  4982.9   87.88
  5001.2   85.36    5026   90.98  5031.7   97.88  5097.9  101.88  5151.6    95.8
  5291.6    95.3  5411.6      97  5591.6   104.9  5671.6   103.9  5751.6    98.6
  5891.6    98.8  6071.6   104.1  6176.6     114  6376.6     116  6476.6     120
#Mann= 5 ,-1 , 0
  2691.6     .11       0  3130.6     .18       0  4962.3     .07       0
  5031.7     .18       0  6476.6      .2       0
Bank Sta=4962.3,5031.7
XS Rating Curve= 0
Exp/Cntr=.3,.1

Type RM Length L Ch R = 1 ,109165.1,1581.18,2130.6,2218.08
BEGIN DESCRIPTION:
Upstream of Confluence with J121-00-00
Cross Section XS85
END DESCRIPTION:
XS GIS Cut Line= 2
    3080471.3683   13969161.9605    3078719.6685   13966329.7102
#Sta/Elev= 30
  2565.5   120.9  2725.5   118.1  2885.5   121.5  3005.5   117.5  3098.9   110.3
  3185.5   106.3  3405.5   105.6  3505.5   110.1  3865.5   115.6  3965.5   113.9
  4145.5   101.8  4265.5   103.3  4345.5    98.6  4405.5    98.8  4725.5   107.2
  4785.5   101.7  4862.2   98.65  4931.7  100.93  4964.5   96.26  4979.7   86.37
  5023.1   86.91  5057.6  101.39  5085.6  102.65  5145.5    91.2  5205.5    91.2
  5365.5   107.7    5469  112.91  5470.3  112.99  5765.5   121.1  5895.7     122
#Mann= 8 ,-1 , 0
  2565.5      .1       0  3098.9     .18       0  4862.2     .08       0
  4964.5     .07       0  5057.6     .08       0    5469     .08       0
  5470.3     .18       0  5895.7     .08       0
#XS Ineff= 2 , 0
       0    2885   121.5    5900       0   122.5
Permanent Ineff=
       F       F
Bank Sta=4964.5,5057.6
XS Rating Curve= 0
Exp/Cntr=.3,.1

Type RM Length L Ch R = 1 ,107034.5,533.18,886.5,498.87
BEGIN DESCRIPTION:
Downstream of Confluence with J121-00-00
Cross Section XS84
END DESCRIPTION:
XS GIS Cut Line= 4
    3081316.4806    13968180.907    3080927.5602   13966728.9372
    3080798.6066   13964278.8194    3080782.9123   13963936.6219
#Sta/Elev= 30
  3289.6   118.5    3494  113.08  3629.6   110.9  3769.6   103.1  3889.6   103.7
  3969.6    99.7  4449.6   104.8  4549.6     105  4669.6    98.5  4749.6   102.2
  4812.8   101.4  4852.8   104.5  4872.8   101.9  4947.9  102.53  4979.1   86.48
  4999.2   84.16  5066.1   93.41  5122.4   92.11  5155.4  101.29  5372.8   102.8
  5452.8     106  5612.8   100.6  5792.8   100.6  5992.8   101.9  6092.8   105.6
  6132.8   104.1  6352.8   114.5  6832.8   116.5  7052.8   114.7  7588.8   118.6
#Mann= 5 ,-1 , 0
  3289.6     .11       0    3494     .18       0  4947.9     .07       0
  5066.1     .18       0  7588.8      .2       0
Bank Sta=4947.9,5066.1
XS Rating Curve= 0
Exp/Cntr=.3,.1

Type RM Length L Ch R = 1 ,106148.0,1814.5,1814.5,1814.5
BEGIN DESCRIPTION:
Cross Section XS83
END DESCRIPTION:
XS GIS Cut Line= 4
    3081799.3935   13968310.4023    3081474.9904   13966647.8364
    3081500.4568   13966251.2613    3080978.2481    13963991.786
#Sta/Elev= 30
  3303.8   118.5  3483.8   119.5  3703.8   112.5  3763.8   116.1  4043.8   111.5
  4223.8   114.2  4283.8   111.5  4363.8   100.6  4423.8    99.6  4583.8   104.5
  4947.9  101.65  4979.1    85.6  4999.2   83.28  5066.1   92.53  5157.7    88.5
  5297.7    88.8  5317.7    89.4  5357.7   100.6  5377.7     101  5415.1    95.6
  5475.1    99.1  5575.1    97.1  5655.1   101.4  5815.1   103.7  5915.1    98.7
  6019.1   99.16  6375.1   102.4  6755.1   113.7  7293.8  116.14  7714.1   119.2
#Mann= 7 , 1 , 0
  3303.8      .2       0  3303.8     .18       0  4947.9     .06       0
  5066.1     .18       0  6019.1      .1       0  7293.8     .18       0
  7714.1      .2       0
Bank Sta=4947.9,5066.1
XS Rating Curve= 0
Exp/Cntr=.3,.1

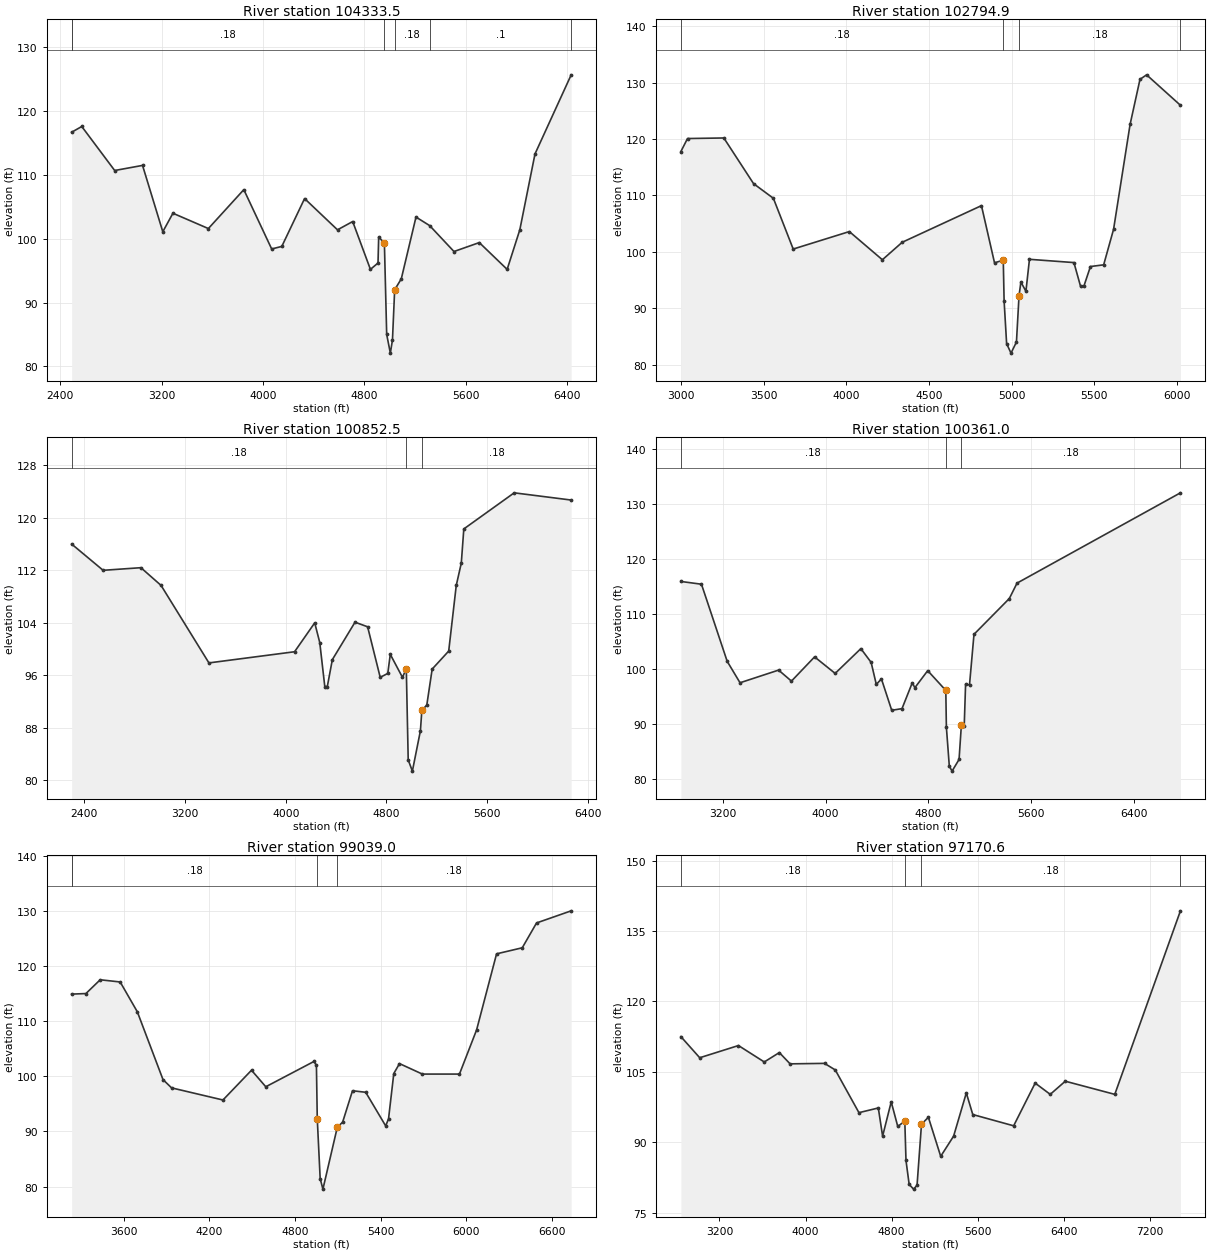
Type RM Length L Ch R = 1 ,104333.5,707.39,1538.6,1421.06
BEGIN DESCRIPTION:
Cross Section XS82
END DESCRIPTION:
XS GIS Cut Line= 2
    3083553.1978   13968148.2008    3082103.5214   13964478.3906
#Sta/Elev= 30
  2488.7   116.7  2568.7   117.6  2828.7   110.7  3048.7   111.5  3208.7   101.1
  3288.7     104  3568.7   101.6  3848.7   107.7  4068.7    98.4  4148.7    98.8
  4328.7   106.3  4588.7   101.4  4708.7   102.7  4848.7    95.2  4908.7    96.2
  4913.9  100.27    4959   99.33  4977.2      85  5006.1   82.07  5022.8   84.13
  5040.2      92  5092.6   93.72  5208.7   103.4  5316.8  102.06  5508.7      98
  5708.7    99.4  5928.7    95.2  6028.7   101.4  6148.7   113.3  6434.5   125.7
#Mann= 6 , 1 , 0
  2488.7      .2       0  2488.7     .18       0    4959     .06       0
  5040.2     .18       0  5316.8      .1       0  6434.5      .2       0
Bank Sta=4959,5040.2
XS Rating Curve= 0
Exp/Cntr=.3,.1

Type RM Length L Ch R = 1 ,102794.9,1487.32,1942.4,1126.24
BEGIN DESCRIPTION:
Cross Section XS81
END DESCRIPTION:
XS GIS Cut Line= 3
    3083890.4657   13968014.1006     3083573.473   13966242.3325
    3083837.0505   13965046.0961
#Sta/Elev= 30
    2998   117.8    3038   120.1    3258   120.2    3438   112.1    3558   109.5
    3678   100.5    4018   103.6    4218    98.6    4338   101.7  4817.9   108.2
    4897   98.06    4950   98.52  4955.1   91.31  4970.3   83.72  4996.9   82.04
  5029.8   84.01  5045.5   92.24  5056.8   94.65  5087.2   93.01  5108.6   98.68
  5377.9    98.1  5417.9    93.9  5437.9    93.9  5477.9    97.4  5557.9    97.7
  5617.9     104  5717.9   122.6  5777.9   130.6  5817.9   131.4  6022.8     126
#Mann= 4 , 1 , 0
    2998     .18       0    4950     .06       0  5045.5     .18       0
  6022.8      .2       0
Bank Sta=4950,5045.5
XS Rating Curve= 0
Exp/Cntr=.3,.1

Type RM Length L Ch R = 1 ,100852.5,413.77,491.5,642.07
BEGIN DESCRIPTION:
Cross Section XS80
END DESCRIPTION:
XS GIS Cut Line= 4
    3085563.0456   13968460.5304    3085327.2773   13968077.2376
    3085002.8742   13965836.8286    3084039.8025   13965035.9585
#Sta/Elev= 30
  2300.4     116  2550.4     112  2850.4   112.4  3010.4   109.7  3390.4    97.9
  4070.4    99.6  4230.4     104  4270.4     101  4310.4    94.3  4330.4    94.3
  4370.4    98.4  4550.4   104.1  4650.4   103.4  4750.4    95.7  4810.4    96.3
  4830.4    99.2  4927.1    95.7  4957.5   97.02  4972.7   83.13  5005.8   81.42
  5069.6   87.57    5081   90.67  5120.3   91.48    5163   96.96  5294.2    99.7
  5354.2   109.7  5394.2   113.1  5414.2   118.3  5814.2   123.8  6266.7   122.7
#Mann= 3 ,-1 , 0
  2300.4     .18       0  4957.5     .06       0    5081     .18       0
Bank Sta=4957.5,5081
XS Rating Curve= 0
Exp/Cntr=.3,.1

Type RM Length L Ch R = 1 ,100361.0,442.92,1322,764.4
BEGIN DESCRIPTION:
Cross Section XS79
END DESCRIPTION:
XS GIS Cut Line= 3
    3085614.2496   13967768.5413    3085418.5157   13965482.0127
    3085063.6998   13963930.9604
#Sta/Elev= 30
  2874.2   115.9  3034.2   115.4  3234.2   101.4  3334.2    97.5  3634.2    99.8
  3734.2    97.8  3914.2   102.2  4074.2    99.2  4274.2   103.7  4354.2   101.2
  4394.2    97.2  4434.2    98.2  4514.2    92.5  4594.2    92.8  4674.2    97.5
  4694.2    96.6  4794.2    99.7    4935   96.11  4939.4   89.44  4962.2   82.36
  4983.6   81.45  5038.1   83.57  5056.3   89.91  5078.1   89.56  5088.9   97.23
  5119.3    97.1  5154.2   106.3  5429.1   112.8  5489.1   115.6  6760.2     132
#Mann= 4 , 1 , 0
  2874.2     .18       0    4935     .06       0  5056.3     .18       0
  6760.2      .2       0
Bank Sta=4935,5056.3
XS Rating Curve= 0
Exp/Cntr=.3,.1

Type RM Length L Ch R = 1 ,99039.0 ,1291.15,1868.4,1234.85
BEGIN DESCRIPTION:
Cross Section XS78
END DESCRIPTION:
XS GIS Cut Line= 3
    3085773.3316    13968016.412    3086118.0099   13965786.1406
    3086371.4498    13964569.629
#Sta/Elev= 30
  3235.4   114.9  3335.4     115  3435.4   117.5  3575.4   117.1  3695.4   111.7
  3875.4    99.4  3935.4    97.9  4295.4    95.7  4495.4   101.1  4595.4    98.1
  4932.9  102.69  4950.1  101.99  4956.1   92.27  4976.4   81.45  4995.7   79.54
  5096.5   90.77  5133.5   91.67  5202.9   97.38  5295.4    97.1  5435.4      91
  5455.4    92.3  5492.1   100.5  5532.1   102.3  5692.1   100.4  5952.1   100.4
  6072.1   108.4  6212.1   122.2  6392.1   123.3  6492.1   127.8  6734.8     130
#Mann= 4 , 1 , 0
  3235.4      .2       0  3235.4     .18       0  4956.1     .06       0
  5096.5     .18       0
Bank Sta=4956.1,5096.5
XS Rating Curve= 0
Exp/Cntr=.3,.1

Type RM Length L Ch R = 1 ,97170.6 ,1383.3,1867,1632.84
BEGIN DESCRIPTION:
Cross Section XS77
END DESCRIPTION:
XS GIS Cut Line= 4
    3087053.1833   13968542.8627    3087081.0816   13968209.0264
    3087364.9343   13966009.1678    3087456.1727   13963920.8228
#Sta/Elev= 30
  2841.7   112.5  3016.7     108  3376.7   110.6  3616.7   107.1  3756.7   109.1
  3856.7   106.7  4176.7   106.8  4276.7   105.4  4496.7    96.3  4676.7    97.3
  4716.7    91.3  4796.7    98.6  4857.6   93.36    4923   94.51    4934   86.12
  4963.6      81  5004.9   80.01  5036.9   80.84  5078.1   93.84  5142.1   95.32
  5256.7      87  5376.7    91.3  5494.8   100.5  5554.8    95.9  5934.8    93.5
  6134.8   102.6  6274.8   100.2  6414.8     103  6874.8   100.2  7485.1   139.3
#Mann= 4 ,-1 , 0
  2841.7     .18       0    4923     .06       0  5078.1     .18       0
  7485.1      .2       0
Bank Sta=4923,5078.1
XS Rating Curve= 0
Exp/Cntr=.3,.1