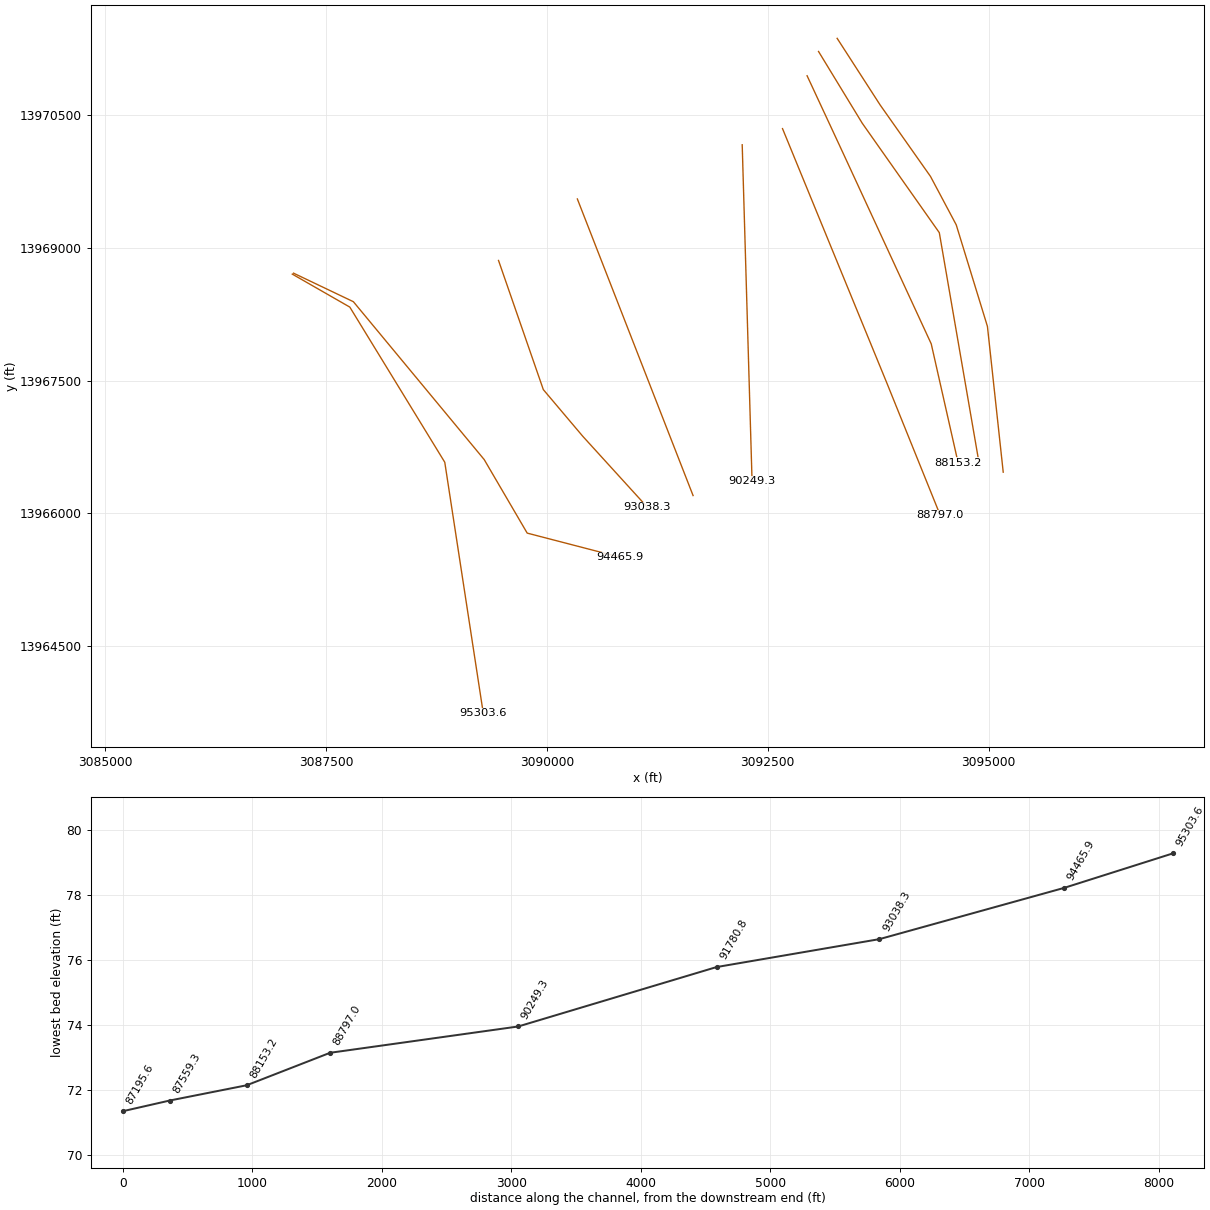
HEC-RAS study J100-00-00.prj: J100-00-00

--- J100-00-00.g01 (geometry) --- (continued)

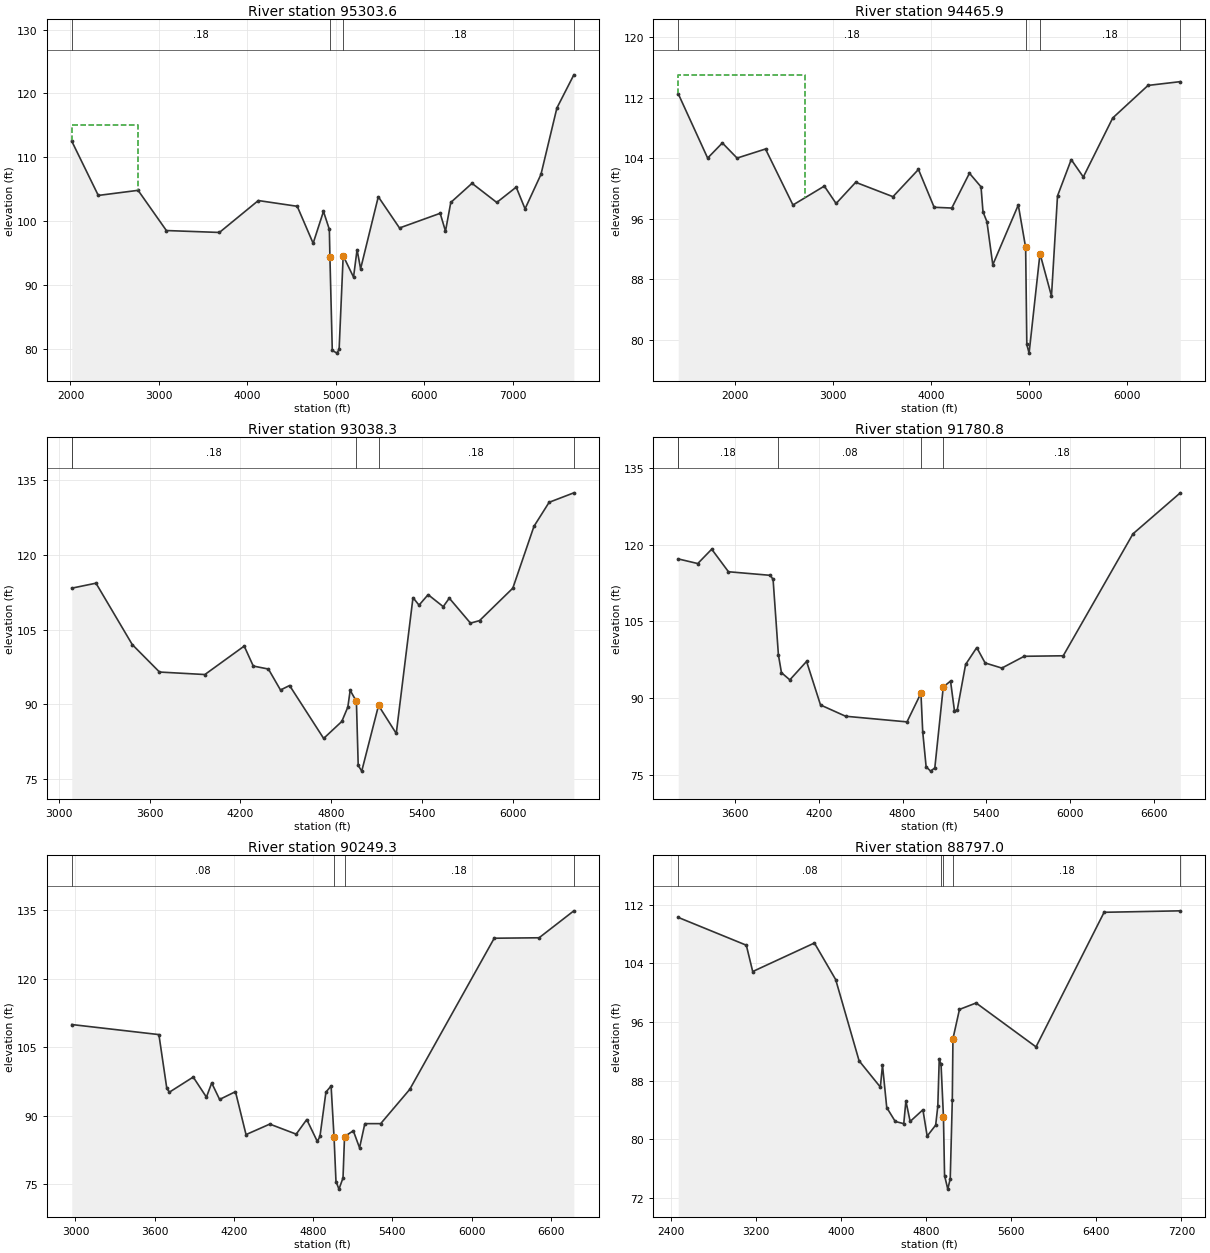
Type RM Length L Ch R = 1 ,95303.6 ,355.5,837.7,818.18
BEGIN DESCRIPTION:
Cross Section XS76
END DESCRIPTION:
XS GIS Cut Line= 4
       3087119.6   13968703.3833    3087770.4382   13968330.6775
    3088845.0235   13966576.8732    3089280.9402    13963738.346
#Sta/Elev= 30
  2014.5   112.5  2314.5     104  2764.5   104.8  3084.5    98.5  3684.5    98.2
  4124.5   103.2  4564.5   102.3  4744.5    96.5  4861.3   101.5  4927.7   98.68
  4934.1   94.42    4961   79.71  5013.7   79.29  5038.3   79.89  5084.3   94.54
  5201.3    91.2  5241.3    95.5  5281.3    92.5  5481.3   103.8  5721.3    98.9
  6181.3   101.2  6241.3    98.4  6301.3   102.9  6541.3   105.9  6821.3   102.9
  7041.3   105.3  7141.3   101.9  7321.3   107.3  7501.3   117.7  7693.1   122.9
#Mann= 4 ,-1 , 0
  2014.5     .18       0  4934.1     .06       0  5084.3     .18       0
  7693.1      .2       0
#XS Ineff= 2 , 0
       0  2764.5     115               0
Permanent Ineff=
       F       F
Bank Sta=4934.1,5084.3
XS Rating Curve= 0
Exp/Cntr=.3,.1

Type RM Length L Ch R = 1 ,94465.9 ,1104.59,1427.6,1289.16
BEGIN DESCRIPTION:
Cross Section XS75
END DESCRIPTION:
XS GIS Cut Line= 5
    3087133.9403   13968714.1572    3087810.9886   13968391.5031
    3089291.0778    13966607.286    3089777.6824    13965776.003
    3090831.9925   13965502.2879
#Sta/Elev= 30
  1424.4   112.5  1724.4     104  1874.4     106  2024.4     104  2314.4   105.2
  2594.4    97.8  2914.4   100.3  3034.4      98  3234.4   100.8  3614.4    98.9
  3874.4   102.5  4034.4    97.5  4214.4    97.4  4394.4     102  4512.6   100.2
  4532.6    96.9  4572.6    95.6  4632.6    89.9  4892.6    97.8  4967.6    92.2
  4979.6   79.37  5002.8   78.23  5113.9   91.38  5231.1   85.77  5292.6      99
  5432.6   103.8  5555.8   101.5  5855.8   109.3  6215.8   113.6  6545.1   114.1
#Mann= 4 ,-1 , 0
  1424.4     .18       0  4967.6     .06       0  5113.9     .18       0
  6545.1      .2       0
#XS Ineff= 2 , 0
       0  2717.4     115               0
Permanent Ineff=
       F       F
Bank Sta=4967.6,5113.9
XS Rating Curve= 0
Exp/Cntr=.3,.1

Type RM Length L Ch R = 1 ,93038.3 ,1197.15,1257.5,962.59
BEGIN DESCRIPTION:
Cross Section XS74
END DESCRIPTION:
XS GIS Cut Line= 4
    3089453.2793   13968857.8326    3089960.1592   13967398.0186
    3090406.2135   13966870.8635    3091136.1205   13966069.9934
#Sta/Elev= 30
  3085.8   113.3  3245.8   114.3  3485.8     102  3665.8    96.5  3965.8      96
  4225.8   101.7  4285.8    97.7  4385.8    97.1  4465.8    92.9  4525.8    93.8
  4751.1    83.2  4871.1    86.6  4911.1    89.5  4926.4   92.84  4967.6   90.62
  4979.6   77.79  5002.8   76.65  5113.9    89.8  5231.1   84.19  5341.7   111.4
  5381.7   109.9  5441.7     112  5541.7   109.6  5581.7   111.3  5721.7   106.3
  5781.7   106.8  6001.7   113.3  6141.7   125.7  6241.7   130.5  6405.2   132.4
#Mann= 5 , 1 , 0
  3085.8      .2       0  3085.8     .18       0  4967.6     .06       0
  5113.9     .18       0  6405.2      .2       0
Bank Sta=4967.6,5113.9
XS Rating Curve= 0
Exp/Cntr=.3,.1

Type RM Length L Ch R = 1 ,91780.8 ,1518.56,1531.5,1306.83
BEGIN DESCRIPTION:
Cross Section XS73
END DESCRIPTION:
XS GIS Cut Line= 2
    3090345.2897   13969553.0384    3091654.6753    13966200.344
#Sta/Elev= 30
  3191.8   117.2  3331.8   116.3  3431.8   119.1  3551.8   114.7  3851.8     114
  3871.8   113.2  3909.9   98.48  3931.8      95  3991.8    93.6  4111.8    97.2
  4211.8    88.7  4391.8    86.5  4831.8    85.4  4931.7      91  4944.4   83.49
  4968.9   76.63  5001.3   75.79  5031.2   76.42  5091.9   92.22  5143.9   93.36
  5171.8    87.6  5191.8    87.7  5251.8    96.6  5331.8    99.9  5391.8    96.9
  5511.8    95.9  5671.8    98.2  5951.8    98.3  6451.8   122.1  6791.1   130.1
#Mann= 6 , 1 , 0
  3191.8      .2       0  3191.8     .18       0  3909.9     .08       0
  4931.7     .06       0  5091.9     .18       0  6791.1      .2       0
Bank Sta=4931.7,5091.9
XS Rating Curve= 0
Exp/Cntr=.3,.1

Type RM Length L Ch R = 1 ,90249.3 ,1070.56,1452.3,1589.17
BEGIN DESCRIPTION:
Cross Section XS72
END DESCRIPTION:
XS GIS Cut Line= 2
    3092210.7058   13970165.5826    3092322.2193   13966363.9837
#Sta/Elev= 30
  2971.9     110  3631.9   107.8  3691.9      96  3711.9    95.2  3891.9    98.5
  3991.9    94.1  4031.9    97.2  4091.9    93.6  4211.9    95.3  4291.9    85.9
  4471.9    88.2  4671.9      86  4751.9    89.2  4831.9    84.4  4851.9    85.5
  4897.2   95.21  4936.3   96.55  4958.7   85.28  4973.3   75.62    4996   73.96
  5026.6   76.42  5038.1   85.48  5104.6   86.73  5151.9      83  5191.9    88.3
  5311.9    88.3  5531.9    95.8  6171.9   128.9  6511.9     129  6775.1   134.9
#Mann= 4 ,-1 , 0
  2971.9     .08       0  4958.7     .06       0  5038.1     .18       0
  6775.1      .2       0
Bank Sta=4958.7,5038.1
XS Rating Curve= 0
Exp/Cntr=.3,.1

Type RM Length L Ch R = 1 ,88797.0 ,617.18,643.8,607.4
BEGIN DESCRIPTION:
Cross Section XS71
Ineffective at Sta 6600 based on topo downstream of the cross section
END DESCRIPTION:
XS GIS Cut Line= 3
    3092666.8976   13970348.0594    3093852.9965   13967458.8442
    3094451.1147    13965978.755
#Sta/Elev= 30
  2469.5   110.3  3109.5   106.5  3169.5   102.9  3749.5   106.8  3949.5   101.8
  4169.5    90.7  4369.5    87.1  4389.5    90.1  4429.5    84.3  4509.5    82.4
  4589.5    82.1  4609.5    85.2  4649.5    82.4  4769.5      84  4809.5    80.4
  4889.5    81.9  4909.5    84.5  4922.9   90.89    4940   90.22  4962.6   83.01
    4973   75.01  5003.3   73.15  5026.4   74.58  5045.8   85.34  5051.8   93.71
  5113.1   97.72  5269.5    98.6  5832.7    92.6  6472.7     111  7189.1   111.2
#Mann= 5 ,-1 , 0
  2469.5     .08       0    4940     .18       0  4962.6     .06       0
  5051.8     .18       0  7189.1      .2       0
#XS Ineff= 2 , 0
       0                    6600       0     111
Permanent Ineff=
       F       F
Bank Sta=4962.6,5051.8
XS Rating Curve= 0
Exp/Cntr=.3,.1

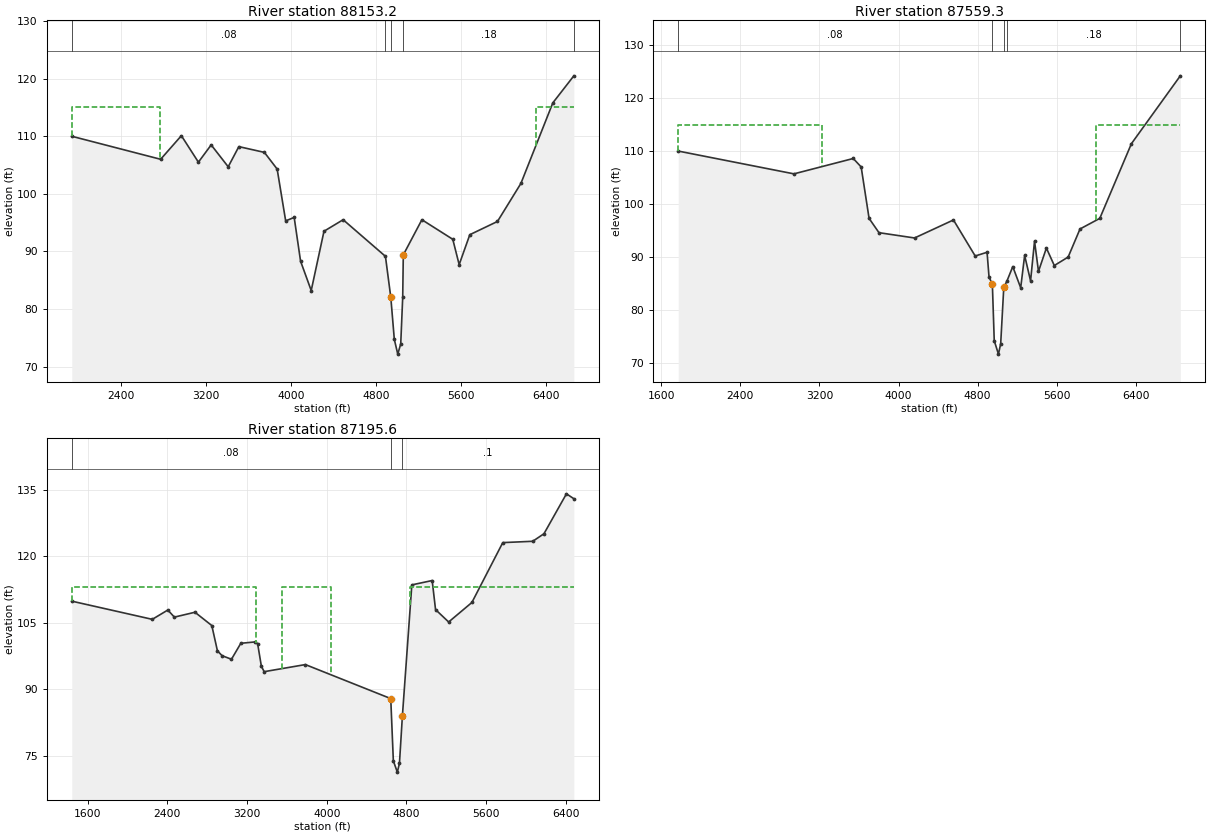
Type RM Length L Ch R = 1 ,88153.2 ,621.8,593.9,341.94
BEGIN DESCRIPTION:
Cross Section XS70
END DESCRIPTION:
XS GIS Cut Line= 4
    3092944.9757   13970945.6357    3093346.1166   13970084.4818
    3094349.7388    13967915.036    3094653.7523   13966571.4755
#Sta/Elev= 30
  1939.1     110  2774.1     106  2969.1   110.1  3129.1   105.5  3249.1   108.5
  3409.1   104.7  3509.1   108.2  3749.1   107.2  3869.1   104.3  3949.1    95.3
  4029.1    95.9  4089.1    88.3  4189.1    83.2  4309.1    93.5  4489.1    95.5
  4886.6   89.14  4937.1   81.99    4970   74.71  5002.5   72.15  5030.3   73.93
  5048.9   82.05  5054.4   89.39  5229.1    95.5  5519.4    92.1  5579.4    87.7
  5679.4    92.9  5939.4    95.2  6159.4   101.8  6459.4   115.8    6657   120.5
#Mann= 5 ,-1 , 0
  1939.1     .08       0  4886.6     .18       0  4937.1     .06       0
  5054.4     .18       0    6657      .2       0
#XS Ineff= 2 , 0
       0    2770     115    6300       0     115
Permanent Ineff=
       F       F
Bank Sta=4937.1,5054.4
XS Rating Curve= 0
Exp/Cntr=.3,.1

Type RM Length L Ch R = 1 ,87559.3 ,209.66,363.7,350.37
BEGIN DESCRIPTION:
Cross Section XS69-Bridge 3- Con
END DESCRIPTION:
XS GIS Cut Line= 4
    3093074.4723   13971219.9337    3093569.1438   13970408.8849
    3094440.9771   13969172.0981    3094886.1613   13966595.9397
#Sta/Elev= 30
  1772.1     110  2942.1   105.7  3542.1   108.6  3622.1     107  3702.1    97.3
  3802.1    94.6  4162.1    93.6  4555.3      97  4775.3    90.2  4895.3    90.9
  4915.3    86.2  4948.8   84.93  4967.9   74.21  5010.4   71.68  5033.1   73.65
  5064.4    84.3  5095.6   85.44  5155.3    88.2  5235.3    84.2  5275.3    90.3
  5335.3    85.5  5375.3      93  5415.3    87.3  5495.3    91.7  5575.3    88.4
  5715.3      90  5835.3    95.3  6035.3    97.3  6355.3   111.4  6849.6   124.2
#Mann= 5 ,-1 , 0
  1772.1     .08       0  4948.8     .06       0  5064.4     .08       0
  5095.6     .18       0  6849.6      .2       0
#XS Ineff= 2 , 0
       0    3230     115    6000       0     115
Permanent Ineff=
       F       F
Bank Sta=4948.8,5064.4
XS Rating Curve= 0
Exp/Cntr=.5,.3

Type RM Length L Ch R = 1 ,87195.6 ,513.8,513.8,513.8
BEGIN DESCRIPTION:
Upstream Section of IH-45
END DESCRIPTION:
XS GIS Cut Line= 6
      3093285.06     13971368.54      3093771.23     13970615.91
      3094341.54     13969807.19      3094632.29     13969261.14
      3094985.64     13968112.36      3095164.28      13966464.8
#Sta/Elev= 30
1440.173   109.92248.309   105.82404.298   107.92470.076   106.32676.809   107.4
2845.953   104.42902.335    98.72949.319    97.63043.289    96.83137.258   100.4
3277.836   100.73306.027   100.33343.614    95.23371.805      94 3785.27    95.6
 4642.27   87.934668.299   73.884708.236   71.354729.567   73.324758.979   83.97
4853.888  113.575058.177  114.555091.913     108 5223.47   105.25456.701   109.6
5766.799   123.16067.501   123.46180.264   125.16405.791   134.16480.214     133
#Mann= 3 ,-1 , 0
1440.173     .08       0 4642.27     .06       04758.979      .1       0
#XS Ineff= 3 ,-1
3548.2794040.678     1134839.4176577.848     1131440.1733290.803     113
Permanent Ineff=
       F       F       F
Bank Sta=4642.27,4758.979
XS Rating Curve= 0
Skew Angle= 20
Exp/Cntr=.5,.3