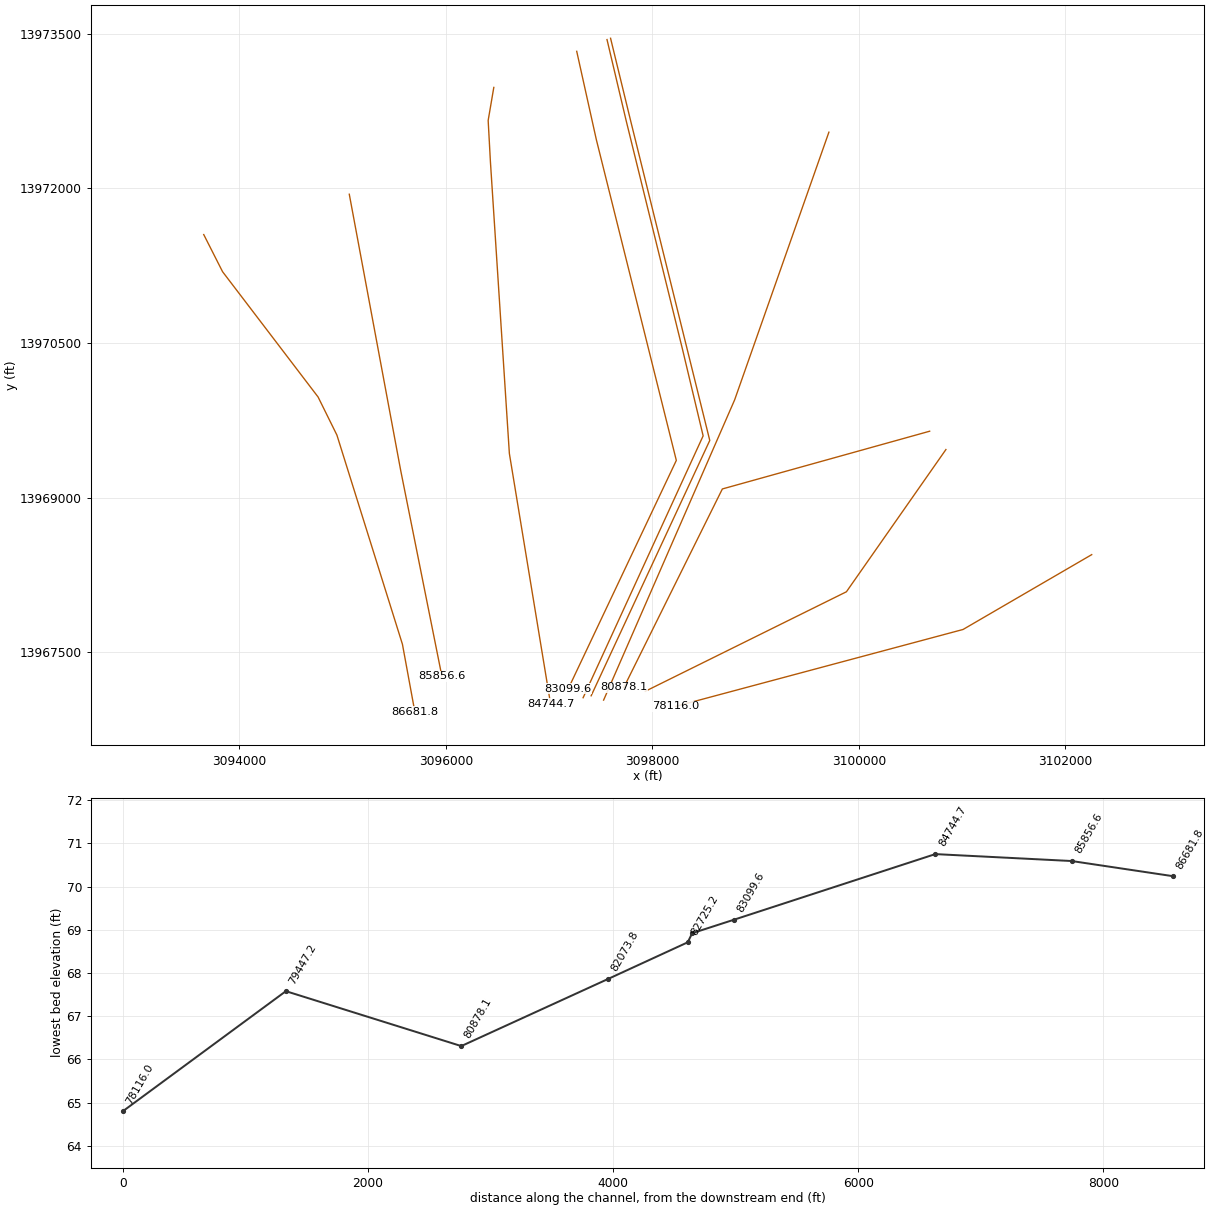
HEC-RAS study J100-00-00.prj: J100-00-00

--- J100-00-00.g01 (geometry) --- (continued)

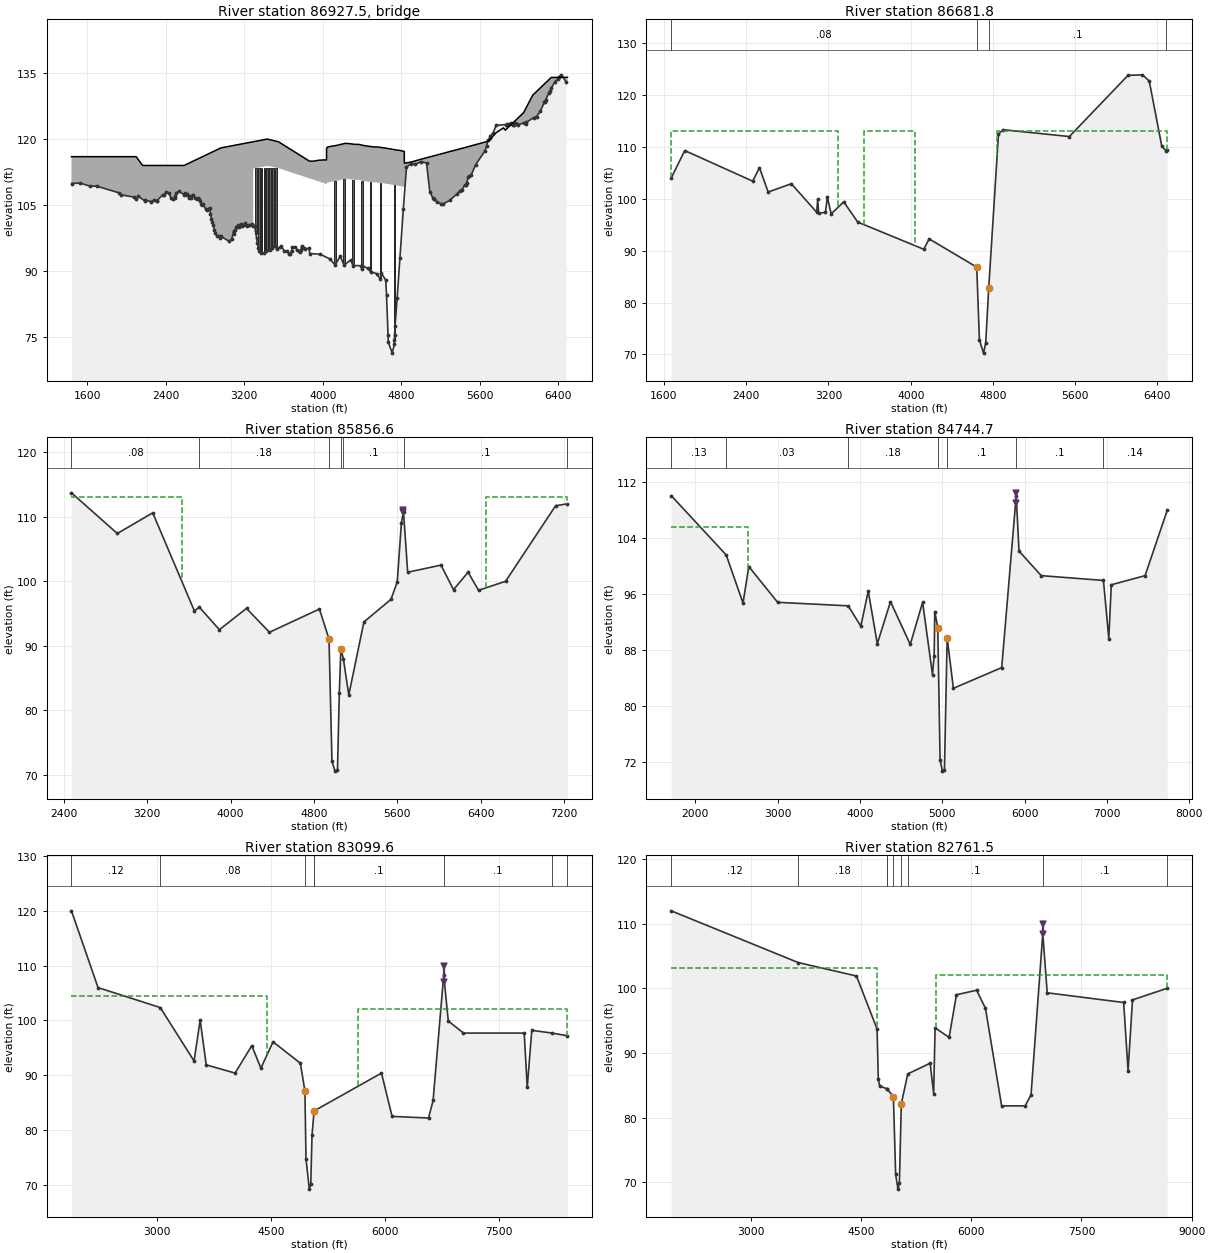
Type RM Length L Ch R = 3 ,86927.5 ,,,
BEGIN DESCRIPTION:
INTER-STATE 45
Structure ID: J100-00-00-03
Circular piers, twin-cylinder piers without diaphragm
END DESCRIPTION:
Node Name=IH 45
Bridge Culvert--1,0,-1,-1, 0
Deck Dist Width WeirC Skew NumUp NumDn MinLoCord MaxHiCord MaxSubmerge Is_Ogee
10,41.1,2.6,20, 125, 125, , , .95, 0, 1,1,,
 1437.731721.5172097.3942163.1722586.0342773.9732961.9113291.2173291.217 3434.52
3549.1633549.1633864.4863868.1513909.0273954.1333973.8664000.6474038.4234038.526
4038.6024038.7054038.7994038.9024047.4444073.7564076.1054095.3694126.3784141.319
4179.377 4187.744216.6834233.8794279.0794286.5964306.8934324.8414370.792 4395.13
4397.1044404.3394415.9914457.7144462.9764487.4084509.3974550.7434555.7244587.204
 4597.074600.735 4642.27 4646.784650.351 4665.014668.2994693.5774708.2364729.567
4730.601 4732.014737.366 4738.874758.9794784.9154787.076  4794.54821.2814830.302
4831.6084831.7114831.815 4831.894831.9944832.0874853.8884895.0474897.3024941.374
4941.4684985.2575003.8635058.1775161.2625165.3965202.9845240.5725259.3665315.747
5353.3355372.1285390.9225409.716 5428.515437.0625447.3045541.2735578.861 5672.83
5691.6245765.9545766.7995841.9755859.9235860.7695953.8935954.7385973.532 6011.12
6047.8626048.7086067.5016094.8466105.0896141.8316199.0586217.852  6235.86236.646
6255.4396262.487 6329.776487.0746495.062
     116     116     116     114     114     116     118  119.39  119.39     120
  119.38  119.38  114.98  114.98  114.98  115.18  115.21  115.25  115.26  115.26
  115.26  115.26  117.86  117.86  118.18   118.3  118.31  118.39   118.5  118.56
  118.76  118.81  118.95  119.03  118.94  118.92  118.86  118.81  118.78  118.65
  118.64   118.6  118.54   118.4  118.38  118.31  118.24   118.2   118.2  118.12
  118.09  118.08  117.94  117.92  117.91  117.85  117.84  117.75  117.69   117.6
  117.59  117.59  117.57  117.56   117.5  117.43  117.42  117.38  117.23  117.18
  117.12  117.12  114.52  114.52  114.52  114.52   114.6  114.75  114.76  115.03
  115.03  115.32  115.43  115.75  116.36  116.39  116.61  116.83  116.95  117.28
   117.5  117.61  117.73  117.84  117.95     118  118.06  118.63  118.86  119.43
  119.55   121.4  121.43  122.53  122.05  122.03     124  124.02  124.42  125.22
     126  126.04  126.84     128  128.44     130  131.22  131.62     132  132.02
  132.42  132.57     134  134.03  134.03
                                                                  113.29   113.9
  113.38
          109.79  109.79  109.79  110.11  110.23  110.24  110.32  110.43  110.49
  110.69  110.74  110.88  110.96  110.87  110.85  110.79  110.74  110.71  110.58
  110.57  110.53  110.47  110.33  110.31  110.24  110.17  110.13  110.13  110.05
  110.02  110.01  109.87  109.85  109.84  109.78  109.77  109.68  109.62  109.53
  109.52  109.52   109.5  109.49  109.43  109.36  109.35  109.31  109.16  109.11
  109.05  109.05  109.05  109.05
                                                                                
                                                                                
                                                                                
                                                                                
                                        
 1437.731721.5172097.3942163.1722586.0342773.9732961.9113291.2173291.217 3434.52
3549.1633549.1633864.4863868.1513909.0273954.1333973.8664000.6474038.4234038.526
4038.6024038.7054038.7994038.9024047.4444073.7564076.1054095.3694126.3784141.319
4179.377 4187.744216.6834233.8794279.0794286.5964306.8934324.8414370.792 4395.13
4397.1044404.3394415.9914457.7144462.9764487.4084509.3974550.7434555.7244587.204
 4597.074600.735 4642.27 4646.784650.351 4665.014668.2994693.5774708.2364729.567
4730.601 4732.014737.366 4738.874758.9794784.9154787.076  4794.54821.2814830.302
4831.6084831.7114831.815 4831.894831.9944832.0874853.8884895.0474897.3024941.374
4941.4684985.2575003.8635058.1775161.2625165.3965202.9845240.5725259.3665315.747
5353.3355372.1285390.9225409.716 5428.515437.0625447.3045541.2735578.861 5672.83
5691.6245765.9545766.7995841.9755859.9235860.7695953.8935954.7385973.532 6011.12
6047.8626048.7086067.5016094.8466105.0896141.8316199.0586217.852  6235.86236.646
6255.4396262.487 6329.776487.0746495.062
     116     116     116     114     114     116     118  119.39  119.39     120
  119.38  119.38  114.98  114.98  114.98  115.18  115.21  115.25  115.26  115.26
  115.26  115.26  117.86  117.86  118.18   118.3  118.31  118.39   118.5  118.56
  118.76  118.81  118.95  119.03  118.94  118.92  118.86  118.81  118.78  118.65
  118.64   118.6  118.54   118.4  118.38  118.31  118.24   118.2   118.2  118.12
  118.09  118.08  117.94  117.92  117.91  117.85  117.84  117.75  117.69   117.6
  117.59  117.59  117.57  117.56   117.5  117.43  117.42  117.38  117.23  117.18
  117.12  117.12  114.52  114.52  114.52  114.52   114.6  114.75  114.76  115.03
  115.03  115.32  115.43  115.75  116.36  116.39  116.61  116.83  116.95  117.28
   117.5  117.61  117.73  117.84  117.95     118  118.06  118.63  118.86  119.43
  119.55   121.4  121.43  122.53  122.05  122.03     124  124.02  124.42  125.22
     126  126.04  126.84     128  128.44     130  131.22  131.62     132  132.02
  132.42  132.57     134  134.03  134.03
                                                                  113.29   113.9
  113.38
          109.79  109.79  109.79  110.11  110.23  110.24  110.32  110.43  110.49
  110.69  110.74  110.88  110.96  110.87  110.85  110.79  110.74  110.71  110.58
  110.57  110.53  110.47  110.33  110.31  110.24  110.17  110.13  110.13  110.05
  110.02  110.01  109.87  109.85  109.84  109.78  109.77  109.68  109.62  109.53
  109.52  109.52   109.5  109.49  109.43  109.36  109.35  109.31  109.16  109.11
  109.05  109.05  109.05  109.05
                                                                                
                                                                                
                                                                                
                                                                                
                                        
Pier Skew= 20
Pier Skew, UpSta & Num, DnSta & Num=  ,3319.878, 4 ,3319.878, 4 , 3 , 3 , 0 ,,
   15.94   15.94   16.88   16.88
      95     109     109   113.5
   15.94   15.94   16.88   16.88
      95     109     109   113.5
Pier Skew, UpSta & Num, DnSta & Num=  ,3348.538, 4 ,3348.538, 4 , 3 , 3 , 0 ,,
   15.94   15.94   16.88   16.88
      95     109     109   113.5
   15.94   15.94   16.88   16.88
      95     109     109   113.5
Pier Skew, UpSta & Num, DnSta & Num=  ,3377.199, 4 ,3377.199, 4 , 3 , 3 , 0 ,,
   15.94   15.94   16.88   16.88
      95     109     109   113.5
   15.94   15.94   16.88   16.88
      95     109     109   113.5
Pier Skew, UpSta & Num, DnSta & Num=  ,3405.859, 4 ,3405.859, 4 , 3 , 3 , 0 ,,
   15.94   15.94   16.88   16.88
      95     109     109   113.5
   15.94   15.94   16.88   16.88
      95     109     109   113.5
Pier Skew, UpSta & Num, DnSta & Num=  ,3434.52, 4 ,3434.52, 4 , 3 , 3 , 0 ,,
   15.94   15.94   16.88   16.88
      95     109     109   113.5
   15.94   15.94   16.88   16.88
      95     109     109   113.5
Pier Skew, UpSta & Num, DnSta & Num=  ,3463.181, 4 ,3463.181, 4 , 3 , 3 , 0 ,,
   15.94   15.94   16.88   16.88
      95     109     109   113.5
   15.94   15.94   16.88   16.88
      95     109     109   113.5
Pier Skew, UpSta & Num, DnSta & Num=  ,3491.841, 4 ,3491.841, 4 , 3 , 3 , 0 ,,
   15.94   15.94   16.88   16.88
      95     109     109   113.5
   15.94   15.94   16.88   16.88
      95     109     109   113.5
Pier Skew, UpSta & Num, DnSta & Num=  ,3520.502, 4 ,3520.502, 4 , 3 , 3 , 0 ,,
   15.94   15.94   16.88   16.88
      95     109     109   113.5
   15.94   15.94   16.88   16.88
      95     109     109   113.5
Pier Skew, UpSta & Num, DnSta & Num=  ,4126.378, 2 ,4126.378, 2 , 0 , 0 , 0 ,,
   16.88   16.88
   90.45  111.44
   16.88   16.88
    89.3  110.29
Pier Skew, UpSta & Num, DnSta & Num=  ,4216.683, 2 ,4216.683, 2 , 0 , 0 , 0 ,,
   16.88   16.88
   90.39  111.89
   16.88   16.88
   89.24  110.74
Pier Skew, UpSta & Num, DnSta & Num=  ,4306.893, 2 ,4306.893, 2 , 0 , 0 , 0 ,,
   16.88   16.88
   90.29  111.79
   16.88   16.88
   89.14  110.64
Pier Skew, UpSta & Num, DnSta & Num=  ,4397.104, 2 ,4397.104, 2 , 0 , 0 , 0 ,,
   16.88   16.88
   89.68  111.58
   16.88   16.88
   88.53  110.43
Pier Skew, UpSta & Num, DnSta & Num=  ,4487.408, 2 ,4487.408, 2 , 0 , 0 , 0 ,,
   16.88   16.88
   88.86  111.24
   16.88   16.88
   87.71  110.09
Pier Skew, UpSta & Num, DnSta & Num=  ,4587.204, 2 ,4587.204, 2 , 0 , 0 , 0 ,,
   16.88   16.88
   87.25  111.05
   16.88   16.88
    86.1   109.9
Pier Skew, UpSta & Num, DnSta & Num=  ,4730.601, 2 ,4730.601, 2 , 0 , 0 , 0 ,,
   16.88   16.88
   72.32  110.53
   16.88   16.88
   71.17  109.38
Abutment Skew #Up #Dn= , 2 , 2
3291.2173322.697
  112.29   95.54
3291.2173322.697
  112.29   95.54
Abutment Skew #Up #Dn= , 2 , 2
3515.3343549.163
   94.38  112.38
3515.3343549.163
   94.38  112.38
Abutment Skew #Up #Dn= , 2 , 2
4038.5174076.105
  109.79   92.72
4038.5174076.105
  108.64   91.57
Abutment Skew #Up #Dn= , 2 , 2
  4794.54832.078
   95.35  109.05
  4794.54832.078
    94.2   107.9
BR Coef= 1 , 1 , 1 ,1.05, 0 ,,,.8,0,1.2,0,
WSPro=,,,, 1 ,,,, 0 ,,,, 0 ,,,,-1 ,-1 ,-1 , 0 , 0 , 0 , 0 , 0
BR U #Sta/Elev= 190
1440.173   109.91524.745     1101628.111   109.3 1693.89   109.31919.416   107.8
1947.607   107.32079.164   106.82097.958   106.32116.752     107 2182.53     106
2191.927   106.12248.309   105.82282.138   106.12305.254  106.022310.328     106
 2366.71   107.32385.504   107.42404.298   107.92432.488   107.72451.282   106.6
2470.076   106.3 2488.87   106.52498.267     1072507.664   107.82535.854   108.1
2582.839   107.42592.236   107.7 2611.03   107.32620.427   107.62639.221   106.6
2648.618   107.12658.015   106.72676.809   107.42695.602   106.62714.396   106.4
2723.793   106.62742.587   106.42751.984     1062761.381   105.22770.778     105
2780.175   105.22808.365     1042817.762   103.92845.953   104.4 2855.35     103
2864.747   101.92874.144   101.12883.541   100.52892.938    99.42902.335    98.7
2921.129      982939.922      982949.319    97.62958.716    97.93043.289    96.8
3071.479    97.23090.273      99 3099.67    98.43109.067    99.43118.464     100
3127.861     1003137.258   100.43146.655   100.13156.052   100.23165.449   100.7
3174.845   100.33193.639   100.53212.057   100.93230.851   100.23240.248   100.4
3259.042   100.43277.836   100.73287.233   100.33306.027   100.33315.423    99.1
 3324.82    97.63334.217    96.33343.614    95.23353.011    94.63371.805      94
3399.996      94 3418.79    94.53465.774    94.73484.568    95.33512.759    95.6
3531.553    95.1 3569.14    95.43578.537    95.63606.728    94.63634.919    94.5
3653.713    93.9 3663.11    93.93681.904    94.63691.301    95.43719.491    95.5
3738.285    94.93757.079    94.63766.476    94.33775.873    94.7 3785.27    95.6
3793.351    95.53812.145    95.33821.542      953859.129    95.23868.151   93.99
3973.866   93.824073.756   92.754126.378   91.384179.377   93.384216.683   91.33
4286.596   92.574306.893   91.26 4395.13   91.214397.104    90.54404.339   91.25
4457.714   90.614487.408   89.844550.743   89.414587.204   88.17 4597.07   89.56
 4642.27   87.934650.351    84.6 4665.01   75.364668.299   73.884708.236   71.35
4729.567   73.324730.601   74.32 4732.01   75.364737.366   77.554758.979   83.97
4787.076   92.914821.281     1044853.888  113.574897.302  114.434941.468  114.23
5003.863  114.865058.177  114.555091.913     1085120.104   106.7  5129.5   106.4
5138.897   106.35167.088   105.6 5202.89  105.35 5223.47   105.25296.953   106.1
5372.128   107.65400.319   108.35419.113   108.55447.304   109.55456.701   109.6
5466.098     1105484.892   111.35494.289   111.65513.083   111.85560.067   114.2
5654.037   117.3 5672.83   118.55682.227   119.75701.021   120.25710.418   120.7
5738.609   121.45766.799   123.15870.166   123.35879.562   123.55898.356   123.4
 5917.15   123.65926.547   123.55935.944   123.15954.738   123.35964.135   123.6
5982.929   123.55992.326   123.26048.708   123.76067.501   123.46076.898   123.8
6152.074   124.96180.264   125.16217.852   126.3 6260.89  128.416262.487  128.49
6264.836   128.66274.233   128.96302.424   130.46321.218     1316330.615   131.6
6368.203     1336396.394   133.66405.791   134.16433.981   134.66480.214     133
BR U #Mann= 3
1440.173     .08 4642.27    .0554758.979      .1
BR D #Sta/Elev= 200
1670.116     104 1688.91   103.81698.307   103.31707.703   104.5  1717.1   106.5
1726.497   107.91735.894   108.41764.085     1091782.879     1091801.673   109.3
 1811.07     1091820.467   108.51829.864   107.7 1839.26   107.31848.657   107.3
1858.054   107.81867.451   108.11886.245   108.11914.436   107.81942.627   107.9
 1961.42   107.51980.214   107.71989.611     1082008.405   107.92036.596   108.3
2049.282   108.22058.679   108.12105.663   108.12143.251   107.72171.442   107.1
2190.236   106.6 2209.03   107.12256.014   106.52265.411   106.62274.808   106.4
2284.205   105.92289.091  105.742293.602   105.62312.396   105.62321.792   105.2
2340.586   104.92349.983     105 2359.38   105.42368.777   104.62387.571   104.3
2406.365   104.92415.762   104.82425.159   104.42443.953   104.12462.746   103.4
 2481.54   105.22500.334   105.92528.525     1062537.922   105.72547.319     105
2566.113   103.1 2575.51   102.52613.097   101.32622.494   101.32631.891   101.8
2641.288   101.32678.876   101.72707.067   100.92735.257   100.72744.654   100.7
2754.051   100.62763.448   100.72782.242   102.32801.036   102.3 2819.83   102.9
2838.624   102.92848.021   102.52857.417   101.72876.211   101.22895.005     101
2923.196    99.92932.593    99.8 2941.99    99.42972.718    98.92982.115    98.7
2991.511      993019.702    98.23029.099    98.13038.496    99.23047.893    99.5
 3057.29    97.83085.481    97.43094.878    99.93104.275    97.23123.068    97.9
3132.465    98.63151.259    97.63170.053    97.43188.847   100.33198.244    99.6
3207.641   100.13217.038      983226.435    97.13254.625    98.63264.022    98.9
3273.419    98.53282.816    98.2 3301.61    98.83329.801    98.63348.595    99.4
3357.991    98.23367.388    98.63386.182    97.33404.976    97.4 3423.77    96.6
3461.358    95.83484.944    95.53663.486    94.13691.677    94.23701.073      94
 3832.63    93.63860.821    93.13868.151   92.883973.866   92.714073.756   91.64
4126.378   90.274179.377   92.274216.683   90.224286.596   91.464306.893   90.15
 4395.13    90.14397.104   89.394404.339   90.144457.714    89.54487.408   88.73
4550.743    88.34587.204   87.06 4597.07   88.45 4642.27   86.824650.351   83.49
 4665.01   74.254668.299   72.774708.236   70.244729.567   72.214730.601   73.21
 4732.01   74.254737.366   76.444758.979   82.864787.076    91.84821.281  102.89
4853.888  112.464897.302  113.324941.468  113.125003.863  113.755058.177  113.44
5064.191   113.65092.382   113.15111.176   113.4 5129.97   113.15158.161   113.4
5176.955   113.15205.146   113.65214.542   113.65233.336   113.15308.512   112.7
  5346.1   112.95477.656   111.85515.244   112.15543.435     1125628.007   112.9
5703.183   114.2 5834.74   117.65869.508     1185935.287   119.15944.684   119.5
5963.478   119.56001.065   120.36010.462   120.86019.859   120.86029.256   121.2
6038.653   121.26066.844   122.46113.828   123.86142.019     1246151.416   123.7
6160.813   123.2 6170.21   122.56179.607   122.36189.004   122.56207.797   123.3
6254.782   123.96282.973   123.86301.767   123.66320.561   122.76329.958   121.6
6339.354   120.96395.736   115.26442.721   110.16452.118   109.46461.515   109.6
6470.912     1096480.309     1096487.074  109.226489.706   109.36495.062   109.4
BR D #Mann= 4
1670.116     .08 4642.27    .0554758.979      .16487.074      .2
BC Design=,, 0 ,, 0 ,,,,,,
BC HTab HWMax=134.03

Type RM Length L Ch R = 1 ,86681.8 ,886,825.2,560
BEGIN DESCRIPTION:
Downstream Section of IH-45
END DESCRIPTION:
XS GIS Cut Line= 6
      3093654.36     13971550.85      3093836.67      13971190.9
      3094762.26     13969975.48      3094944.57     13969606.18
      3095579.34     13967577.57      3095699.53     13966922.73
#Sta/Elev= 30
1670.116     1041801.673   109.32462.746   103.42528.525     1062613.097   101.3
2838.624   102.93085.481    97.43094.878    99.93104.275    97.23170.053    97.4
3188.847   100.33226.435    97.13348.595    99.43484.944    95.54126.378   90.27
4179.377   92.27 4642.27   86.824668.299   72.774708.236   70.244729.567   72.21
4758.979   82.864853.888  112.464897.302  113.325543.435     1126113.828   123.8
6254.782   123.96320.561   122.76442.721   110.16487.074  109.226495.062   109.4
#Mann= 4 ,-1 , 0
1670.116     .08       0 4642.27     .06       04758.979      .1       0
6487.074      .2       0
#XS Ineff= 3 ,-1
3548.2794040.678     1134839.4176577.848     1131670.1163290.803     113
Permanent Ineff=
       F       F       F
Bank Sta=4642.27,4758.979
XS Rating Curve= 0
Skew Angle= 20
Exp/Cntr=.5,.3

Type RM Length L Ch R = 1 ,85856.6 ,1347.76,1111.9,1063.39
BEGIN DESCRIPTION:
Cross Section XS68-Bridge 3- Exp
Northgate Development Levee at sta 5660.
END DESCRIPTION:
XS GIS Cut Line= 3
    3095064.3348   13971942.0659    3095562.8538   13969261.1417
    3095961.6689   13967267.0659
#Sta/Elev= 30
  2473.2   113.7  2913.2   107.4  3253.2   110.6  3653.2    95.4  3699.4      96
  3893.2    92.5  4153.2    95.8  4373.2    92.1  4853.2    95.7  4945.2   91.04
  4973.3   72.16  5002.4   70.59  5026.3   70.74  5044.2   82.75    5059   89.57
  5083.5   87.94  5134.9   82.39  5280.1    93.7  5540.1    97.2  5600.1    99.9
  5640.1   109.1  5660.1   110.8  5700.1   101.4  6020.1   102.5  6140.1    98.7
  6280.1   101.4  6380.1    98.6  6640.1     100  7120.1   111.7  7233.6     112
#Mann= 7 ,-1 , 0
  2473.2     .08       0  3699.4     .18       0  4945.2     .06       0
    5059     .18       0  5083.5      .1       0  5660.1      .1       0
  7233.6      .2       0
Levee=0,,,-1,5660,111,,
#XS Ineff= 2 , 0
       0    3530     113    6450       0     113
Permanent Ineff=
       F       F
Bank Sta=4945.2,5059
XS Rating Curve= 0
Exp/Cntr=.3,.1

Type RM Length L Ch R = 1 ,84744.7 ,1314.29,1645.1,1597.74
BEGIN DESCRIPTION:
Northgate Development Levee at sta 5890.
Cross Section XS67
END DESCRIPTION:
XS GIS Cut Line= 5
     3096464.456   13972977.9697     3096409.846   13972657.5907
    3096431.3792   13972261.5917    3096615.2827   13969427.3147
    3097014.0978   13967001.1891
#Sta/Elev= 30
  1709.6     110    2377  101.55  2581.2    94.7  2651.2    99.9  3001.2    94.8
    3858    94.3  4011.2    91.4  4101.2    96.4  4211.2    88.9  4371.2    94.9
  4611.2    88.8  4761.2    94.8  4881.2    84.5  4901.2    87.2  4908.8   93.48
  4945.2    91.2  4973.3   72.32  5002.4   70.75  5026.3    70.9    5059   89.73
  5134.9   82.55  5721.4    85.5  5897.4     110  5931.4   102.1  6201.4    98.6
  6956.3   97.92  7021.4    89.6  7051.4    97.3  7461.4    98.6  7730.1   107.9
#Mann= 7 ,-1 , 0
  1709.6     .13       0    2377     .03       0    3858     .18       0
  4945.2     .06       0    5059      .1       0  5897.4      .1       0
  6956.3     .14       0
Levee=0,,,-1,5890,110.4,,
#XS Ineff= 2 , 0
       0    2642   105.5               0
Permanent Ineff=
       F       F
Bank Sta=4945.2,5059
XS Rating Curve= 0
Exp/Cntr=.3,.1

Type RM Length L Ch R = 1 ,83099.6 ,268.71,338.15,94.73
BEGIN DESCRIPTION:
Northgate Development Levee at sta 6775.
Cross Section XS66-Bridge2-Con
END DESCRIPTION:
XS GIS Cut Line= 4
    3097267.7385   13973327.8741    3097457.2258   13972473.8194
    3098232.6997   13969360.8455    3097185.7871    13967146.382
#Sta/Elev= 30
  1871.2     120  2221.2     106  3041.1  102.35  3486.2    92.6  3566.2   100.1
  3646.2    91.9  4026.2    90.4  4246.2    95.4  4366.2    91.3  4526.2    96.1
  4886.2    92.2  4946.1   87.14  4960.2    74.8    5004   69.23  5023.5   70.23
  5039.6   79.09  5066.1   83.42  5067.4    83.5  5954.3    90.4  6094.3    82.5
  6574.3    82.2  6634.3    85.4  6774.3   108.3  6834.3    99.9  7034.3    97.7
  7834.3    97.7  7874.3    87.8  7934.3    98.2  8203.5    97.7  8403.8    97.2
#Mann= 8 ,-1 , 0
  1871.2     .12       0  3041.1     .08       0  4946.1     .06       0
  5066.1     .08       0  5067.4      .1       0  6774.3      .1       0
  8203.5     .14       0  8403.8      .2       0
Levee=0,,,-1,6784,110,,
#XS Ineff= 2 , 0
       0    4445   104.5    5650       0     102
Permanent Ineff=
       F       F
Bank Sta=4946.1,5066.1
XS Rating Curve= 0
Exp/Cntr=.5,.3

Type RM Length L Ch R = 1 ,82761.5 ,36.3,36.3,36.3
BEGIN DESCRIPTION:
Upstream Section of Union Pacific Railroad
Northgate Levee at station 6975
END DESCRIPTION:
XS GIS Cut Line= 5
      3097561.14   13973441.9222    3097747.3822   13972652.5966
    3098291.9065   13970440.6056     3098492.453   13969598.9179
    3097329.6757    13967059.334
#Sta/Elev= 30
  1919.5     112  3644.5     104  4439.5  101.91  4719.5   93.71  4736.4   85.96
  4755.5   84.87  4856.3   84.45  4856.5   84.44  4941.9   83.24  4972.4   71.22
    5004   68.92  5023.5   69.92  5049.6   82.14  5136.8   86.75  5441.4   88.41
  5489.4   83.72    5509   93.89  5699.5   92.41  5799.5   99.01  6074.1   99.71
  6194.1   96.91  6414.1   81.81  6734.1   81.81  6814.1   83.51  6974.1   108.5
  7034.1   99.31  8074.1   97.81  8134.1   87.21  8194.1   98.21  8666.3  100.01
#Mann= 9 ,-1 , 0
  1919.5     .12       0  3644.5     .18       0  4856.3      .1       0
  4856.5     .08       0  4941.9     .06       0  5049.6     .08       0
  5136.8      .1       0  6974.1      .1       0  8666.3      .2       0
Levee=0,,,-1,6975,110,,
#XS Ineff= 2 , 0
       0    4715   103.2    5520       0     102
Permanent Ineff=
       F       F
Bank Sta=4941.9,5049.6
XS Rating Curve= 0
Exp/Cntr=.5,.3

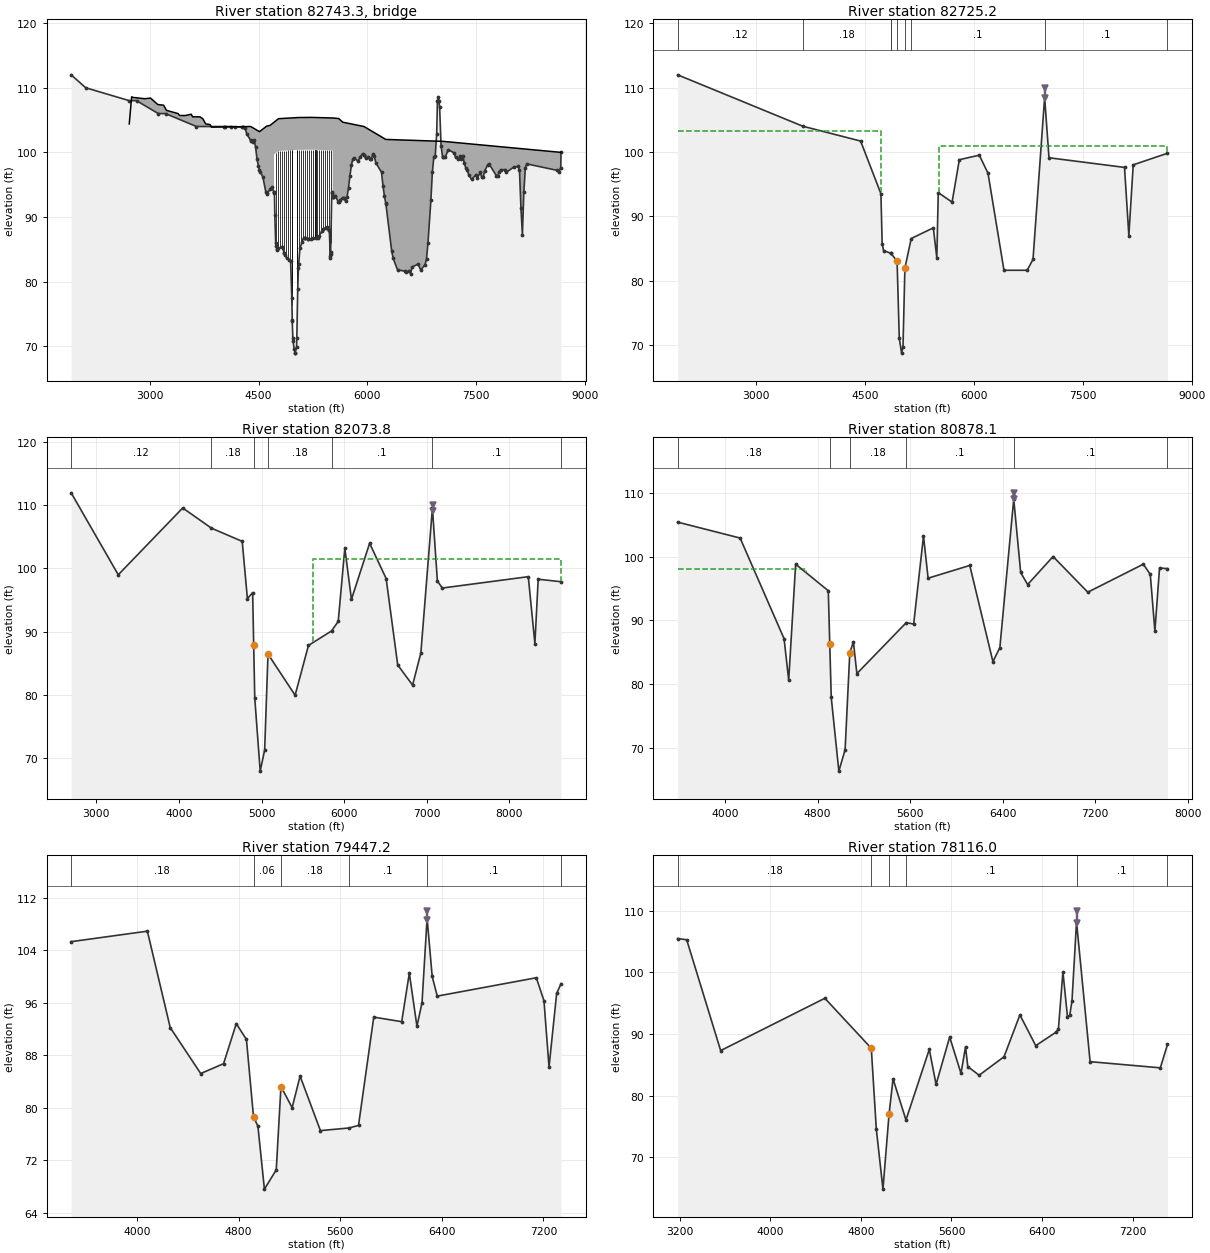
Type RM Length L Ch R = 3 ,82743.3 ,,,
BEGIN DESCRIPTION:
UNION PACIFIC RAILROAD
Structure ID: J100-00-00-02
T/R elev from station 5900 projected from railroad alignment. Northgate Development Levee at sta 6975.
Circular piers, ten pile trestle bent
END DESCRIPTION:
Node Name=UP Railroad 2
Bridge Culvert--1,0,-1,-1, 0
Deck Dist Width WeirC Skew NumUp NumDn MinLoCord MaxHiCord MaxSubmerge Is_Ogee
10,16.3,2.6,0, 36, 36, , , .95, 0, 1,1,,
  2719.5  2752.5  2772.5  2932.5  3012.5  3112.5  3192.5  3232.5  3392.5  3412.5
  3492.5  3572.5  3592.5  3692.5  3732.5  3772.5  3832.5  3852.5  4392.5  4512.5
  4612.6  4657.6 4712.91    4713  4774.4  5049.6  5229.1 5521.49  5521.6  5604.6
  5659.5  5952.5  6252.5  7042.5  8662.2  8666.3
   104.4   108.6   108.5   108.3   108.4   107.4   107.3   106.5     106   105.7
   105.7   105.9   105.5   105.5   105.2   104.4   104.3   103.9     104   103.2
  104.06  104.16  104.66  104.66  105.21  105.39  105.41  105.32  105.32  105.23
  104.67     104     102   101.7     100     100
       0       0       0       0       0       0       0       0       0       0
       0       0       0       0       0       0       0       0       0       0
       0       0       0   99.66  100.21  100.39  100.41  100.32       0       0
       0       0       0       0       0       0
  2719.5  2752.5  2772.5  2932.5  3012.5  3112.5  3192.5  3232.5  3392.5  3412.5
  3492.5  3572.5  3592.5  3692.5  3732.5  3772.5  3832.5  3852.5  4392.5  4512.5
  4612.6  4657.6 4712.91    4713  4774.4  5049.6  5229.1 5521.49  5521.6  5604.6
  5659.5  5952.5  6252.5  7042.5  8662.2  8666.3
   104.4   108.6   108.5   108.3   108.4   107.4   107.3   106.5     106   105.7
   105.7   105.9   105.5   105.5   105.2   104.4   104.3   103.9     104   103.2
  104.06  104.16  104.66  104.66  105.21  105.39  105.41  105.32  105.32  105.23
  104.67     104     102   101.7     100     100
       0       0       0       0       0       0       0       0       0       0
       0       0       0       0       0       0       0       0       0       0
       0       0       0   99.66  100.21  100.39  100.41  100.32       0       0
       0       0       0       0       0       0
Pier Skew, UpSta & Num, DnSta & Num=  ,4741, 2 ,4741, 2 , 0 , 0 , 0 ,,
       1       1
   84.66  100.92
       1       1
   84.47  100.73
Pier Skew, UpSta & Num, DnSta & Num=  ,4767.4, 2 ,4767.4, 2 , 0 , 0 , 0 ,,
       1       1
   84.11  101.15
       1       1
   83.92  100.96
Pier Skew, UpSta & Num, DnSta & Num=  ,4792.4, 2 ,4792.4, 2 , 0 , 0 , 0 ,,
       1       1
    84.2  101.23
       1       1
   84.01  101.04
Pier Skew, UpSta & Num, DnSta & Num=  ,4820.4, 2 ,4820.4, 2 , 0 , 0 , 0 ,,
       1       1
    84.3  101.26
       1       1
   84.11  101.07
Pier Skew, UpSta & Num, DnSta & Num=  ,4847.4, 2 ,4847.4, 2 , 0 , 0 , 0 ,,
       1       1
   83.67  101.27
       1       1
   83.48  101.08
Pier Skew, UpSta & Num, DnSta & Num=  ,4873.4, 2 ,4873.4, 2 , 0 , 0 , 0 ,,
       1       1
   82.96  101.29
       1       1
   82.77   101.1
Pier Skew, UpSta & Num, DnSta & Num=  ,4901.3, 2 ,4901.3, 2 , 0 , 0 , 0 ,,
       1       1
   82.49  101.32
       1       1
    82.3  101.13
Pier Skew, UpSta & Num, DnSta & Num=  ,4929.3, 2 ,4929.3, 2 , 0 , 0 , 0 ,,
       1       1
   82.31  101.34
       1       1
   82.12  101.15
Pier Skew, UpSta & Num, DnSta & Num=  ,4956.2, 2 ,4956.2, 2 , 0 , 0 , 0 ,,
       2       2
   76.83  101.34
       2       2
   76.64  101.15
Pier Skew, UpSta & Num, DnSta & Num=  ,4960.2, 2 ,4960.2, 2 , 0 , 0 , 0 ,,
       2       2
   74.82  101.34
       2       2
   74.63  101.15
Pier Skew, UpSta & Num, DnSta & Num=  ,5032, 2 ,5032, 2 , 0 , 0 , 0 ,,
       2       2
    72.4  101.36
       2       2
   72.21  101.17
Pier Skew, UpSta & Num, DnSta & Num=  ,5035.6, 2 ,5035.6, 2 , 0 , 0 , 0 ,,
       2       2
   74.65  101.37
       2       2
   74.46  101.18
Pier Skew, UpSta & Num, DnSta & Num=  ,5062.2, 2 ,5062.2, 2 , 0 , 0 , 0 ,,
       1       1
   82.91  101.39
       1       1
   82.72   101.2
Pier Skew, UpSta & Num, DnSta & Num=  ,5088.6, 2 ,5088.6, 2 , 0 , 0 , 0 ,,
       1       1
   84.73  101.38
       1       1
   84.54  101.19
Pier Skew, UpSta & Num, DnSta & Num=  ,5115.3, 2 ,5115.3, 2 , 0 , 0 , 0 ,,
       1       1
   85.58  101.38
       1       1
   85.39  101.19
Pier Skew, UpSta & Num, DnSta & Num=  ,5143.4, 2 ,5143.4, 2 , 0 , 0 , 0 ,,
       1       1
    85.7  101.38
       1       1
   85.51  101.19
Pier Skew, UpSta & Num, DnSta & Num=  ,5171.6, 2 ,5171.6, 2 , 0 , 0 , 0 ,,
       1       1
   85.59  101.39
       1       1
    85.4   101.2
Pier Skew, UpSta & Num, DnSta & Num=  ,5198.4, 2 ,5198.4, 2 , 0 , 0 , 0 ,,
       1       1
    85.6   101.4
       1       1
   85.41  101.21
Pier Skew, UpSta & Num, DnSta & Num=  ,5226.4, 2 ,5226.4, 2 , 0 , 0 , 0 ,,
       1       1
   85.64  101.41
       1       1
   85.45  101.22
Pier Skew, UpSta & Num, DnSta & Num=  ,5254.5, 2 ,5254.5, 2 , 0 , 0 , 0 ,,
       1       1
   85.68   101.4
       1       1
   85.49  101.21
Pier Skew, UpSta & Num, DnSta & Num=  ,5282.3, 2 ,5282.3, 2 , 0 , 0 , 0 ,,
       1       1
   85.72  101.39
       1       1
   85.53   101.2
Pier Skew, UpSta & Num, DnSta & Num=  ,5285.1, 2 ,5285.1, 2 , 0 , 0 , 0 ,,
       1       1
   85.72  101.39
       1       1
   85.53   101.2
Pier Skew, UpSta & Num, DnSta & Num=  ,5309.3, 2 ,5309.3, 2 , 0 , 0 , 0 ,,
       1       1
   85.75  101.39
       1       1
   85.56   101.2
Pier Skew, UpSta & Num, DnSta & Num=  ,5332.5, 2 ,5332.5, 2 , 0 , 0 , 0 ,,
       1       1
   86.01  101.39
       1       1
   85.82   101.2
Pier Skew, UpSta & Num, DnSta & Num=  ,5359.3, 2 ,5359.3, 2 , 0 , 0 , 0 ,,
       1       1
   86.53   101.4
       1       1
   86.34  101.21
Pier Skew, UpSta & Num, DnSta & Num=  ,5386.4, 2 ,5386.4, 2 , 0 , 0 , 0 ,,
       1       1
   87.05  101.39
       1       1
   86.86   101.2
Pier Skew, UpSta & Num, DnSta & Num=  ,5413.4, 2 ,5413.4, 2 , 0 , 0 , 0 ,,
       1       1
   87.27  101.38
       1       1
   87.08  101.19
Pier Skew, UpSta & Num, DnSta & Num=  ,5441.4, 2 ,5441.4, 2 , 0 , 0 , 0 ,,
       1       1
   87.39  101.37
       1       1
    87.2  101.18
Pier Skew, UpSta & Num, DnSta & Num=  ,5468.7, 2 ,5468.7, 2 , 0 , 0 , 0 ,,
       1       1
   86.92  101.36
       1       1
   86.73  101.17
Pier Skew, UpSta & Num, DnSta & Num=  ,5495.4, 2 ,5495.4, 2 , 0 , 0 , 0 ,,
       1       1
   84.62  101.35
       1       1
   84.43  101.16
Abutment Skew #Up #Dn= , 2 , 2
  4712.8    4743
   99.66   85.57
  4712.8    4743
   99.47   85.38
Abutment Skew #Up #Dn= , 2 , 2
  5491.6 5521.69
   84.24  100.32
  5491.6 5521.69
   84.05  100.13
BR Coef= 1 , 1 , 1 ,2.5, 0 ,,,.8,0,1.6,0,
WSPro=,,,, 1 ,,,, 0 ,,,, 0 ,,,,-1 ,-1 ,-1 , 0 , 0 , 0 , 0 , 0
BR U #Sta/Elev= 183
  1919.5     112  2119.5     110  2719.5     108  2819.5     108  3119.5     106
  3219.5     106  3644.5     104  4019.5     104  4044.5     104  4119.5     104
  4179.5  103.95  4272.5   103.9  4279.5  103.85  4312.5   103.8  4339.5  102.81
  4392.5  101.84  4399.5  101.71  4419.5  101.61  4439.5  101.91  4459.5  100.81
  4479.5   98.91  4499.5   97.81  4512.5   97.29  4519.5   97.01  4559.5   96.21
  4599.5   93.91  4612.6   93.71  4619.5   93.61  4657.6   94.25  4679.5   94.61
 4712.91   93.86    4713   93.86  4719.5   93.71  4724.6   90.25  4736.4   85.96
    4743   85.58  4755.5   84.87  4756.8   85.08  4774.4   85.15  4818.6   85.31
    4824   85.33  4856.3   84.45  4856.5   84.44  4868.5   84.12  4887.8   83.59
  4914.9   83.41  4941.9   83.24  4958.2   77.49  4964.5      74    4965   73.82
  4972.4   71.22    4977   70.72  4989.5   69.62    5004   68.92  5005.7   69.01
  5023.5   69.92  5027.5   71.22  5039.6   78.78  5049.6   82.14  5053.2   82.67
  5070.2   85.17  5099.3    86.1  5121.6   86.81  5136.8   86.75  5144.9   86.71
  5176.8   86.58  5184.5   86.59  5229.1   86.66  5251.7   86.69  5284.7   86.73
  5319.5   86.78  5331.3   87.01  5376.5   87.88  5392.4   88.19  5423.2   88.33
  5441.4   88.41  5467.8   87.94  5467.9   87.94  5474.8   87.91  5488.4   83.88
  5489.4   83.72  5491.6   84.25  5493.2   84.63    5509   93.89  5511.7   93.69
  5519.5   93.11 5521.49   93.11  5521.6   93.12  5558.4   93.21  5559.5   93.21
  5599.5   92.31  5604.6   92.37  5622.6   92.58  5659.5   93.01  5679.5   92.91
  5699.5   92.41  5719.5   93.11  5739.5   94.51  5759.5   96.41  5779.5   98.01
  5799.5   99.01  5819.5   99.11  5874.1   98.61  5894.1   99.21  5934.1   99.81
  5952.5   99.63  5954.1   99.61  5974.1   99.11  6014.1   99.31  6034.1   99.01
  6054.1   99.01  6074.1   99.71  6094.1   99.51  6114.1   98.41  6194.1   96.91
  6214.1   94.81  6234.1   93.21  6252.5   92.11  6254.1   92.01  6334.1   84.71
  6354.1   83.61  6414.1   81.81  6514.1   81.61  6534.1   81.41  6574.1   81.71
  6594.1   81.21  6614.1   82.21  6694.1   82.71  6734.1   81.81  6794.1   82.61
  6814.1   83.51  6834.1   86.01  6874.1   92.61  6894.1   96.91  6914.1   99.21
  6934.1   99.51  6954.1  102.91  6964.1     108  6974.1   108.5  6984.1     108
  6994.1  107.01  7014.1  101.01  7034.1   99.31  7042.5   99.31  7074.1   99.31
  7114.1  100.41  7194.1   99.91  7214.1   99.21  7254.1   98.91  7274.1   99.41
  7294.1   98.91  7314.1   99.51  7334.1   98.31  7354.1   97.61  7374.1   97.31
  7394.1   96.51  7434.1   95.81  7494.1   96.51  7514.1   96.01  7554.1   96.91
  7574.1   96.11  7594.1   96.11  7614.1   97.11  7654.1   98.01  7674.1   98.21
  7774.1   96.41  7794.1   96.31  7814.1   97.01  7834.1   97.31  7894.1   97.31
  7914.1   96.91  8014.1   97.71  8074.1   97.81  8094.1   97.21  8114.1   91.41
  8134.1   87.21  8154.1   93.81  8174.1   97.51  8194.1   98.21  8614.1   97.21
  8634.1   96.91  8662.2   97.61  8666.3  100.01
BR U #Mann= 8
  1919.5     .12  3644.5     .18  4856.3      .1  4856.5     .08  4941.9    .055
  5049.6     .08  5136.8      .1  6974.1      .1
BR D #Sta/Elev= 183
  1919.5     112  2119.5     110  2719.5     108  2819.5     108  3119.5     106
  3219.5     106  3644.5     104  4019.5     104  4044.5     104  4119.5     104
  4179.5  103.95  4272.5   103.9  4279.5  103.85  4312.5  103.59  4339.5   102.6
  4392.5  101.63  4399.5   101.5  4419.5   101.4  4439.5   101.7  4459.5   100.6
  4479.5    98.7  4499.5    97.6  4512.5   97.08  4519.5    96.8  4559.5      96
  4599.5    93.7  4612.6    93.5  4619.5    93.4  4657.6   94.04  4679.5    94.4
 4712.91   93.65    4713   93.65  4719.5    93.5  4724.6   90.04  4736.4   85.75
    4743   85.37  4755.5   84.66  4756.8   84.87  4774.4   84.94  4818.6    85.1
    4824   85.12  4856.3   84.24  4856.5   84.23  4868.5   83.91  4887.8   83.38
  4914.9    83.2  4941.9   83.03  4958.2   77.28  4964.5   73.79    4965   73.61
  4972.4   71.01    4977   70.51  4989.5   69.41    5004   68.71  5005.7    68.8
  5023.5   69.71  5027.5   71.01  5039.6   78.57  5049.6   81.93  5053.2   82.46
  5070.2   84.96  5099.3   85.89  5121.6    86.6  5136.8   86.54  5144.9    86.5
  5176.8   86.37  5184.5   86.38  5229.1   86.45  5251.7   86.48  5284.7   86.52
  5319.5   86.57  5331.3    86.8  5376.5   87.67  5392.4   87.98  5423.2   88.12
  5441.4    88.2  5467.8   87.73  5467.9   87.73  5474.8    87.7  5488.4   83.67
  5489.4   83.51  5491.6   84.04  5493.2   84.42    5509   93.68  5511.7   93.48
  5519.5    92.9 5521.49    92.9  5521.6   92.91  5558.4      93  5559.5      93
  5599.5    92.1  5604.6   92.16  5622.6   92.37  5659.5    92.8  5679.5    92.7
  5699.5    92.2  5719.5    92.9  5739.5    94.3  5759.5    96.2  5779.5    97.8
  5799.5    98.8  5819.5    98.9  5874.1    98.4  5894.1      99  5934.1    99.6
  5952.5   99.42  5954.1    99.4  5974.1    98.9  6014.1    99.1  6034.1    98.8
  6054.1    98.8  6074.1    99.5  6094.1    99.3  6114.1    98.2  6194.1    96.7
  6214.1    94.6  6234.1      93  6252.5    91.9  6254.1    91.8  6334.1    84.5
  6354.1    83.4  6414.1    81.6  6514.1    81.4  6534.1    81.2  6574.1    81.5
  6594.1      81  6614.1      82  6694.1    82.5  6734.1    81.6  6794.1    82.4
  6814.1    83.3  6834.1    85.8  6874.1    92.4  6894.1    96.7  6914.1      99
  6934.1    99.3  6954.1   102.7  6964.1     108  6974.1   108.5  6984.1     108
  6994.1   106.8  7014.1   100.8  7034.1    99.1  7042.5    99.1  7074.1    99.1
  7114.1   100.2  7194.1    99.7  7214.1      99  7254.1    98.7  7274.1    99.2
  7294.1    98.7  7314.1    99.3  7334.1    98.1  7354.1    97.4  7374.1    97.1
  7394.1    96.3  7434.1    95.6  7494.1    96.3  7514.1    95.8  7554.1    96.7
  7574.1    95.9  7594.1    95.9  7614.1    96.9  7654.1    97.8  7674.1      98
  7774.1    96.2  7794.1    96.1  7814.1    96.8  7834.1    97.1  7894.1    97.1
  7914.1    96.7  8014.1    97.5  8074.1    97.6  8094.1      97  8114.1    91.2
  8134.1      87  8154.1    93.6  8174.1    97.3  8194.1      98  8614.1      97
  8634.1    96.7  8662.2    97.4  8666.3    99.8
BR D #Mann= 8
  1919.5     .12  3644.5     .18  4856.3      .1  4856.5     .08  4941.9    .055
  5049.6     .08  5136.8      .1  6974.1      .1
BC Design=,, 0 ,, 0 ,,,,,,
BC HTab HWMax=112

Type RM Length L Ch R = 1 ,82725.2 ,651.35,651.35,651.35
BEGIN DESCRIPTION:
Downstream Section of Union Pacific Railroad
Northgate levee at sta 6975
END DESCRIPTION:
XS GIS Cut Line= 4
    3097595.6254   13973454.6173    3097792.2869   13972645.1649
    3098556.6826   13969554.3474    3097407.5253   13967078.1622
#Sta/Elev= 30
  1919.5     112  3644.5     104  4439.5   101.7  4719.5    93.5  4736.4   85.75
  4755.5   84.66  4856.3   84.24  4856.5   84.23  4941.9   83.03  4972.4   71.01
    5004   68.71  5023.5   69.71  5049.6   81.93  5136.8   86.54  5441.4    88.2
  5489.4   83.51    5509   93.68  5699.5    92.2  5799.5    98.8  6074.1    99.5
  6194.1    96.7  6414.1    81.6  6734.1    81.6  6814.1    83.3  6974.1   108.5
  7034.1    99.1  8074.1    97.6  8134.1      87  8194.1      98  8666.3    99.8
#Mann= 9 ,-1 , 0
  1919.5     .12       0  3644.5     .18       0  4856.3      .1       0
  4856.5     .08       0  4941.9     .06       0  5049.6     .08       0
  5136.8      .1       0  6974.1      .1       0  8666.3      .2       0
Levee=0,,,-1,6975,110,,
#XS Ineff= 2 , 0
       0    4715   103.2    5520       0     101
Permanent Ineff=
       F       F
Bank Sta=4941.9,5049.6
XS Rating Curve= 0
Exp/Cntr=.5,.3

Type RM Length L Ch R = 1 ,82073.8 ,1557.35,1195.7,235.03
BEGIN DESCRIPTION:
Northgate Development Levee at sta 7076.
Cross Section XS65-Bridge2-Exp
END DESCRIPTION:
XS GIS Cut Line= 3
    3099710.7199   13972543.7578    3098797.6879   13969947.9901
    3097528.2846   13967036.2935
#Sta/Elev= 30
  2696.1     112  3266.1      99  4046.1   109.6  4393.3   106.4  4766.1   104.3
  4828.8   95.22  4892.3   96.18  4905.1    87.8  4917.9   79.42  4983.6   67.86
  5037.6   71.21  5078.2   86.42  5406.1    79.9  5567.8    87.8  5847.7    90.1
  5927.8    91.6  6007.8   103.2  6087.8    95.1  6307.8     104  6507.8    98.4
  6647.8    84.7  6827.8    81.5  6927.8    86.6  7067.8   109.6  7127.8      98
  7187.8    96.9  8227.8    98.7  8307.8    88.1  8347.8    98.3  8624.1    97.9
#Mann= 7 ,-1 , 0
  2696.1     .12       0  4393.3     .18       0  4905.1     .06       0
  5078.2     .18       0  5847.7      .1       0  7067.8      .1       0
  8624.1      .2       0
Levee=0,,,-1,7070,110,,
#XS Ineff= 2 , 0
       0    4300     105    5625       0   101.5
Permanent Ineff=
       F       F
Bank Sta=4905.1,5078.2
XS Rating Curve= 0
Exp/Cntr=.3,.1

Type RM Length L Ch R = 1 ,80878.1 ,961.79,1430.9,1427.52
BEGIN DESCRIPTION:
Northgate Development Levee at sta 6495.
Ineffective at Sta 4700 based on topo upstream of the cross section
Cross Section XS64
END DESCRIPTION:
XS GIS Cut Line= 3
    3100686.8858   13969643.8423    3098678.5972   13969083.8905
    3097723.9975   13967158.6141
#Sta/Elev= 30
  3590.2   105.4  4130.2   102.9  4510.2    87.1  4550.2    80.6  4610.2    98.8
  4892.3   94.63  4905.1   86.25  4917.9   77.87  4983.6   66.31  5037.6   69.66
  5078.2   84.87  5109.4   86.61  5139.3   81.62  5566.2   89.62  5630.2    89.4
  5715.1   103.2  5755.1    96.6  6115.1    98.6  6315.1    83.5  6375.1    85.7
  6495.1     109  6555.1    97.5  6615.1    95.6  6835.1     100  7135.1    94.4
  7615.1    98.8  7675.1    97.2  7715.1    88.3  7755.1    98.2    7824    98.1
#Mann= 6 ,-1 , 0
  3590.2     .18       0  4905.1     .06       0  5078.2     .18       0
  5566.2      .1       0  6495.1      .1       0    7824      .2       0
Levee=0,,,-1,6495,110,,
#XS Ineff= 2 , 0
       0    4700      98               0
Permanent Ineff=
       F       F
Bank Sta=4905.1,5078.2
XS Rating Curve= 0
Exp/Cntr=.3,.1

Type RM Length L Ch R = 1 ,79447.2 ,1414.85,1331.2,701.2
BEGIN DESCRIPTION:
Northgate Development Levee at sta 6280.
Cross Section XS63
END DESCRIPTION:
XS GIS Cut Line= 3
    3100844.3851   13969466.0884    3099880.5818   13968086.8526
    3097931.9424   13967121.9179
#Sta/Elev= 30
  3481.4   105.3  4081.4   106.9  4261.4    92.2  4501.4    85.2  4681.4    86.7
  4781.4    92.8  4861.4    90.4  4917.2   78.58  4951.8   77.18    5003   67.58
  5096.2   70.51  5133.3   83.22  5221.2      80    5284    84.8    5444    76.5
  5669.4    76.9    5744    77.3    5864    93.8    6084    93.1    6144   100.5
    6204    92.4    6244      96    6284   108.9    6324     100    6364      97
    7144    99.8    7204    96.3    7244    86.2    7304    97.4  7338.5    98.9
#Mann= 6 ,-1 , 0
  3481.4     .18       0  4917.2     .06       0  5133.3     .18       0
  5669.4      .1       0    6284      .1       0  7338.5      .2       0
Levee=0,,,-1,6285,110,,
Bank Sta=4917.2,5133.3
XS Rating Curve= 0
Exp/Cntr=.3,.1

Type RM Length L Ch R = 1 ,78116.0 ,1000.43,1562.7,1730.84
BEGIN DESCRIPTION:
Northgate Development Levee at sta 6705. Cross Section XS62
END DESCRIPTION:
XS GIS Cut Line= 3
    3102256.8555   13968446.8941    3101010.5581   13967721.2721
    3098225.5116   13966975.1333
#Sta/Elev= 30
    3182   105.5    3262   105.3    3562    87.3    4482    95.8    4892   87.68
  4936.1   74.61    4995    64.8  5048.9      77  5084.1    82.7  5198.2   76.03
  5404.1    87.5  5464.1    81.8  5584.1    89.5  5684.1    83.6  5724.1    87.9
  5744.1    84.7  5844.1    83.3  6064.1    86.3  6204.1    93.1  6344.1    88.1
  6524.1    90.3  6544.1    90.8  6584.1   100.1  6624.1    92.8  6644.1      93
  6664.1    95.4  6704.1   108.2  6824.1    85.5  7444.1    84.5  7507.4    88.3
#Mann= 6 ,-1 , 0
    3182     .18       0    4892     .06       0  5048.9     .18       0
  5198.2      .1       0  6704.1      .1       0  7507.4      .2       0
Levee=0,,,-1,6705,110,,
Bank Sta=4892,5048.9
XS Rating Curve= 0
Exp/Cntr=.3,.1