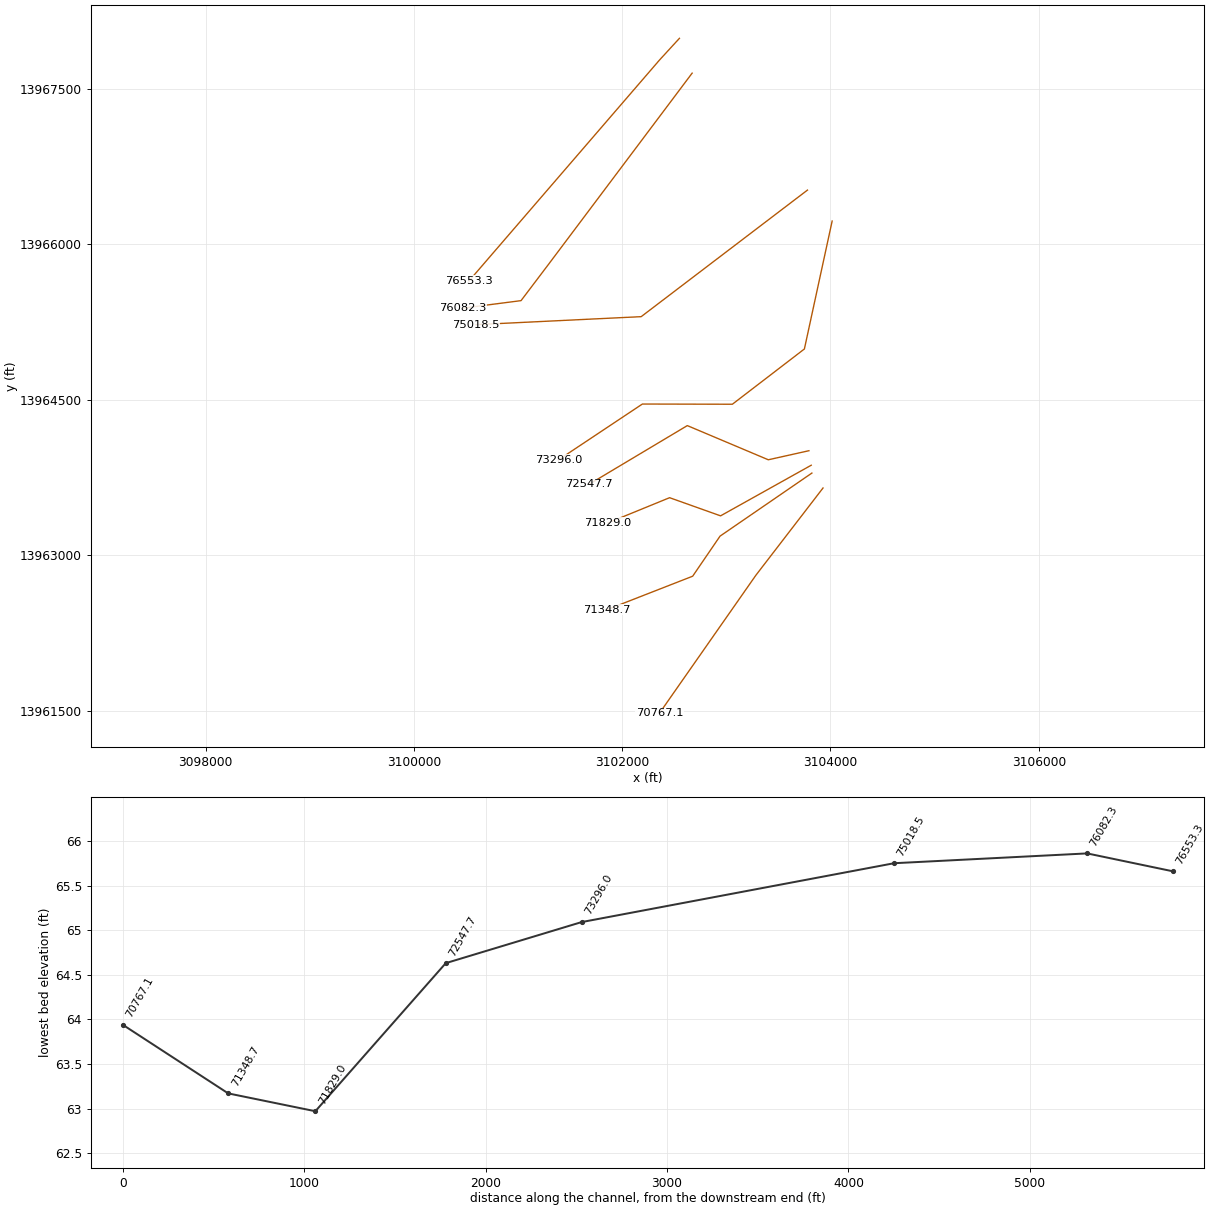
HEC-RAS study J100-00-00.prj: J100-00-00

--- J100-00-00.g01 (geometry) --- (continued)

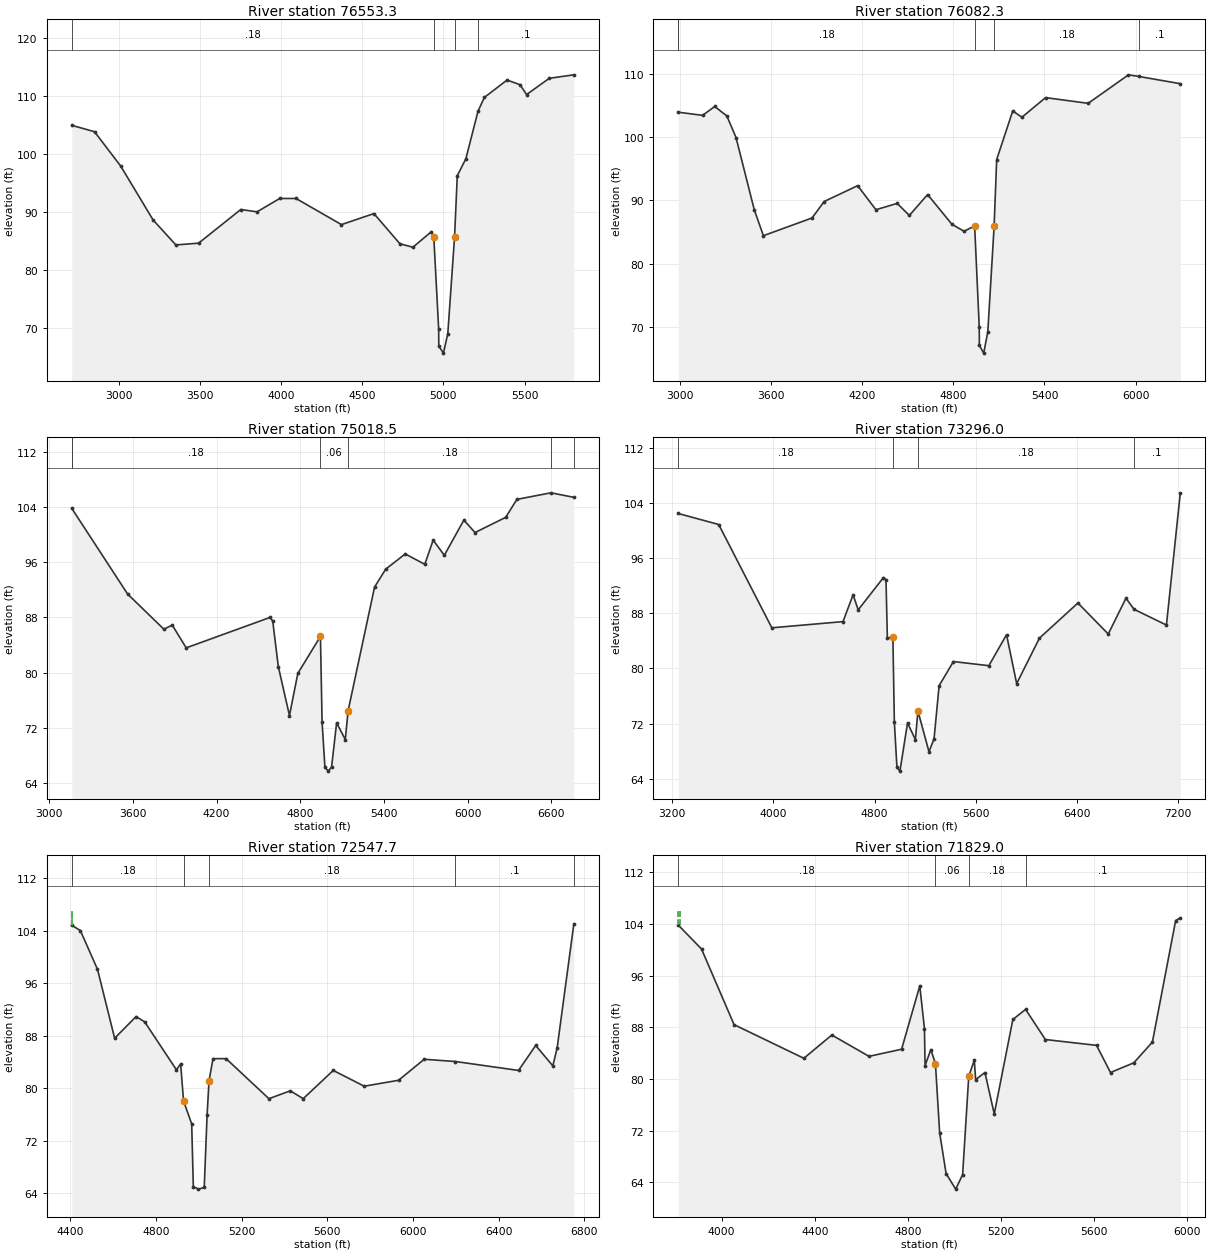
Type RM Length L Ch R = 1 ,76553.3 ,422.01,471,478.97
BEGIN DESCRIPTION:
Cross Section XS61.5
END DESCRIPTION:
XS GIS Cut Line= 3
    3102549.5668   13967984.3534    3102360.0072   13967777.0947
    3100528.6565   13965644.1098
#Sta/Elev= 30
  2711.3   104.9  2851.3   103.8  3012.2    97.9  3212.2    88.6  3352.2    84.3
  3492.2    84.6  3752.2    90.4  3852.2      90  3992.2    92.3  4092.2    92.3
  4372.2    87.8  4572.2    89.7  4732.2    84.5  4812.2    83.9  4925.4   86.56
  4940.7   85.75    4971   69.78  4971.8   66.87  5000.4   65.66  5027.3   69.03
  5068.8   85.66  5085.6   96.22  5138.6   99.15  5213.4  107.34  5252.2   109.7
  5392.2   112.7  5472.2   111.9  5512.2   110.2  5652.2     113  5803.5   113.6
#Mann= 4 ,-1 , 0
  2711.3     .18       0  4940.7     .06       0  5068.8     .18       0
  5213.4      .1       0
Bank Sta=4940.7,5068.8
XS Rating Curve= 0
Exp/Cntr=.3,.1

Type RM Length L Ch R = 1 ,76082.3 ,1224.64,1063.8,747.52
BEGIN DESCRIPTION:
Cross Section XS61
END DESCRIPTION:
XS GIS Cut Line= 4
    3102671.7049   13967648.6807    3101296.5506   13965809.9912
    3101028.7302   13965454.6143     3100472.488   13965382.5088
#Sta/Elev= 30
  2991.4   103.9  3151.4   103.4  3231.4   104.8  3311.4   103.3  3371.4    99.9
  3491.4    88.5  3551.4    84.4  3871.4    87.2  3951.4    89.8  4171.4    92.3
  4291.4    88.5  4431.4    89.5  4511.4    87.6  4631.4    90.9  4791.4    86.2
  4871.4    85.1  4940.7   85.95    4971   69.98  4971.8   67.07  5000.4   65.86
  5027.3   69.23  5068.8   85.86  5085.6   96.42  5191.4   104.1  5251.4   103.1
  5407.4   106.2  5687.4   105.3  5952.4   109.8  6021.2  109.54  6293.3   108.4
#Mann= 5 , 1 , 0
  2991.4      .2       0  2991.4     .18       0  4940.7     .06       0
  5068.8     .18       0  6021.2      .1       0
Bank Sta=4940.7,5068.8
XS Rating Curve= 0
Exp/Cntr=.3,.1

Type RM Length L Ch R = 1 ,75018.5 ,1261.97,1722.5,1278.71
BEGIN DESCRIPTION:
Cross Section XS60
END DESCRIPTION:
XS GIS Cut Line= 3
    3103779.0389   13966520.7451    3102182.4178   13965300.1025
    3100596.0974   13965222.8467
#Sta/Elev= 30
  3162.4   103.8  3562.4    91.4  3822.4    86.3  3882.4    86.9  3982.4    83.6
  4582.4      88  4602.4    87.5  4642.4    80.9  4722.4    73.8  4782.4    79.9
  4944.5   85.26  4956.2   72.85  4976.5   66.32  5000.3   65.75  5024.4   66.36
  5060.4   72.75  5122.5   70.32  5142.6   74.48  5332.2    92.4  5412.2      95
  5552.2    97.2  5692.2    95.7  5752.2    99.2  5832.2      97  5972.2   102.1
  6052.2   100.3  6272.2   102.5  6352.2   105.1  6595.9  106.05  6760.4   105.4
#Mann= 6 , 1 , 0
  3162.4      .2       0  3162.4     .18       0  4944.5     .06       0
  5142.6     .18       0  6595.9      .1       0  6760.4      .2       0
Bank Sta=4944.5,5142.6
XS Rating Curve= 0
Exp/Cntr=.3,.1

Type RM Length L Ch R = 1 ,73296.0 ,1154.83,748.3,230.99
BEGIN DESCRIPTION:
Cross Section XS59
END DESCRIPTION:
XS GIS Cut Line= 5
    3104016.1733   13966222.4755    3103749.5418   13964988.3129
    3103057.9842   13964455.4385    3102193.8253    13964457.398
    3101387.6314   13963918.6002
#Sta/Elev= 30
  3247.5   102.5  3567.5   100.9  3987.5    85.9  4550.1    86.8  4630.1    90.7
  4670.1    88.5  4870.1    93.2  4890.1    92.9  4900.9   84.41  4944.5    84.6
  4956.2   72.19  4976.5   65.66  5000.3   65.09  5060.4   72.09  5122.5   69.66
  5142.6   73.82  5230.1    67.9  5270.1    69.8  5310.1    77.5  5423.2      81
  5703.2    80.4  5843.2    84.9  5923.2    77.8  6103.2    84.4  6407.3    89.5
  6647.3      85  6787.3    90.2    6851   88.59  7107.3    86.3    7217   105.5
#Mann= 4 ,-1 , 0
  3247.5     .18       0  4944.5     .06       0  5142.6     .18       0
    6851      .1       0
Bank Sta=4944.5,5142.6
XS Rating Curve= 0
Exp/Cntr=.3,.1

Type RM Length L Ch R = 1 ,72547.7 ,286.26,718.7,742.42
BEGIN DESCRIPTION:
Cross Section XS58
END DESCRIPTION:
XS GIS Cut Line= 4
    3103793.1464   13964007.1771    3103403.0604   13963919.7978
    3102625.3514   13964249.4228    3101683.7795   13963684.6822
#Sta/Elev= 30
  4407.9   104.8  4447.9     104  4527.9    98.1  4607.9    87.6  4707.9    90.9
  4747.9    90.1  4896.1    82.8  4915.8   83.69  4929.5   78.03  4967.4   74.57
    4975      65  4999.1   64.63 5025.89   64.88  5039.2   75.86  5048.3   81.13
  5066.8   84.49  5127.7    84.5  5327.7    78.4  5427.7    79.6  5487.7    78.4
  5627.7    82.7  5772.3    80.3  5932.3    81.2  6052.3    84.4  6197.6   84.06
  6492.3    82.7  6572.3    86.5  6652.3    83.4  6672.3    86.1  6750.3     105
#Mann= 5 ,-1 , 0
  4407.9     .18       0  4929.5     .06       0  5048.3     .18       0
  6197.6      .1       0  6750.3      .2       0
#XS Ineff= 2 , 0
       0    4411     107  6750.3       0     107
Permanent Ineff=
       F       F
Bank Sta=4929.5,5048.3
XS Rating Curve= 0
Exp/Cntr=.3,.1

Type RM Length L Ch R = 1 ,71829.0 ,140.17,480.3,867.58
BEGIN DESCRIPTION:
Cross Section XS57
END DESCRIPTION:
XS GIS Cut Line= 4
    3103815.2798   13963867.3022    3102944.6756   13963379.0068
    3102455.3885   13963554.1201    3101863.4236    13963311.178
#Sta/Elev= 30
  3813.5   103.8  3913.5   100.1  4053.5    88.4  4353.5    83.2  4473.5    86.8
  4633.5    83.5  4773.5    84.6  4851.7    94.4  4871.7    87.8  4874.4   82.08
  4899.1   84.54  4918.9   82.38  4937.1   71.67  4964.8   65.37    5006   62.97
  5035.8   65.21  5062.1   80.41    5086   82.91  5091.7    79.9  5131.7      81
  5171.7    74.6  5251.7    89.2  5306.4   90.76  5391.4    86.1  5611.4    85.2
  5671.4      81  5771.4    82.5  5851.4    85.7  5951.4   104.5  5971.4   104.9
#Mann= 4 ,-1 , 0
  3813.5     .18       0  4918.9     .06       0  5062.1     .18       0
  5306.4      .1       0
#XS Ineff= 2 , 0
       0    3822     106  5971.4       0     106
Permanent Ineff=
       F       F
Bank Sta=4918.9,5062.1
XS Rating Curve= 0
Exp/Cntr=.3,.1

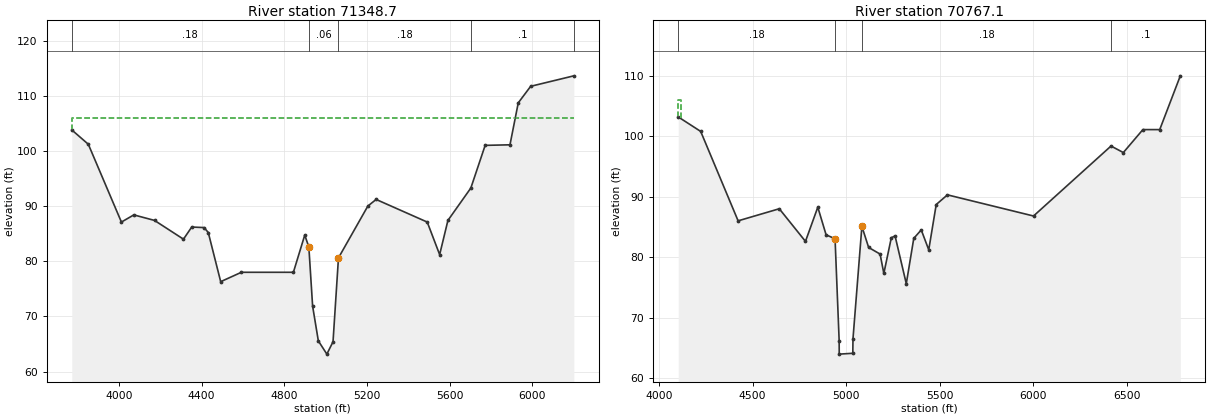
Type RM Length L Ch R = 1 ,71348.7 ,333.18,581.6,505.18
BEGIN DESCRIPTION:
Cross Section XS56
END DESCRIPTION:
XS GIS Cut Line= 4
     3103821.595   13963791.6159    3102939.5252    13963183.292
    3102676.8553   13962797.0127    3101849.1301   13962472.2091
#Sta/Elev= 30
  3772.7   103.8  3852.7   101.2  4012.7    87.1  4072.7    88.4  4172.7    87.4
  4312.7      84  4352.7    86.2  4412.7    86.1  4432.7    85.2  4492.7    76.3
  4592.7      78  4844.2      78  4899.1   84.74  4918.9   82.58  4937.1   71.87
  4964.8   65.57    5006   63.17  5035.8   65.41  5062.1   80.61  5204.2      90
  5244.2    91.2  5491.3    87.1  5551.3    81.2  5591.3    87.4  5702.1   93.27
  5771.3     101  5891.3   101.1  5931.3   108.7  5991.3   111.7  6200.1   113.6
#Mann= 5 ,-1 , 0
  3772.7     .18       0  4918.9     .06       0  5062.1     .18       0
  5702.1      .1       0  6200.1      .2       0
#XS Ineff= 2 , 0
       0    3772     106               0
Permanent Ineff=
       F       F
Bank Sta=4918.9,5062.1
XS Rating Curve= 0
Exp/Cntr=.3,.1

Type RM Length L Ch R = 1 ,70767.1 ,704.72,1029.3,855.44
BEGIN DESCRIPTION:
Cross Section XS55
END DESCRIPTION:
XS GIS Cut Line= 4
    3103928.6059   13963647.7939    3103284.6014   13962807.3134
    3102470.8396   13961638.1747 3102356.584325613961474.0231473
#Sta/Elev= 30
  4103.1   103.2  4223.1   100.8  4423.1      86  4643.1      88  4783.1    82.6
    4849   88.26  4893.4   83.68  4941.2   83.04  4963.1   66.19  4963.5   63.94
  5036.1   64.08    5037   66.47  5084.6   85.08  5120.7   81.59  5181.9    80.5
  5201.9    77.3  5241.9    83.2  5261.9    83.5  5321.9    75.6  5361.9    83.1
  5401.9    84.5  5441.9    81.2  5481.9    88.7  5541.9    90.3  6001.9    86.8
  6416.1   98.38  6481.9    97.3  6586.4   101.1  6676.4   101.1  6786.4     110
#Mann= 4 ,-1 , 0
  4103.1     .18       0  4941.2     .06       0  5084.6     .18       0
  6416.1      .1       0
#XS Ineff= 2 , 0
       0    4120     106               0
Permanent Ineff=
       F       F
Bank Sta=4941.2,5084.6
XS Rating Curve= 0
Exp/Cntr=.3,.1