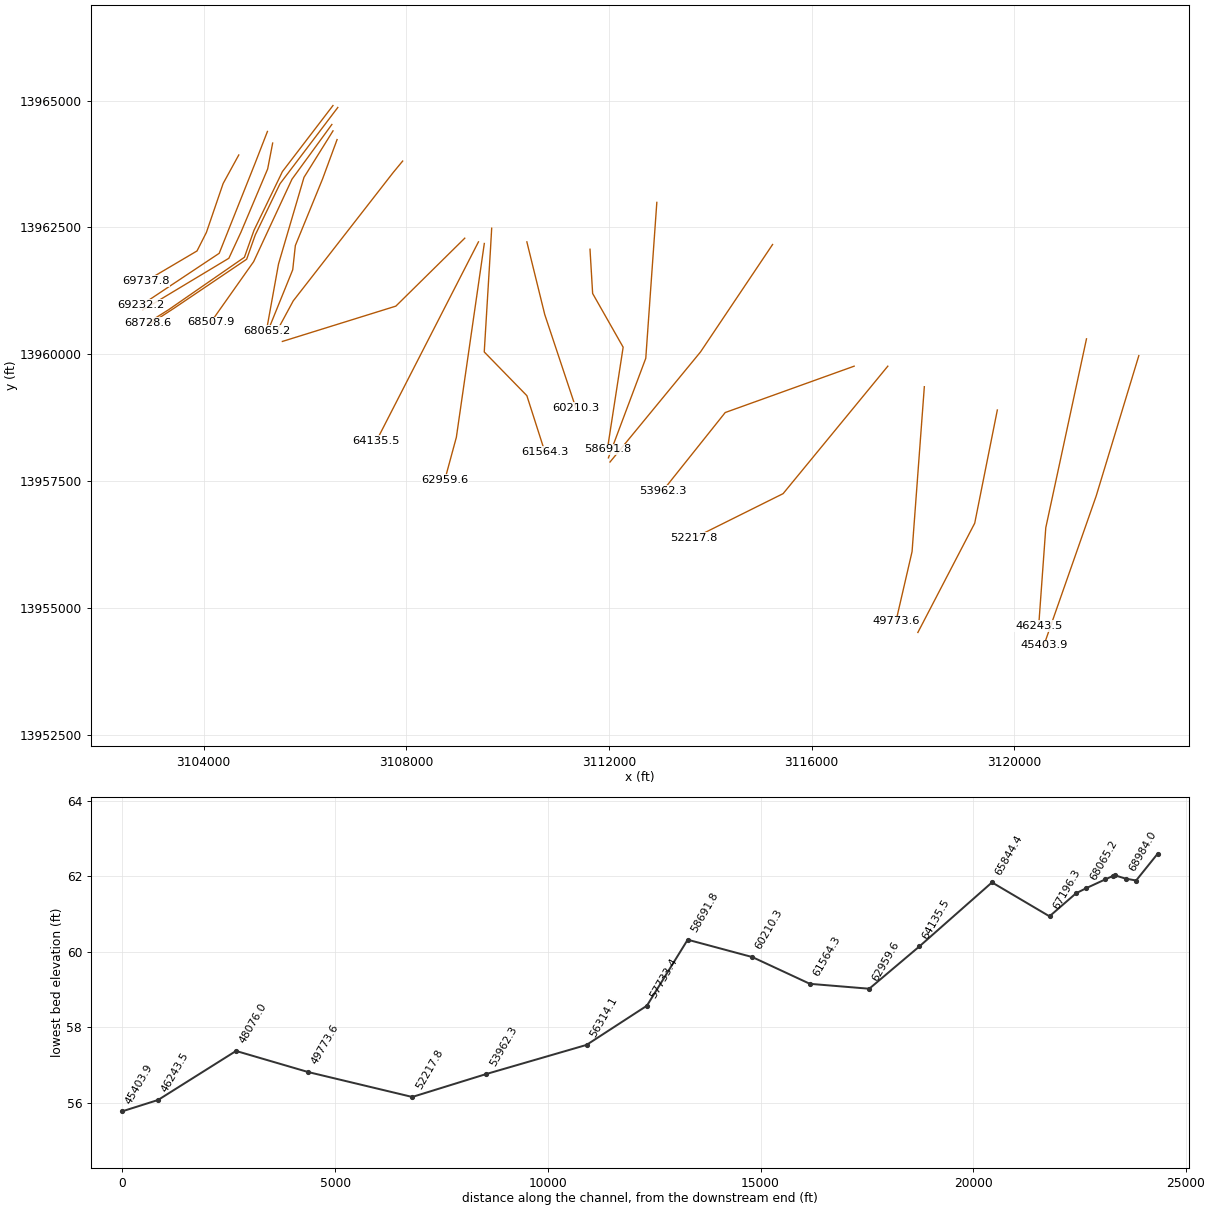
HEC-RAS study J100-00-00.prj: J100-00-00

--- J100-00-00.g01 (geometry) --- (continued)

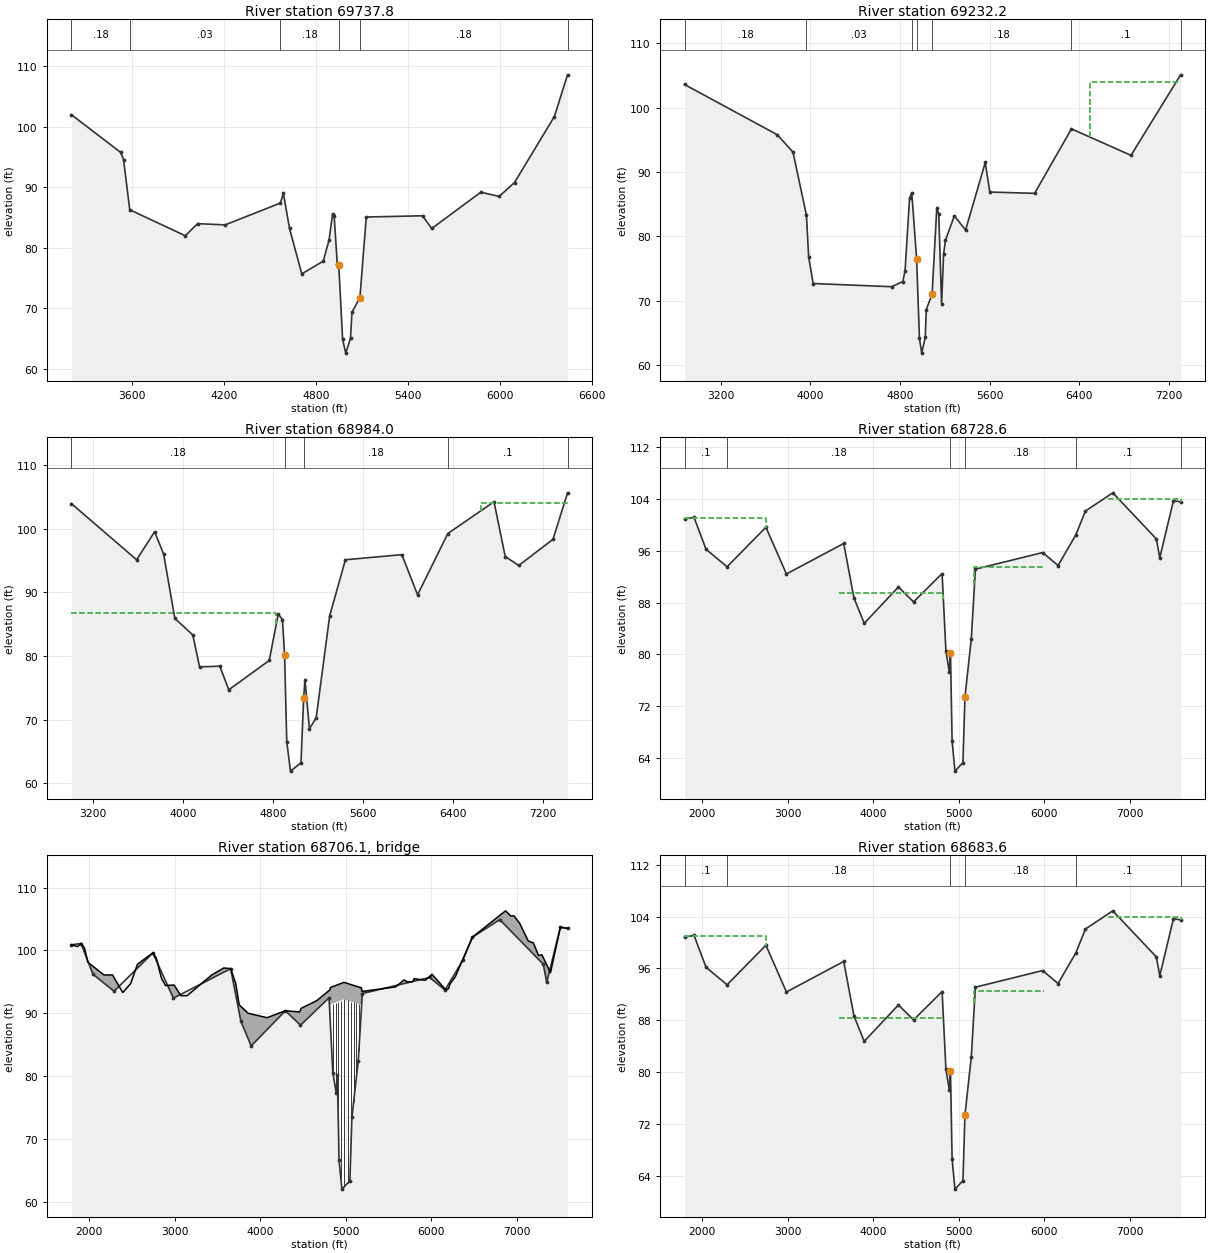
Type RM Length L Ch R = 1 ,69737.8 ,448.49,505.6,382.08
BEGIN DESCRIPTION:
Cross Section XS54
END DESCRIPTION:
XS GIS Cut Line= 5
    3104695.7436   13963926.7565     3104386.785   13963363.5556
      3104057.16   13962400.4326    3103871.7459   13962034.7548
    3102867.4197   13961442.4599
#Sta/Elev= 30
  3205.2     102  3525.2    95.8  3545.2    94.6  3585.2    86.3  3947.9      82
  4027.9      84  4207.9    83.8  4567.9    87.4  4587.9      89  4627.9    83.2
  4707.9    75.7  4847.9    77.8  4885.8    81.3  4908.9    85.6  4919.2   85.21
  4939.5   77.26    4949    77.2  4974.2    64.9  4994.3    62.6  5025.7   65.04
  5035.3   69.35  5087.2   71.78  5128.6    85.1  5495.8    85.3  5555.8    83.2
  5875.8    89.2  5995.8    88.5  6095.8    90.8  6355.8   101.7  6441.8   108.6
#Mann= 6 ,-1 , 0
  3205.2     .18       0  3585.2     .03       0  4567.9     .18       0
    4949     .06       0  5087.2     .18       0  6441.8      .2       0
Bank Sta=4949,5087.2
XS Rating Curve= 0
Exp/Cntr=.3,.1

Type RM Length L Ch R = 1 ,69232.2 ,279.28,248.2,178.33
BEGIN DESCRIPTION:
Cross Section XS53
Ineffective at Sta 6500 based on ineffective flow line
END DESCRIPTION:
XS GIS Cut Line= 5
    3105261.4526   13964390.3405    3105019.4854    13963768.025
    3104309.5291   13961988.4013    3102932.0192    13961073.413
    3102769.7647   13960976.5182
#Sta/Elev= 30
  2878.1   103.6  3705.8    95.8  3845.8    93.1  3965.8    83.3  3985.8    76.8
  4025.8    72.7  4725.8    72.2  4825.8      73  4845.8    74.7  4885.8    85.9
  4905.8    86.8    4949   76.49  4974.2   64.19  4994.3   61.89  5025.7   64.33
  5035.3   68.64  5087.2   71.07  5128.6   84.39  5146.6   83.47  5171.7   69.52
  5189.6   77.25  5206.6   79.44  5285.8    83.2  5385.8      81  5561.8    91.5
  5601.8    86.9  6001.8    86.7  6330.6   96.71  6861.8    92.6  7304.5   105.1
#Mann= 7 ,-1 , 0
  2878.1     .18       0  3965.8     .03       0  4905.8     .18       0
    4949     .06       0  5087.2     .18       0  6330.6      .1       0
  7304.5      .2       0
#XS Ineff= 2 , 0
       0  4905.8    86.8    6500       0     104
Permanent Ineff=
       T       F
Bank Sta=4949,5087.2
XS Rating Curve= 0
Exp/Cntr=.3,.1

Type RM Length L Ch R = 1 ,68984.0 ,243.5,255.4,180.75
BEGIN DESCRIPTION:
Cross Section XS52-Bridge1-Con
Ineffective at Sta 6650 based on ineffective flow line
END DESCRIPTION:
XS GIS Cut Line= 6
    3105364.5102   13964161.3236    3105265.6834   13963650.8564
    3104737.0116   13962400.4326    3104500.0936   13961890.5439
    3102935.8434    13960950.978    3102804.2223   13960879.6063
#Sta/Elev= 30
  3005.9   103.9  3585.8    95.1  3745.8    99.5  3825.8      96  3925.8    85.9
  4085.8    83.3  4145.8    78.3  4325.8    78.4  4405.8    74.7  4765.8    79.3
  4845.8    86.6  4883.4    85.7  4902.4   80.14  4921.6   66.55    4955   61.94
  5048.1   63.25  5071.9   73.38  5083.4    76.3  5123.4    68.6  5183.4    70.3
  5303.4    86.3  5443.4    95.1  5945.7    95.9  6085.7    89.6  6354.7   99.21
  6765.7   104.2  6865.7    95.6  6985.7    94.2  7290.4    98.3  7420.1   105.6
#Mann= 5 ,-1 , 0
  3005.9     .18       0  4902.4     .06       0  5071.9     .18       0
  6354.7      .1       0  7420.1      .2       0
#XS Ineff= 2 , 0
       0    4825    86.8    6650       0     104
Permanent Ineff=
       T       F
Bank Sta=4902.4,5071.9
XS Rating Curve= 0
Exp/Cntr=.5,.3

Type RM Length L Ch R = 1 ,68728.6 ,45,45,45
BEGIN DESCRIPTION:
Upstream Section of Riley Fuzzel
Ineffective at Sta 6750 based on topo downstream of the cross section
END DESCRIPTION:
XS GIS Cut Line= 6
    3106554.2806   13964900.8029    3105556.8908   13963599.2335
    3104996.0293   13962441.1465    3104807.2734   13961910.2706
    3103312.7056   13960877.4614     3102894.248   13960614.4719
#Sta/Elev= 30
  1792.5   100.9  1904.2   101.1  2044.2    96.2    2290   93.51  2744.2    99.6
  2984.2    92.4    3654    97.1    3774    88.7    3894    84.8    4294    90.4
  4470.7    88.1  4804.5   92.46  4849.2   80.51  4888.6   77.34  4902.4   80.23
  4921.6   66.64    4955   62.03  5048.1   63.34  5071.9   73.47  5146.2   82.43
  5193.8   93.14  5980.8    95.7  6160.8    93.7  6368.9   98.44  6480.8   102.1
  6800.8   104.9  7310.1    97.8  7350.1    94.9  7510.1   103.7  7593.7   103.5
#Mann= 6 ,-1 , 0
  1792.5      .1       0    2290     .18       0  4902.4     .06       0
  5071.9     .18       0  6368.9      .1       0  7593.7      .2       0
#XS Ineff= 4 ,-1
    3600    4820    89.4    5183    6000    93.5    6750  7593.7     104
  1792.5    2750     101
Permanent Ineff=
       F       F       F       F
Bank Sta=4902.4,5071.9
XS Rating Curve= 0
Exp/Cntr=.5,.3

Type RM Length L Ch R = 3 ,68706.1 ,,,
BEGIN DESCRIPTION:
RILEY FUZZELL
Structure ID: J100-00-00-01
Square nose piers
END DESCRIPTION:
Node Name=Riley Fuzzell
Bridge Culvert--1,0,-1,-1, 0
Deck Dist Width WeirC Skew NumUp NumDn MinLoCord MaxHiCord MaxSubmerge Is_Ogee
10,25,2.6,0, 60, 60, , , .95, 0, 1,1,,
  1792.5  1864.2  1904.2  1944.2  1984.2  2172.5  2272.5  2392.5  2484.2  2564.2
  2744.2  2784.2  2844.2  2892.5  2992.5  3072.5  3144.2    3434    3574    3654
    3714    3754  3859.6  4079.6    4294  4459.6  4479.6  4659.6  4804.5  4814.3
 4820.01  4820.1  4979.1 5181.99  5182.1    5190  5193.8  5580.8  5680.8  5720.8
  5780.8  5800.8  5928.6  6008.6  6168.6  6200.8  6220.8  6280.8  6480.8  6868.6
  6928.6  6968.6  7034.2  7134.2  7194.2  7254.2  7294.2  7394.2  7510.1  7593.7
   100.9  100.61  101.11  100.41   98.11    96.1    96.1    93.3   94.71   97.81
   99.61   98.81   95.61   94.41    94.5    92.8    92.8   96.11   97.21   97.11
   94.71   91.34      90    89.3   90.41    90.2    90.8      92   93.62   93.68
    94.1    94.1   94.92   94.05   94.05   93.46   93.48   94.19   95.31   95.01
   95.01   95.51   95.24    96.2   93.75   93.91   94.71   95.81  102.11   106.3
   105.5   105.5   104.3   101.5   101.2    99.2    99.3   96.46  103.71   103.5
                                                                                
                                                                                
                                                                           89.84
   88.31    91.4   92.22   91.35   90.51   92.29
                                                                                
                                                                                
  1792.5  1864.2  1904.2  1944.2  1984.2  2172.5  2272.5  2392.5  2484.2  2564.2
  2744.2  2784.2  2844.2  2892.5  2992.5  3072.5  3144.2    3434    3574    3654
    3714    3754  3859.6  4079.6    4294  4459.6  4479.6  4659.6  4804.5  4814.3
 4820.01  4820.1  4979.1 5181.99  5182.1    5190  5193.8  5580.8  5680.8  5720.8
  5780.8  5800.8  5928.6  6008.6  6168.6  6200.8  6220.8  6280.8  6480.8  6868.6
  6928.6  6968.6  7034.2  7134.2  7194.2  7254.2  7294.2  7394.2  7510.1  7593.7
   100.9  100.61  101.11  100.41   98.11    96.1    96.1    93.3   94.71   97.81
   99.61   98.81   95.61   94.41    94.5    92.8    92.8   96.11   97.21   97.11
   94.71   91.34      90    89.3   90.41    90.2    90.8      92   93.62   93.68
    94.1    94.1   94.92   94.05   94.05   93.46   93.48   94.19   95.31   95.01
   95.01   95.51   95.24    96.2   93.75   93.91   94.71   95.81  102.11   106.3
   105.5   105.5   104.3   101.5   101.2    99.2    99.3   96.46  103.71   103.5
                                                                                
                                                                                
                                                                           89.84
   88.31    91.4   92.22   91.35   90.51   92.29
                                                                                
                                                                                
Pier Skew, UpSta & Num, DnSta & Num=  ,4850.3, 2 ,4850.3, 2 , 0 , 0 , 0 ,,
     1.3     1.3
   79.37   92.45
     1.3     1.3
   79.36   92.44
Pier Skew, UpSta & Num, DnSta & Num=  ,4880.9, 2 ,4880.9, 2 , 0 , 0 , 0 ,,
     1.3     1.3
   76.91   92.62
     1.3     1.3
    76.9   92.61
Pier Skew, UpSta & Num, DnSta & Num=  ,4911.1, 2 ,4911.1, 2 , 0 , 0 , 0 ,,
     1.3     1.3
   72.61   92.91
     1.3     1.3
    72.6    92.9
Pier Skew, UpSta & Num, DnSta & Num=  ,4941.6, 2 ,4941.6, 2 , 0 , 0 , 0 ,,
     1.3     1.3
   63.81    93.1
     1.3     1.3
    63.8   93.09
Pier Skew, UpSta & Num, DnSta & Num=  ,4981.4, 2 ,4981.4, 2 , 0 , 0 , 0 ,,
     1.3     1.3
   61.39   93.22
     1.3     1.3
   61.38   93.21
Pier Skew, UpSta & Num, DnSta & Num=  ,5021.5, 2 ,5021.5, 2 , 0 , 0 , 0 ,,
     1.3     1.3
   61.96   93.14
     1.3     1.3
   61.95   93.13
Pier Skew, UpSta & Num, DnSta & Num=  ,5061.8, 2 ,5061.8, 2 , 0 , 0 , 0 ,,
     1.3     1.3
   66.32   93.02
     1.3     1.3
   66.31   93.01
Pier Skew, UpSta & Num, DnSta & Num=  ,5092.2, 2 ,5092.2, 2 , 0 , 0 , 0 ,,
     1.3     1.3
   74.84   92.86
     1.3     1.3
   74.83   92.85
Pier Skew, UpSta & Num, DnSta & Num=  ,5122.8, 2 ,5122.8, 2 , 0 , 0 , 0 ,,
     1.3     1.3
   78.53   92.54
     1.3     1.3
   78.52   92.53
Pier Skew, UpSta & Num, DnSta & Num=  ,5153.1, 2 ,5153.1, 2 , 0 , 0 , 0 ,,
     1.3     1.3
   82.84   92.38
     1.3     1.3
   82.83   92.37
Abutment Skew #Up #Dn= , 2 , 2
  4819.9  4849.3
    91.4    80.5
  4819.9  4849.3
   91.39   80.49
Abutment Skew #Up #Dn= , 2 , 2
  5059.7 5182.19
   66.49   91.35
  5059.7 5182.19
   66.48   91.34
BR Coef= 1 , 1 , 1 ,1.25, 0 ,,,.8,0,2,0,
WSPro=,,,, 1 ,,,, 0 ,,,, 0 ,,,,-1 ,-1 ,-1 , 0 , 0 , 0 , 0 , 0
BR U #Sta/Elev= 30
  1792.5   100.9  1904.2   101.1  2044.2    96.2    2290   93.51  2744.2    99.6
  2984.2    92.4    3654    97.1    3774    88.7    3894    84.8    4294    90.4
  4470.7    88.1  4804.5   92.46  4849.2   80.51  4888.6   77.34  4902.4   80.23
  4921.6   66.64    4955   62.03  5048.1   63.34  5071.9   73.47  5146.2   82.43
  5193.8   93.14  5980.8    95.7  6160.8    93.7  6368.9   98.44  6480.8   102.1
  6800.8   104.9  7310.1    97.8  7350.1    94.9  7510.1   103.7  7593.7   103.5
BR U #Mann= 5
  1792.5      .1    2290     .18  4902.4    .055  5071.9     .18  6368.9      .1
BR D #Sta/Elev= 30
  1792.5  100.88  1904.2  101.08  2044.2   96.18    2290   93.49  2744.2   99.58
  2984.2   92.38    3654   97.08    3774   88.68    3894   84.78    4294   90.38
  4470.7   88.08  4804.5   92.44  4849.2   80.49  4888.6   77.32  4902.4   80.21
  4921.6   66.62    4955   62.01  5048.1   63.32  5071.9   73.45  5146.2   82.41
  5193.8   93.12  5980.8   95.68  6160.8   93.68  6368.9   98.42  6480.8  102.08
  6800.8  104.88  7310.1   97.78  7350.1   94.88  7510.1  103.68  7593.7  103.48
BR D #Mann= 5
  1792.5      .1    2290     .18  4902.4    .055  5071.9     .18  6368.9      .1
BC Design=,, 0 ,, 0 ,,,,,,
BC HTab HWMax=104.9

Type RM Length L Ch R = 1 ,68683.6 ,175.7,175.7,175.7
BEGIN DESCRIPTION:
Downstream Section of Riley Fuzzell
Ineffective at Sta 6750 based on topo downstream of the cross section
END DESCRIPTION:
XS GIS Cut Line= 6
    3106649.6453   13964862.6882    3105509.1535   13963359.2279
    3105021.2235   13962350.6417     3104851.161   13961871.3158
    3103420.2642   13960906.7576    3102951.2062   13960601.8041
#Sta/Elev= 30
  1792.5  100.88  1904.2  101.08  2044.2   96.18    2290   93.49  2744.2   99.58
  2984.2   92.38    3654   97.08    3774   88.68    3894   84.78    4294   90.38
  4470.7   88.08  4804.5   92.44  4849.2   80.49  4888.6   77.32  4902.4   80.21
  4921.6   66.62    4955   62.01  5048.1   63.32  5071.9   73.45  5146.2   82.41
  5193.8   93.12  5980.8   95.68  6160.8   93.68  6368.9   98.42  6480.8  102.08
  6800.8  104.88  7310.1   97.78  7350.1   94.88  7510.1  103.68  7593.7  103.48
#Mann= 6 ,-1 , 0
  1792.5      .1       0    2290     .18       0  4902.4     .06       0
  5071.9     .18       0  6368.9      .1       0  7593.7      .2       0
#XS Ineff= 4 ,-1
    3600    4820    88.4    5183    6000    92.5    6750  7593.7     104
  1792.5    2750     101
Permanent Ineff=
       F       F       F       F
Bank Sta=4902.4,5071.9
XS Rating Curve= 0
Exp/Cntr=.5,.3

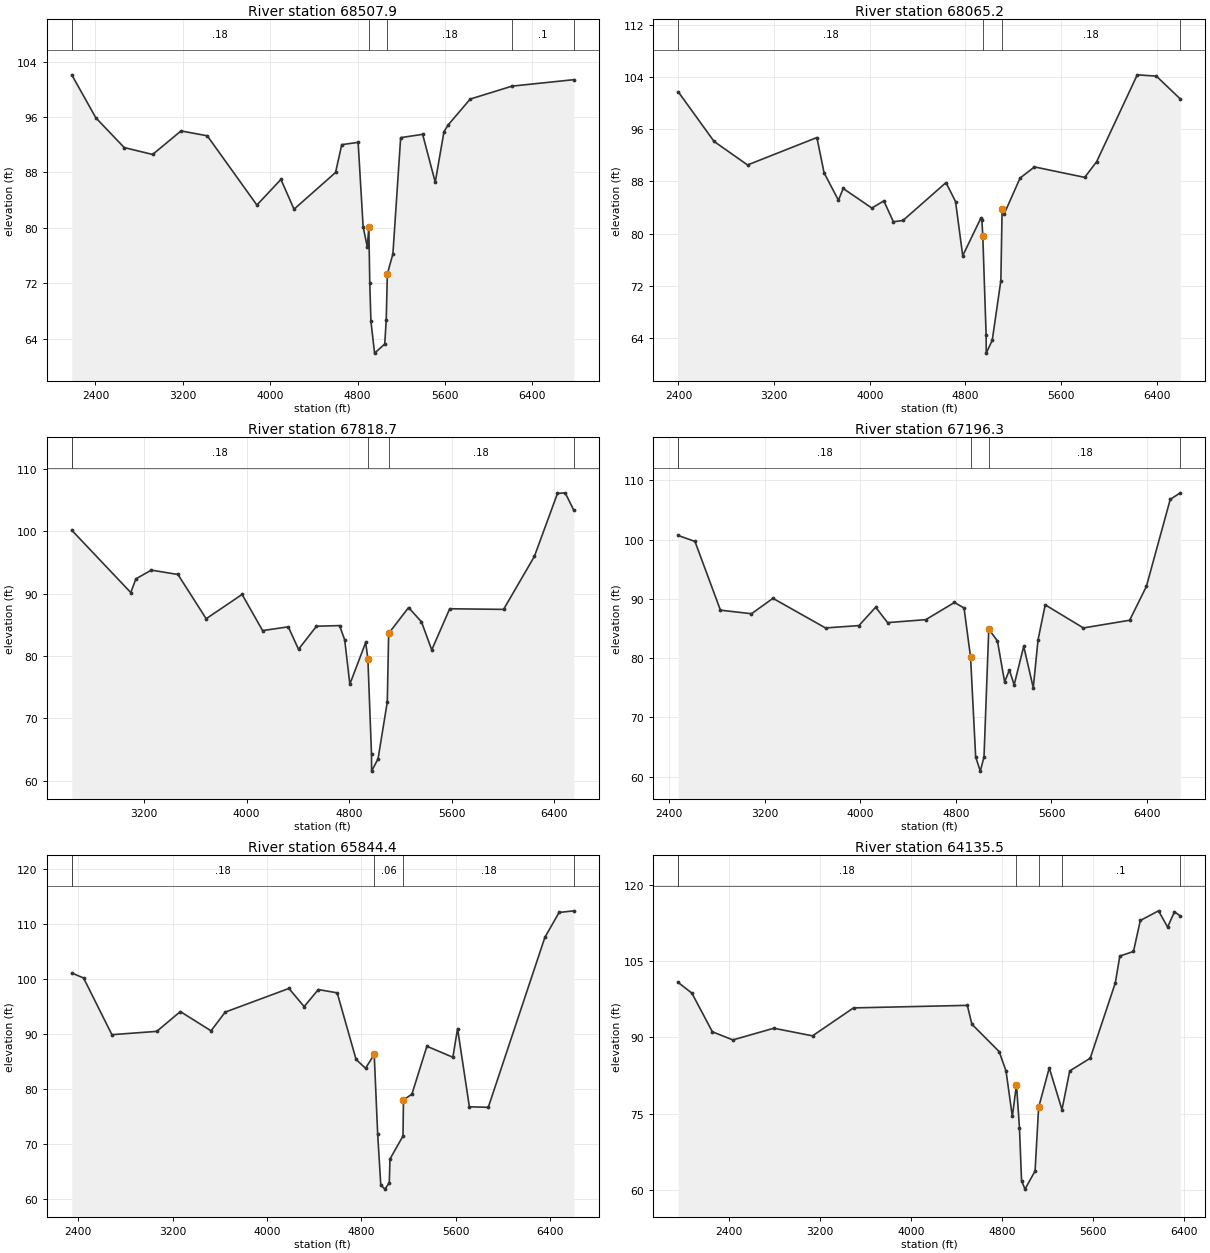
Type RM Length L Ch R = 1 ,68507.9 ,298.52,442.7,523.76
BEGIN DESCRIPTION:
Cross Section XS51-Bridge1-Exp
END DESCRIPTION:
XS GIS Cut Line= 4
    3106532.4962   13964527.7506    3105745.9361   13963449.7205
    3104989.7217   13961824.4239    3104141.7836   13960625.1972
#Sta/Elev= 30
  2183.3   102.1  2403.3    95.9  2663.3    91.6  2923.3    90.6  3183.3      94
  3423.3    93.3  3877.8    83.3  4097.8      87  4217.8    82.7  4597.8      88
  4654.7   92.02  4804.5   92.35  4850.3   80.16  4888.6   77.23  4902.4   80.12
  4911.1   72.08  4921.6   66.53    4955   61.92  5048.1   63.23  5061.8   66.72
  5071.9   73.36  5122.8   76.24  5193.8   93.03  5394.9   93.51  5510.4    86.6
  5590.4    93.9  5630.4    94.9  5830.4    98.6  6213.8  100.47  6779.1   101.4
#Mann= 6 , 1 , 0
  2183.3      .2       0  2183.3     .18       0  4902.4     .06       0
  5071.9     .18       0  6213.8      .1       0  6779.1      .2       0
Bank Sta=4902.4,5071.9
XS Rating Curve= 0
Exp/Cntr=.3,.1

Type RM Length L Ch R = 1 ,68065.2 ,250.1,246.5,230.5
BEGIN DESCRIPTION:
Cross Section XS50
END DESCRIPTION:
XS GIS Cut Line= 4
    3106555.3979   13964401.7913    3105982.8042    13963485.739
    3105479.8818   13961777.7008    3105241.0748   13960459.0705
#Sta/Elev= 30
  2398.1   101.7  2698.1    94.1  2978.1    90.5  3558.4    94.7  3618.4    89.3
  3738.4    85.1  3778.4    86.9  4018.4    83.9  4118.4      85  4198.4    81.8
  4278.4      82  4638.4    87.8  4718.4    84.9  4778.4    76.6  4929.1   82.33
  4938.9      82  4946.2   79.69  4974.4   64.39  4975.2   61.69  5025.4   63.66
  5097.5   72.79  5108.1   83.78  5126.4   83.05  5258.4    88.5  5378.9    90.2
  5798.9    88.6  5898.9      91  6238.9   104.3  6398.9   104.1    6599   100.6
#Mann= 4 ,-1 , 0
  2398.1     .18       0  4946.2     .06       0  5108.1     .18       0
    6599      .2       0
Bank Sta=4946.2,5108.1
XS Rating Curve= 0
Exp/Cntr=.3,.1

Type RM Length L Ch R = 1 ,67818.7 ,872.56,622.4,358.6
BEGIN DESCRIPTION:
Cross Section XS49
END DESCRIPTION:
XS GIS Cut Line= 5
    3106635.5538   13964230.0287    3106349.0701   13963453.6106
    3105812.1351   13962141.1028    3105760.2205   13961663.4887
    3105313.7552   13960562.8997
#Sta/Elev= 30
  2637.9   100.2  3097.9    90.2  3137.9    92.4  3257.9    93.8  3465.5    93.1
  3685.5      86  3965.5    89.9  4125.5    84.1  4325.5    84.7  4405.5    81.1
  4545.5    84.8  4725.5    84.9  4765.5    82.6  4805.5    75.5  4929.1   82.19
  4946.2   79.55  4974.4   64.25  4975.2   61.55  5025.4   63.52  5097.5   72.65
  5108.1   83.64  5263.6    87.8    5364    85.5    5444      81    5584    87.6
    6004    87.5    6244      96    6424   106.1    6484   106.2  6551.7   103.4
#Mann= 5 , 1 , 0
  2637.9      .2       0  2637.9     .18       0  4946.2     .06       0
  5108.1     .18       0  6551.7      .2       0
Bank Sta=4946.2,5108.1
XS Rating Curve= 0
Exp/Cntr=.3,.1

Type RM Length L Ch R = 1 ,67196.3 ,1865.03,1351.9,982.58
BEGIN DESCRIPTION:
Cross Section XS48
END DESCRIPTION:
XS GIS Cut Line= 4
    3107929.4992   13963806.3474    3107742.3935   13963580.3647
    3105770.6035   13961050.8967    3105435.5631   13960431.3449
#Sta/Elev= 30
  2474.4   100.7  2614.4    99.7  2827.8    88.1  3087.8    87.5  3267.8    90.1
  3707.8    85.1  3987.8    85.5  4127.8    88.6  4227.8      86  4547.8    86.5
  4787.8    89.4  4868.1   88.46  4922.6   80.18  4965.4   63.33  5004.2   60.94
  5035.2   63.34  5075.1    84.9  5147.8    82.9  5207.8      76  5247.8      78
  5287.8    75.5  5367.8      82  5447.8      75  5487.8    83.1  5547.8      89
  5867.8    85.1    6255    86.4    6395    92.1    6595   106.8  6679.3   107.9
#Mann= 5 , 1 , 0
  2474.4      .2       0  2474.4     .18       0  4922.6     .06       0
  5075.1     .18       0  6679.3      .2       0
Bank Sta=4922.6,5075.1
XS Rating Curve= 0
Exp/Cntr=.3,.1

Type RM Length L Ch R = 1 ,65844.4 ,1184.63,1708.9,2019.13
BEGIN DESCRIPTION:
Cross Section XS47
END DESCRIPTION:
XS GIS Cut Line= 3
    3109155.4339   13962286.4636     3107795.272   13960947.0675
    3105555.8966   13960250.8446
#Sta/Elev= 30
  2345.9   101.1  2445.9   100.2  2685.9    89.9  3065.9    90.5  3265.9    94.1
  3525.9    90.6  3645.9      94  4185.9    98.3  4314.8      95  4434.8    98.1
  4594.8    97.5  4754.8    85.4  4834.8    83.8  4908.5   86.31  4937.9   71.78
  4964.2   62.57  4999.5   61.84  5036.3   63.02  5041.9   67.31  5152.3   71.49
  5156.3   78.05  5227.8   79.09  5354.8    87.8  5574.8    85.8  5614.8      91
  5714.8    76.8  5874.8    76.7  6354.8   107.6  6474.8   112.1  6599.9   112.4
#Mann= 5 , 1 , 0
  2345.9      .2       0  2345.9     .18       0  4908.5     .06       0
  5156.3     .18       0  6599.9      .2       0
Bank Sta=4908.5,5156.3
XS Rating Curve= 0
Exp/Cntr=.3,.1

Type RM Length L Ch R = 1 ,64135.5 ,956.5,1175.9,1301.35
BEGIN DESCRIPTION:
Cross Section XS46
END DESCRIPTION:
XS GIS Cut Line= 2
    3109425.3897   13962213.7832    3107411.1041   13958289.0412
#Sta/Elev= 30
    1952   100.8    2072    98.7    2252    91.1    2432    89.5    2792    91.8
    3132    90.3    3492    95.8    4492    96.3    4532    92.6    4772    87.2
    4832    83.4  4887.6   74.44    4924   80.71  4950.2   72.23  4968.5   61.82
  4998.7   60.14  5087.3    63.7  5118.7   76.22    5212      84  5323.7   75.78
    5392    83.4    5572    85.9    5792   100.7    5832     106    5952   106.9
    6012     113    6172   114.9    6252   111.7    6312   114.7  6363.5   113.9
#Mann= 6 , 1 , 0
    1952      .2       0    1952     .18       0    4924     .06       0
  5118.7     .18       0  5323.7      .1       0  6363.5      .2       0
Bank Sta=4924,5118.7
XS Rating Curve= 0
Exp/Cntr=.3,.1

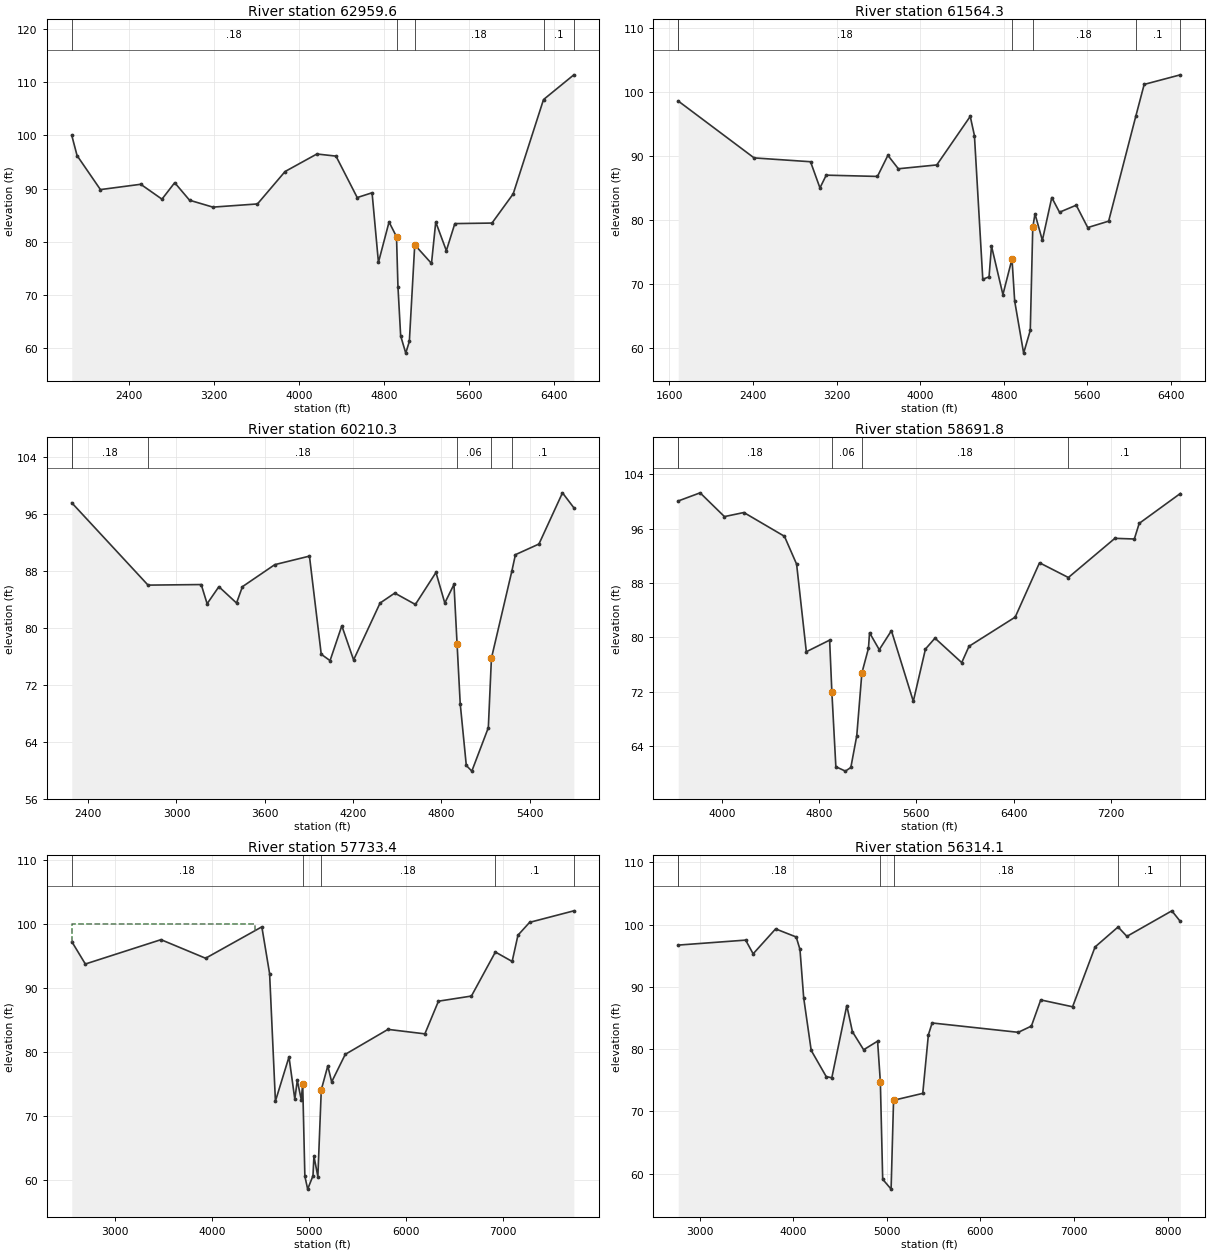
Type RM Length L Ch R = 1 ,62959.6 ,341.33,1395.3,1650.58
BEGIN DESCRIPTION:
Cross Section XS45
END DESCRIPTION:
XS GIS Cut Line= 4
  3109541.031114 13962182.148926    3109539.6018   13962172.2516
    3108989.3073   13958361.7216    3108760.8831   13957520.7054
#Sta/Elev= 30
  1857.7     100  1907.7    96.2  2127.7    89.8  2507.7    90.8  2707.7      88
  2827.7    91.1  2967.7    87.8  3187.7    86.5  3607.7    87.1  3867.7    93.2
  4167.7    96.5  4347.7    96.1  4547.7    88.3  4687.7    89.2  4747.7    76.1
  4847.7    83.7    4918   80.93  4931.6   71.55  4957.1   62.28  5005.1   59.02
    5039   61.22  5089.8    79.4  5247.7    75.9  5287.7    83.7  5387.7    78.3
  5467.7    83.4  5817.8    83.5  6017.8      89  6303.3  106.74  6589.2   111.4
#Mann= 5 ,-1 , 0
  1857.7     .18       0    4918     .06       0  5089.8     .18       0
  6303.3      .1       0  6589.2      .2       0
Bank Sta=4918,5089.8
XS Rating Curve= 0
Exp/Cntr=.3,.1

Type RM Length L Ch R = 1 ,61564.3 ,1353.26,1354,861.47
BEGIN DESCRIPTION:
Cross Section XS44
END DESCRIPTION:
XS GIS Cut Line= 5
     3109686.461    13962483.215    3109665.5993   13962117.8675
    3109539.6018   13960043.7539    3110380.6179   13959181.9719
    3110733.6371   13958081.3829
#Sta/Elev= 30
  1685.7    98.6  2411.6    89.7  2951.6    89.1  3041.6      85  3101.6      87
  3591.6    86.8  3691.6    90.1  3791.6      88  4159.6    88.6  4479.6    96.2
  4519.6    93.2  4599.6    70.7  4659.6    71.1  4682.8   75.91  4792.2   68.31
  4879.2   73.88  4904.7    67.3  4990.4   59.15    5054   62.71  5077.8   78.83
  5099.2   80.94  5169.6    76.8  5259.6    83.5  5333.7    81.2  5493.7    82.3
  5603.7    78.8  5803.7    79.8  6064.7   96.29  6143.7   101.2  6489.5   102.7
#Mann= 6 , 1 , 0
  1685.7      .2       0  1685.7     .18       0  4879.2     .06       0
  5077.8     .18       0  6064.7      .1       0  6489.5      .2       0
Bank Sta=4879.2,5077.8
XS Rating Curve= 0
Exp/Cntr=.3,.1

Type RM Length L Ch R = 1 ,60210.3 ,1086.1,1518.5,1252.53
BEGIN DESCRIPTION:
Cross Section XS43
END DESCRIPTION:
XS GIS Cut Line= 3
    3110380.6179   13962213.7832    3110733.6371   13960780.9409
    3111346.2291   13958943.1649
#Sta/Elev= 30
  2288.4    97.6  2806.8   86.02  3168.4    86.1  3208.4    83.4  3288.4    85.8
  3408.4    83.5  3448.4    85.8  3668.4    88.9  3904.1    90.1  3984.1    76.3
  4044.1    75.4  4124.1    80.3  4204.1    75.5  4384.1    83.5  4484.1    84.9
  4624.1    83.3  4764.1    87.8  4824.1    83.5  4886.4   86.12  4907.6   77.74
  4928.8   69.37  4970.2   60.66  5007.8   59.86    5120   65.97  5141.1   75.74
  5279.9   87.99  5304.1    90.3  5464.1    91.8  5624.1      99  5701.3    96.9
#Mann= 6 , 1 , 0
  2288.4      .2       0  2288.4     .18       0  2806.8     .18       0
  4907.6     .06       0  5141.1     .18       0  5279.9      .1       0
Bank Sta=4907.6,5141.1
XS Rating Curve= 0
Exp/Cntr=.3,.1

Type RM Length L Ch R = 1 ,58691.8 ,1079.18,958.4,467.32
BEGIN DESCRIPTION:
Cross Section XS42
END DESCRIPTION:
XS GIS Cut Line= 4
    3111626.5678   13962068.4224    3111678.4824   13961196.2575
    3112280.6915   13960137.2001     3111969.204   13958122.9145
#Sta/Elev= 30
  3640.6   100.1  3820.6   101.3  4020.6    97.8  4180.6    98.4  4514.3    94.9
  4614.3    90.8  4694.3    77.9    4886   79.61  4904.3   71.99  4937.2   60.97
  5015.8   60.32  5060.5   60.86  5109.3   65.54  5151.2   74.77  5205.5   78.41
  5214.3    80.7  5294.3    78.2  5394.3      81  5574.3    70.6  5674.3    78.3
  5752.6    79.9  5972.6    76.3  6032.6    78.7  6412.6      83  6612.6      91
    6850   88.83  7232.6    94.6  7392.6    94.5  7432.6    96.8  7770.8   101.2
#Mann= 6 , 1 , 0
  3640.6      .2       0  3640.6     .18       0  4904.3     .06       0
  5151.2     .18       0    6850      .1       0  7770.8      .2       0
Bank Sta=4904.3,5151.2
XS Rating Curve= 0
Exp/Cntr=.3,.1

Type RM Length L Ch R = 1 ,57733.4 ,1528.03,1419.3,871.33
BEGIN DESCRIPTION:
Cross Section XS41
Ineffective at Sta 4440 based on topo upstream of the cross section
END DESCRIPTION:
XS GIS Cut Line= 3
    3112945.1981   13962992.5019    3112727.1568   13959919.1589
    3111989.9698   13957956.7879
#Sta/Elev= 30
  2554.6    97.2  2694.6    93.7  3474.6    97.5  3934.6    94.6  4514.6    99.5
  4594.6    92.2  4654.6    72.3  4794.6    79.2  4854.6    72.6  4880.2   75.55
  4921.1   72.52  4935.8   75.02  4958.2   60.58  4987.2   58.57  5041.9   60.65
  5051.7   63.71  5092.3   60.54  5127.6   74.07  5194.6    77.8  5234.6    75.3
  5374.6    79.6  5815.7    83.5  6195.7    82.8  6335.7    87.9  6675.7    88.7
  6922.9   95.57  7095.7    94.1  7155.7    98.2  7275.7   100.2  7731.9     102
#Mann= 5 ,-1 , 0
  2554.6     .18       0  4935.8     .06       0  5127.6     .18       0
  6922.9      .1       0  7731.9      .2       0
#XS Ineff= 2 , 0
       0    4440     100               0
Permanent Ineff=
       F       F
Bank Sta=4935.8,5127.6
XS Rating Curve= 0
Exp/Cntr=.3,.1

Type RM Length L Ch R = 1 ,56314.1 ,2471.35,2351.8,1168.29
BEGIN DESCRIPTION:
Cross Section XS40
END DESCRIPTION:
XS GIS Cut Line= 3
    3115229.4395   13962161.8687    3113806.9801   13960043.7539
    3112021.1186   13957873.7246
#Sta/Elev= 30
  2772.2    96.7  3492.2    97.5  3572.2    95.3  3812.2    99.3  4032.2      98
  4072.2      96  4112.2    88.2  4192.2    79.8  4352.2    75.6  4412.2    75.4
  4572.2      87  4632.2    82.8  4752.2    79.9  4901.1   81.28  4930.6   74.76
  4955.6   59.12  5045.4   57.53  5071.7   71.79  5383.6    72.9  5443.6    82.3
  5483.6    84.2  6403.6    82.7  6543.6    83.7  6643.6    87.9  6983.6    86.8
  7223.6    96.4  7469.5   99.61  7563.6    98.1  8043.6   102.2    8134   100.5
#Mann= 6 , 1 , 0
  2772.2      .2       0  2772.2     .18       0  4930.6     .06       0
  5071.7     .18       0  7469.5      .1       0    8134      .2       0
Bank Sta=4930.6,5071.7
XS Rating Curve= 0
Exp/Cntr=.3,.1

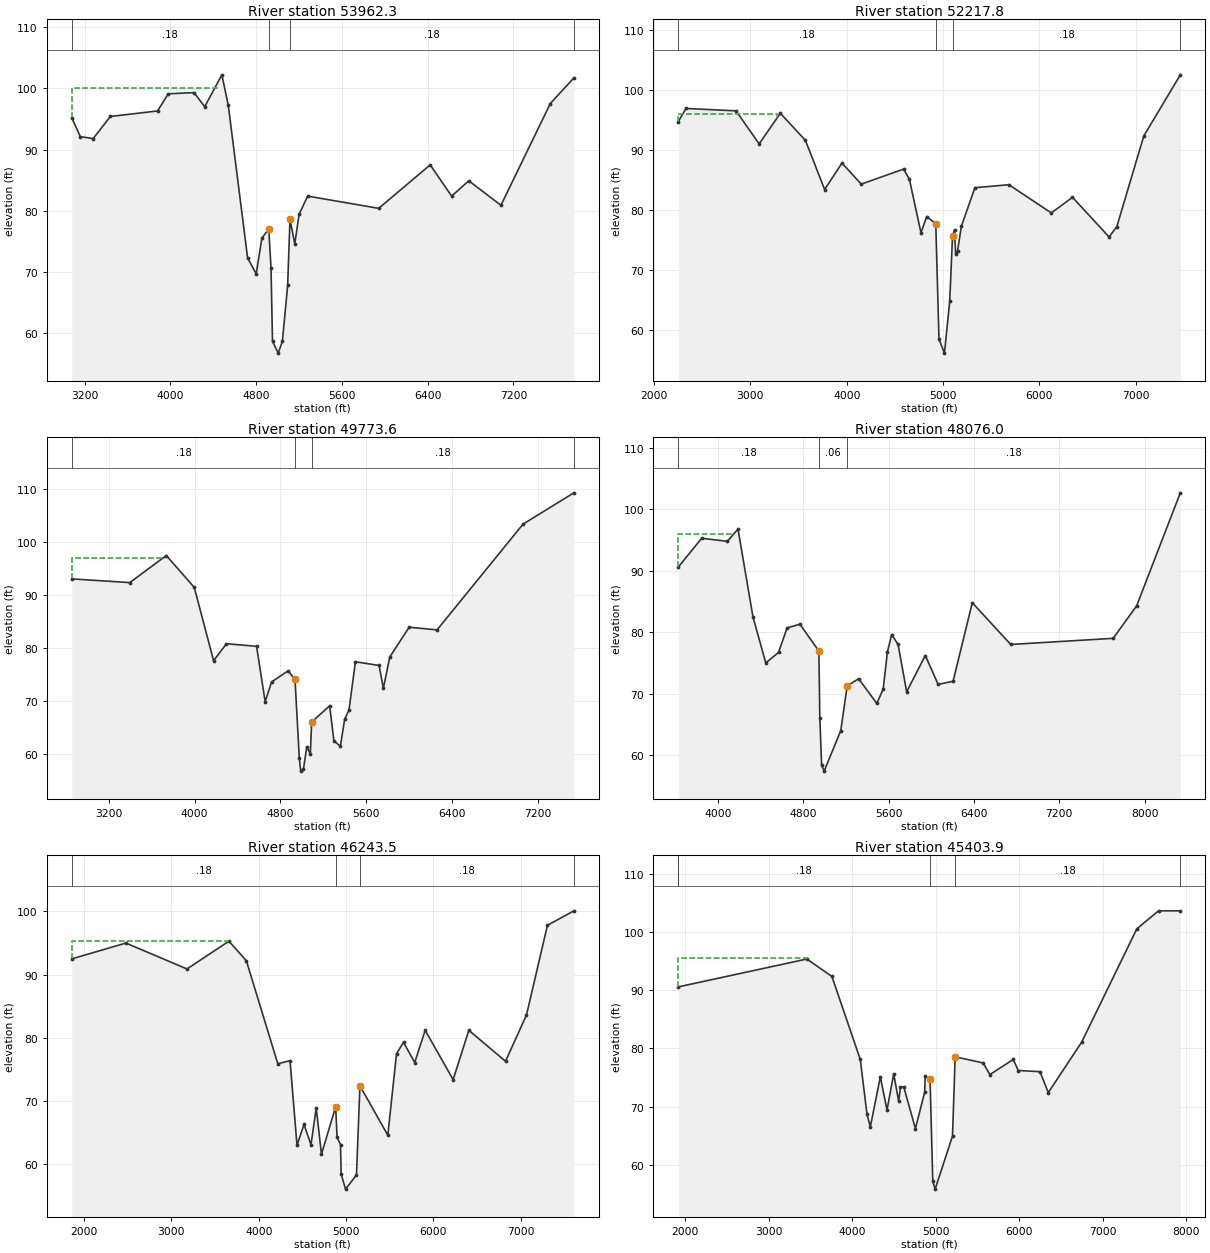
Type RM Length L Ch R = 1 ,53962.3 ,1570.7,1744.5,1909.2
BEGIN DESCRIPTION:
Cross Section XS39
Ineffective at Sta 4450 based on topo upstream of the cross section
END DESCRIPTION:
XS GIS Cut Line= 3
    3116838.7914   13959763.4152    3114294.9771   13958849.7186
    3113059.4101   13957302.6642
#Sta/Elev= 30
  3081.1    95.2  3161.1    92.1  3281.1    91.8  3441.1    95.4  3881.1    96.3
  3981.1    99.1  4221.1    99.3  4321.1      97  4481.1   102.2  4541.1    97.2
  4721.1    72.3  4801.1    69.7    4854    75.5  4918.3   77.07  4939.5   70.64
  4953.3   58.69  5006.7   56.76  5045.4   58.69  5094.6   67.83  5116.3    78.6
  5161.1    74.6  5201.1    79.4  5281.1    82.4    5944    80.4    6424    87.5
    6624    82.4    6784    84.9    7084    80.9    7544    97.5  7763.9   101.7
#Mann= 4 ,-1 , 0
  3081.1     .18       0  4918.3     .06       0  5116.3     .18       0
  7763.9      .2       0
#XS Ineff= 2 , 0
       0    4450     100               0
Permanent Ineff=
       F       F
Bank Sta=4918.3,5116.3
XS Rating Curve= 0
Exp/Cntr=.3,.1

Type RM Length L Ch R = 1 ,52217.8 ,2053.2,2444.2,3107.2
BEGIN DESCRIPTION:
Just Upstream of Confluence with J109-00-00
Cross Section XS38
Ineffective at Sta 3280 based on topo upstream of the cross section
END DESCRIPTION:
XS GIS Cut Line= 3
     3117503.298   13959763.4152    3115437.0978   13957250.7496
    3113682.3851   13956378.5847
#Sta/Elev= 30
  2250.8    94.7  2330.8    96.9  2850.8    96.5  3090.8      91  3310.8    96.1
  3570.8    91.6  3770.8    83.4  3950.8    87.8  4150.8    84.3  4590.8    86.8
  4650.8    85.1  4770.8    76.2  4830.8    78.9  4924.6   77.69    4958   58.47
  5014.7   56.15  5069.5   64.81  5098.5   75.63  5119.8    76.7  5130.8    72.6
  5150.8    73.2  5190.8    77.3  5330.8    83.7  5683.9    84.2  6123.9    79.5
  6343.9    82.1  6723.9    75.5  6803.9    77.2  7083.9    92.3  7463.4   102.5
#Mann= 4 ,-1 , 0
  2250.8     .18       0  4924.6     .06       0  5098.5     .18       0
  7463.4      .2       0
#XS Ineff= 2 , 0
       0    3280      96               0
Permanent Ineff=
       F       F
Bank Sta=4924.6,5098.5
XS Rating Curve= 0
Exp/Cntr=.3,.1

Type RM Length L Ch R = 1 ,49773.6 ,1404.42,1697.6,1119.95
BEGIN DESCRIPTION:
Just Downstream of Confluence with J109-00-00
Cross Section XS37
Ineffective at Sta 3725 based on topo upstream of the cross section
END DESCRIPTION:
XS GIS Cut Line= 3
    3118223.9485   13959358.5616    3117981.7339   13956107.7871
    3117663.0305   13954730.9884
#Sta/Elev= 30
  2857.7      93  3397.7    92.3  3737.7    97.4  3997.7    91.4  4177.7    77.6
  4297.7    80.8  4577.7    80.3  4657.7    69.9  4717.7    73.6  4871.6   75.69
  4935.5   74.06  4975.6    59.2  4988.6   56.81  5014.1   57.21  5044.9   61.37
  5078.3   60.08  5090.2   66.05  5257.7    69.1  5297.7    62.5  5357.7    61.5
  5397.7    66.6  5437.7    68.3  5497.7    77.4  5717.7    76.7  5757.7    72.4
  5817.7    78.3  5997.7    83.9  6257.5    83.4  7057.5   103.3  7530.7   109.2
#Mann= 4 ,-1 , 0
  2857.7     .18       0  4935.5     .06       0  5090.2     .18       0
  7530.7      .2       0
#XS Ineff= 2 , 0
       0    3725      97               0
Permanent Ineff=
       F       F
Bank Sta=4935.5,5090.2
XS Rating Curve= 0
Exp/Cntr=.3,.1

Type RM Length L Ch R = 1 ,48076.0 ,1412.03,1832.5,1490.88
BEGIN DESCRIPTION:
Cross Section XS36
Ineffective at Sta 4150 based on topo upstream of the cross section
END DESCRIPTION:
XS GIS Cut Line= 3
    3119664.4878   13958899.6288    3119218.3031    13956668.705
    3118096.4671   13954514.2701
#Sta/Elev= 30
  3629.8    90.6  3849.8    95.3  4089.8    94.8  4189.8    96.8  4329.8    82.5
  4449.8      75  4569.8    76.7  4649.8    80.7  4769.8    81.3  4947.7   76.92
  4956.2   66.09 4973.31   58.32  4996.8   57.37  5152.7   63.98  5212.7   71.24
  5320.1   72.42  5489.8    68.4  5549.8    70.7  5589.8    76.8  5629.8    79.6
  5689.8      78  5769.8    70.3  5944.9    76.2  6064.9    71.5  6204.9      72
  6384.9    84.8  6744.9      78  7704.9      79  7924.9    84.3  8333.9   102.7
#Mann= 3 ,-1 , 0
  3629.8     .18       0  4947.7     .06       0  5212.7     .18       0
#XS Ineff= 2 , 0
       0    4150      96               0
Permanent Ineff=
       F       F
Bank Sta=4947.7,5212.7
XS Rating Curve= 0
Exp/Cntr=.3,.1

Type RM Length L Ch R = 1 ,46243.5 ,862.53,839.6,695.6
BEGIN DESCRIPTION:
Cross Section XS35
Ineffective at Sta 3660 based on topo upstream of the cross section
END DESCRIPTION:
XS GIS Cut Line= 3
    3121423.7305   13960301.9237     3120620.598   13956579.4681
    3120480.3685   13954641.7515
#Sta/Elev= 30
  1858.7    92.5  2478.7      95  3178.7    90.9  3658.7    95.3  3858.7    92.2
  4218.7    75.9  4358.7    76.4  4438.7      63  4518.7    66.3  4598.7    63.1
  4658.7    68.9  4718.7    61.6  4881.5   69.11  4897.4   64.27    4937   63.11
  4944.4   58.45  4994.8   56.07  5119.8   58.31  5159.4   72.42  5478.7    64.6
  5578.7    77.5  5658.7    79.3  5786.8    76.1  5906.8    81.2  6226.8    73.4
  6406.8    81.2  6826.8    76.3  7066.8    83.6  7306.8    97.8  7609.6   100.1
#Mann= 4 ,-1 , 0
  1858.7     .18       0  4881.5     .06       0  5159.4     .18       0
  7609.6      .2       0
#XS Ineff= 2 , 0
       0    3660    95.3               0
Permanent Ineff=
       F       F
Bank Sta=4881.5,5159.4
XS Rating Curve= 0
Exp/Cntr=.3,.1

Type RM Length L Ch R = 1 ,45403.9 ,1626.58,1479.5,921.68
BEGIN DESCRIPTION:
Cross Section XS34
END DESCRIPTION:
XS GIS Cut Line= 3
    3122456.3295   13959970.4722    3121614.9525   13957204.1267
    3120582.3536   13954259.3074
#Sta/Elev= 30
  1917.3    90.6  3457.3    95.4  3757.3    92.4  4097.3    78.1  4177.3    68.7
  4217.3    66.5  4337.3    75.1  4417.3    69.4  4497.3    75.6  4557.3    70.9
  4577.3    73.3  4617.3    73.4  4757.3    66.2  4868.8    72.5    4874    75.2
  4932.7   74.66 4965.61    57.1  4993.8   55.77  5201.6   64.92  5233.4   78.56
  5568.8    77.5  5648.8    75.5  5928.8    78.1  5988.8    76.2  6248.8      76
  6348.8    72.4  6748.8    81.1  7408.8   100.6  7668.8   103.7  7929.4   103.7
#Mann= 5 , 1 , 0
  1917.3      .2       0  1917.3     .18       0  4932.7     .06       0
  5233.4     .18       0  7929.4      .2       0
#XS Ineff= 2 , 0
       0    3456    95.5               0
Permanent Ineff=
       F       F
Bank Sta=4932.7,5233.4
XS Rating Curve= 0
Exp/Cntr=.3,.1