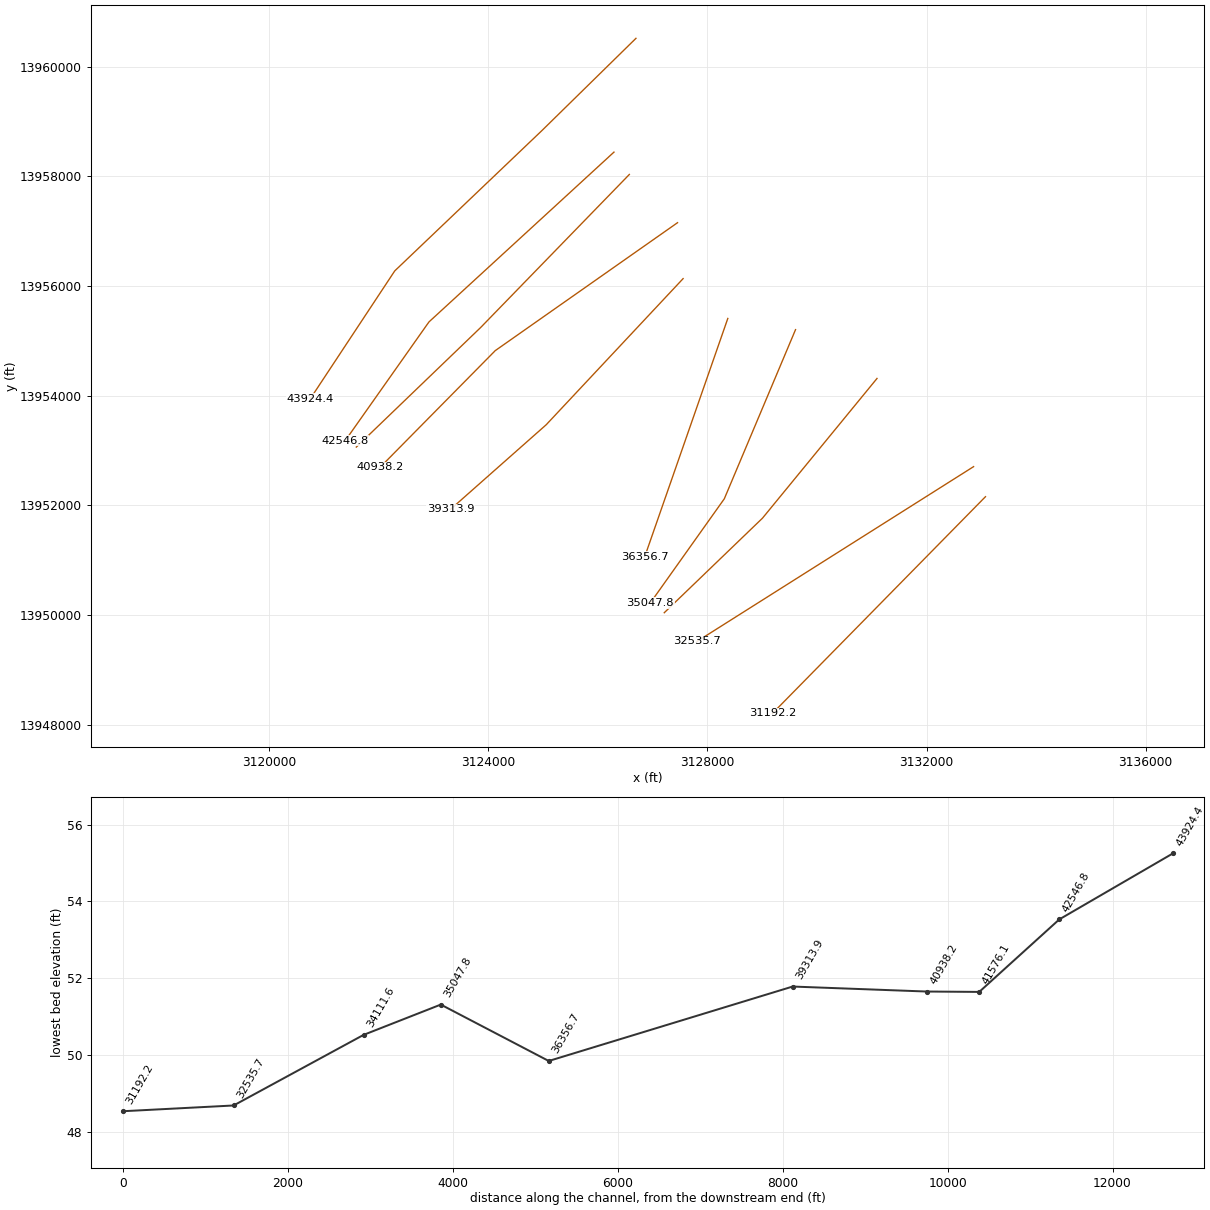
HEC-RAS study J100-00-00.prj: J100-00-00

--- J100-00-00.g01 (geometry) --- (continued)

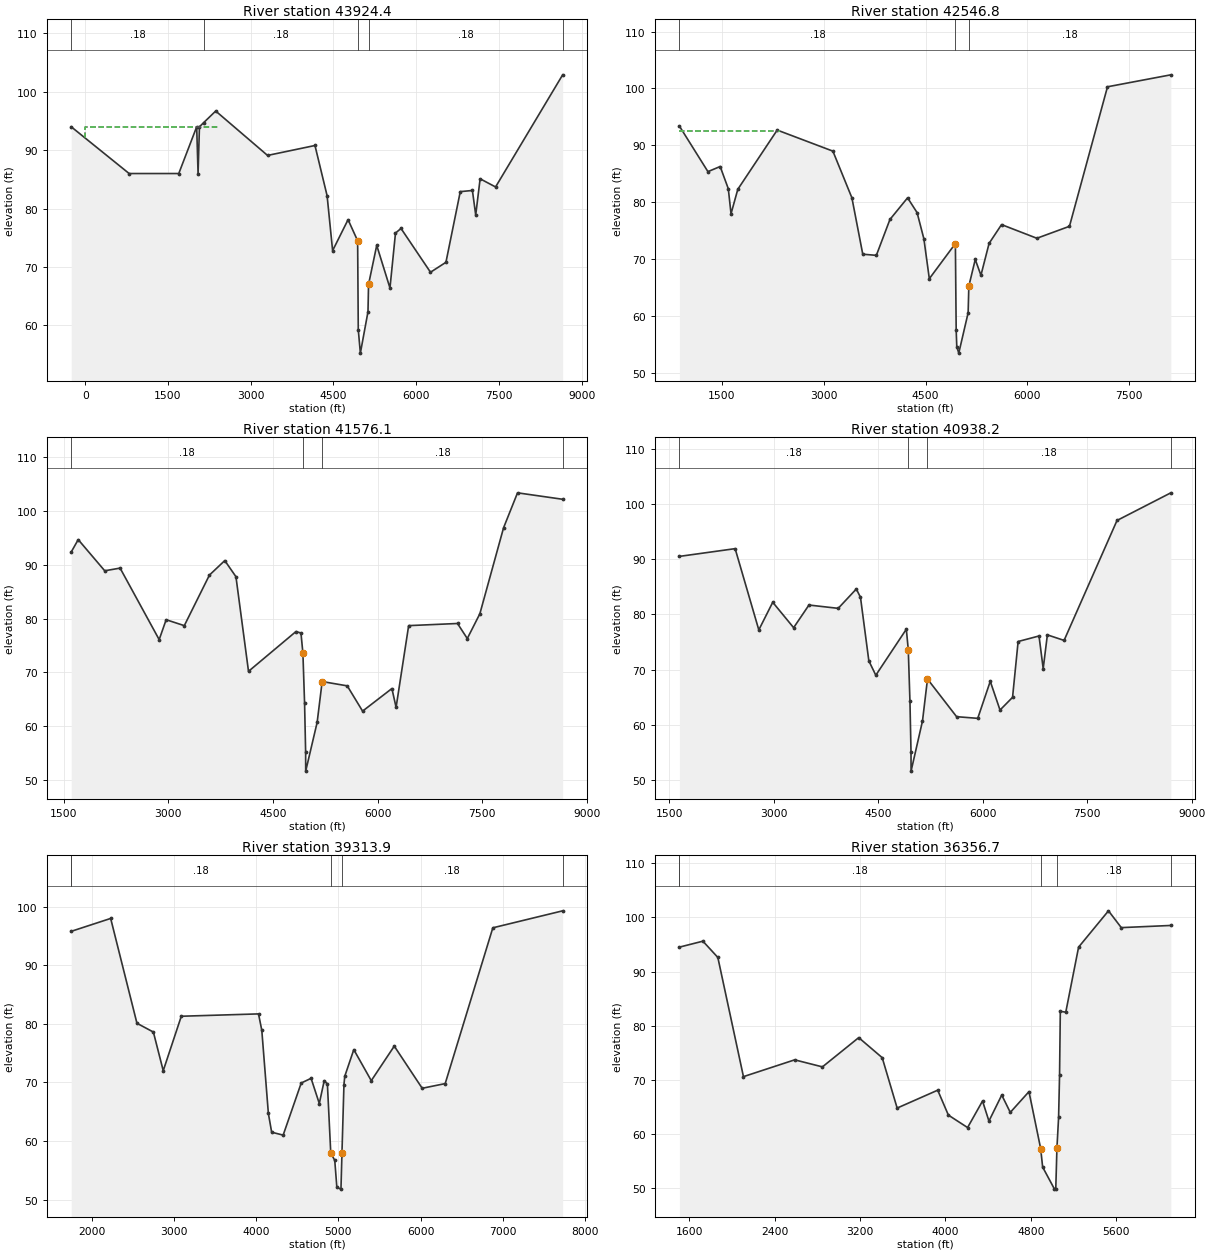
Type RM Length L Ch R = 1 ,43924.4 ,1191.89,1377.6,1158.99
BEGIN DESCRIPTION:
Cross Section XS33
END DESCRIPTION:
XS GIS Cut Line= 4
     3126694.686   13960515.5995    3124980.4604   13958835.8881
    3122290.6037   13956273.5128    3120748.0793    13953940.604
#Sta/Elev= 30
  -254.8      94   795.2      86  1695.2      86  2020.2      94  2045.2      86
  2070.2      94  2145.2    94.7  2365.2    96.7  3305.2    89.1  4165.2    90.8
  4385.2    82.2  4485.2    72.8  4765.2    78.1  4938.8   74.49  4950.5   59.27
  4988.6   55.25  5126.6   62.34  5136.8   67.01  5285.2    73.7  5525.2    66.4
  5625.2    75.8  5725.2    76.6  6260.2    69.1  6540.2    70.8  6800.2    82.9
  7020.2    83.1  7080.2    78.9  7160.2    85.1  7440.2    83.7  8656.9   102.9
#Mann= 5 ,-1 , 0
  -254.8     .18       0  2145.2     .18       0  4938.8     .06       0
  5136.8     .18       0  8656.9      .2       0
#XS Ineff= 2 , 0
       0    2400      94               0
Permanent Ineff=
       F       F
Bank Sta=4938.8,5136.8
XS Rating Curve= 0
Exp/Cntr=.3,.1

Type RM Length L Ch R = 1 ,42546.8 ,678.36,970.7,761.73
BEGIN DESCRIPTION:
Cross Section XS31
Ineffective at Sta 2360 based on topo upstream of the cross section
END DESCRIPTION:
XS GIS Cut Line= 3
    3126293.5183   13958440.6959    3122915.2624   13955342.8989
    3121385.4861   13953175.7159
#Sta/Elev= 30
     875    93.4    1295    85.4    1475    86.3    1595    82.4    1635      78
    1735    82.3    2315    92.7    3135      89    3415    80.8    3575    70.9
    3775    70.7    3975      77    4235    80.8    4375    78.2    4475    73.6
    4555    66.6  4938.8   72.77  4950.5   57.55  4959.4   54.67  4988.6   53.53
  5126.6   60.62  5136.8   65.29  5231.4   69.98    5315    67.2    5435    72.8
  5618.6    76.1  6138.6    73.7  6618.6    75.8  7178.6   100.3  8111.3   102.4
#Mann= 3 ,-1 , 0
     875     .18       0  4938.8     .06       0  5136.8     .18       0
#XS Ineff= 2 , 0
       0    2360    92.5               0
Permanent Ineff=
       F       F
Bank Sta=4938.8,5136.8
XS Rating Curve= 0
Exp/Cntr=.3,.1

Type RM Length L Ch R = 1 ,41576.1 ,761.2,637.9,516.63
BEGIN DESCRIPTION:
Cross Section XS32
Ineffective at Sta 3770 based on topo upstream of the cross section
END DESCRIPTION:
XS GIS Cut Line= 3
    3126573.9773   13958032.7555    3123858.6244   13955240.9138
    3121589.4563   13953060.9826
#Sta/Elev= 30
  1610.5    92.4  1710.5    94.7  2090.5    88.9  2310.5    89.4  2870.5    76.1
  2970.5    79.8  3230.5    78.7  3590.5    88.1  3810.5    90.8  3970.5    87.8
  4150.5    70.2  4830.5    77.6  4902.1   77.32  4929.9   73.59  4953.9   64.26
    4969   55.13  4969.9   51.64    5134   60.71  5205.8    68.3  5565.1    67.5
  5785.1    62.8  6205.1      67  6265.1    63.5  6445.1    78.7  7145.1    79.1
  7285.1    76.3  7465.1    80.9  7805.1    96.9  8005.1   103.4  8651.7   102.2
#Mann= 4 ,-1 , 0
  1610.5     .18       0  4929.9     .06       0  5205.8     .18       0
  8651.7      .2       0
#XS Ineff= 2 , 0
       0    3770      90               0
Permanent Ineff=
       F       F
Bank Sta=4929.9,5205.8
XS Rating Curve= 0
Exp/Cntr=.3,.1

Type RM Length L Ch R = 1 ,40938.2 ,1377.67,1624.3,1617.41
BEGIN DESCRIPTION:
Cross Section XS30
Ineffective at Sta 4170 based on topo upstream of the cross section
END DESCRIPTION:
XS GIS Cut Line= 3
    3127453.5987   13957153.1342    3124126.3353   13954820.2254
    3122022.8929   13952691.2867
#Sta/Elev= 30
  1643.5    90.5  2443.6    91.9  2783.6    77.2  2983.6    82.2  3283.6    77.6
  3503.6    81.7  3923.6    81.1  4183.6    84.6  4243.6    83.1  4363.6    71.6
  4463.6      69  4902.1   77.33  4929.9    73.6  4953.9   64.27    4969   55.14
  4969.9   51.65    5134   60.72  5205.8   68.31  5623.6    61.5  5927.2    61.2
  6107.2    67.9  6247.2    62.7  6427.2      65  6507.2    75.1  6807.2    76.1
  6867.2    70.2  6927.2    76.3  7167.2    75.3  7927.2      97    8700     102
#Mann= 4 ,-1 , 0
  1643.5     .18       0  4929.9     .06       0  5205.8     .18       0
    8700      .2       0
#XS Ineff= 2 , 0
       0    4170      84               0
Permanent Ineff=
       F       F
Bank Sta=4929.9,5205.8
XS Rating Curve= 0
Exp/Cntr=.3,.1

Type RM Length L Ch R = 1 ,39313.9 ,2068.33,2957.2,2657.62
BEGIN DESCRIPTION:
Cross Section XS29
END DESCRIPTION:
XS GIS Cut Line= 3
    3127555.5837   13956133.2833    3125056.9492    13953468.923
    3123310.4546   13951926.3986
#Sta/Elev= 30
  1747.7    95.8  2227.7      98  2547.7    80.1  2747.7    78.6  2867.7      72
  3087.7    81.3  4027.7    81.7  4067.7    78.9  4147.7    64.7  4187.7    61.5
  4327.7      61  4547.7    69.9  4667.7    70.7  4767.7    66.4  4827.7    70.3
  4866.2   69.75  4907.1   57.98    4956   56.68  4981.6   52.07  5031.4   51.78
  5043.7   57.99  5067.8   69.62  5077.5   71.04  5187.7    75.6  5400.4    70.3
  5680.4    76.2  6020.4      69  6300.4    69.8  6880.4    96.4  7730.5    99.3
#Mann= 5 , 1 , 0
  1747.7      .2       0  1747.7     .18       0  4907.1     .06       0
  5043.7     .18       0  7730.5      .2       0
Bank Sta=4907.1,5043.7
XS Rating Curve= 0
Exp/Cntr=.3,.1

Type RM Length L Ch R = 1 ,36356.7 ,1167.66,1308.9,1210.95
BEGIN DESCRIPTION:
Cross Section XS28
END DESCRIPTION:
XS GIS Cut Line= 2
    3128371.4644   13955406.6396    3126854.4363   13951059.5254
#Sta/Elev= 30
  1508.8    94.5  1728.8    95.6  1868.8    92.6  2108.8    70.6  2588.8    73.7
  2848.8    72.4  3188.8    77.8  3408.8    74.1  3548.8    64.8  3928.8    68.1
  4028.8    63.5  4208.8    61.2  4348.8    66.1  4408.8    62.4  4528.8    67.2
  4608.8      64  4783.9   67.83  4893.4   57.33    4912   53.91  5022.9   49.84
    5035   49.88  5045.8    57.4  5061.4   63.06  5070.6   70.97  5077.5   82.65
  5128.8    82.5  5248.8    94.5  5528.8   101.2  5648.8    98.1    6113    98.5
#Mann= 5 , 1 , 0
  1508.8      .2       0  1508.8     .18       0  4893.4     .06       0
  5045.8     .18       0    6113      .2       0
Bank Sta=4893.4,5045.8
XS Rating Curve= 0
Exp/Cntr=.3,.1

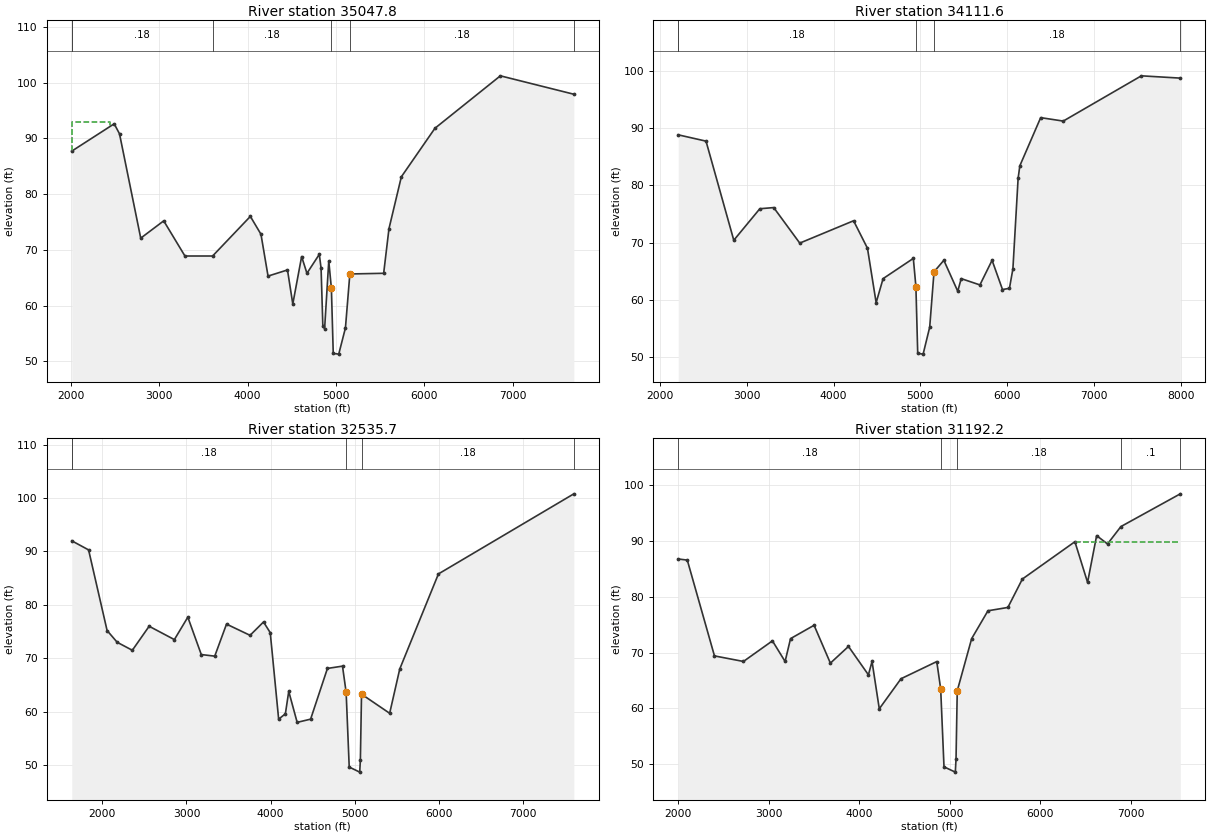
Type RM Length L Ch R = 1 ,35047.8 ,1158.26,936.2,779.62
BEGIN DESCRIPTION:
Cross Section XS27
END DESCRIPTION:
XS GIS Cut Line= 3
    3129608.0336   13955202.6694    3128307.7238   13952117.6206
    3126956.4214   13950218.1484
#Sta/Elev= 30
  2011.3    87.7  2491.3    92.6  2551.3    90.8  2791.3    72.1  3051.3    75.2
  3291.3    68.9  3604.3    68.9  4031.3      76  4151.3    72.8  4231.3    65.3
  4451.3    66.4  4511.3    60.3  4611.3    68.8  4671.3    65.8  4811.3    69.2
  4831.3    66.7  4851.3    56.3  4871.3    55.9  4918.3   68.02  4947.9    63.1
  4968.9   51.44  5031.1   51.31  5106.9   56.02  5156.7   65.68  5539.2    65.8
  5599.2    73.8  5739.2    83.1  6119.2    91.8  6859.2   101.2  7690.3    97.9
#Mann= 6 , 1 , 0
  2011.3      .2       0  2011.3     .18       0  3604.3     .18       0
  4947.9     .06       0  5156.7     .18       0  7690.3      .2       0
#XS Ineff= 2 , 0
       0    2445      93               0
Permanent Ineff=
       F       F
Bank Sta=4947.9,5156.7
XS Rating Curve= 0
Exp/Cntr=.3,.1

Type RM Length L Ch R = 1 ,34111.6 ,1696.86,1575.9,1260.4
BEGIN DESCRIPTION:
Cross Section XS26
END DESCRIPTION:
XS GIS Cut Line= 3
    3131095.4898   13954312.3837    3129005.1241   13951764.7505
    3127211.3841   13950039.6745
#Sta/Elev= 30
  2209.9    88.8  2529.9    87.7  2849.9    70.4  3149.9    75.9  3309.9    76.1
  3609.9    69.9  4229.9    73.8  4389.9      69  4489.9    59.5  4569.9    63.7
  4918.3   67.23  4947.9   62.31  4968.9   50.65  5031.1   50.52  5106.9   55.23
  5156.7   64.89  5269.9    66.9  5429.9    61.5  5469.9    63.7  5685.4    62.6
  5825.4    66.9  5945.4    61.8  6025.4      62  6065.4    65.4  6125.4    81.2
  6145.4    83.4  6385.4    91.8  6645.4    91.2  7545.4    99.1    7994    98.7
#Mann= 5 , 1 , 0
  2209.9      .2       0  2209.9     .18       0  4947.9     .06       0
  5156.7     .18       0    7994      .2       0
Bank Sta=4947.9,5156.7
XS Rating Curve= 0
Exp/Cntr=.3,.1

Type RM Length L Ch R = 1 ,32535.7 ,1059.72,1343.5,1400.37
BEGIN DESCRIPTION:
Cross Section XS25
END DESCRIPTION:
XS GIS Cut Line= 2
    3132858.8082   13952704.0349    3127810.5465   13949517.0009
#Sta/Elev= 30
  1636.3      92  1836.3    90.3  2056.3    75.2  2176.3      73  2356.3    71.5
  2556.3      76  2856.3    73.5  3016.3    77.7  3176.3    70.7  3336.3    70.4
  3476.3    76.4  3756.3    74.3  3916.3    76.8  3996.3    74.8  4096.3    58.6
  4176.3    59.6  4216.3    63.8  4316.3      58  4476.3    58.6  4676.3    68.1
  4855.5   68.53  4898.8   63.63  4935.4   49.63  5060.4   48.68  5068.2   51.03
  5081.7   63.28  5416.3    59.7  5536.3      68  5996.3    85.8  7606.4   100.8
#Mann= 5 , 1 , 0
  1636.3      .2       0  1636.3     .18       0  4898.8     .06       0
  5081.7     .18       0  7606.4      .2       0
Bank Sta=4898.8,5081.7
XS Rating Curve= 0
Exp/Cntr=.3,.1

Type RM Length L Ch R = 1 ,31192.2 ,1045.4,1499.4,1362.95
BEGIN DESCRIPTION:
Cross Section XS24
Ineffective at Sta 6350 based on topo upstream of the cross section
END DESCRIPTION:
XS GIS Cut Line= 2
    3133075.5265    13952155.865    3129187.3451    13948203.943
#Sta/Elev= 30
  2000.8    86.8  2100.8    86.6  2400.8    69.4  2720.8    68.4  3040.8    72.1
  3180.8    68.4  3240.8    72.5  3500.8    74.9  3680.8    68.1  3880.8    71.1
  4100.8      66  4140.8    68.4  4220.8    59.9  4460.8    65.3  4855.5   68.38
  4898.8   63.48  4935.4   49.48  5060.4   48.53  5068.2   50.88  5081.7   63.13
  5240.8    72.5  5420.8    77.5  5640.8    78.1  5800.8    83.2  6380.8    89.9
  6520.8    82.6  6620.8      91  6740.8    89.5  6888.8   92.62  7544.8    98.5
#Mann= 5 ,-1 , 0
  2000.8     .18       0  4898.8     .06       0  5081.7     .18       0
  6888.8      .1       0  7544.8      .2       0
#XS Ineff= 2 , 0
       0                    6380       0    89.9
Permanent Ineff=
       F       F
Bank Sta=4898.8,5081.7
XS Rating Curve= 0
Exp/Cntr=.3,.1