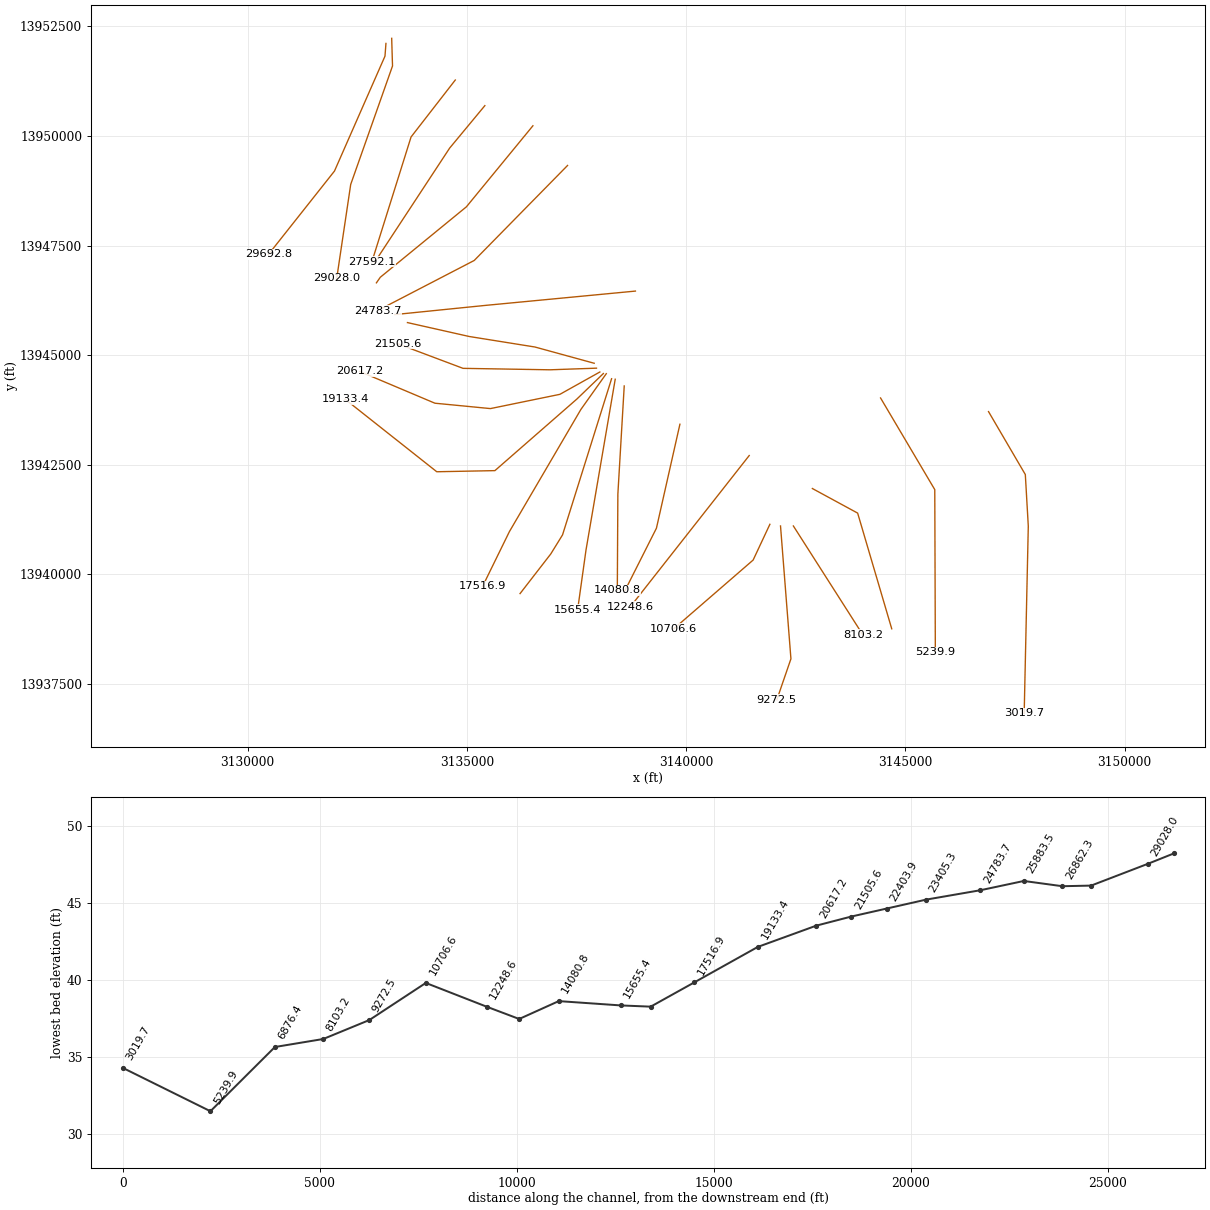
HEC-RAS study J100-00-00.prj: J100-00-00

--- J100-00-00.g01 (geometry) --- (continued)

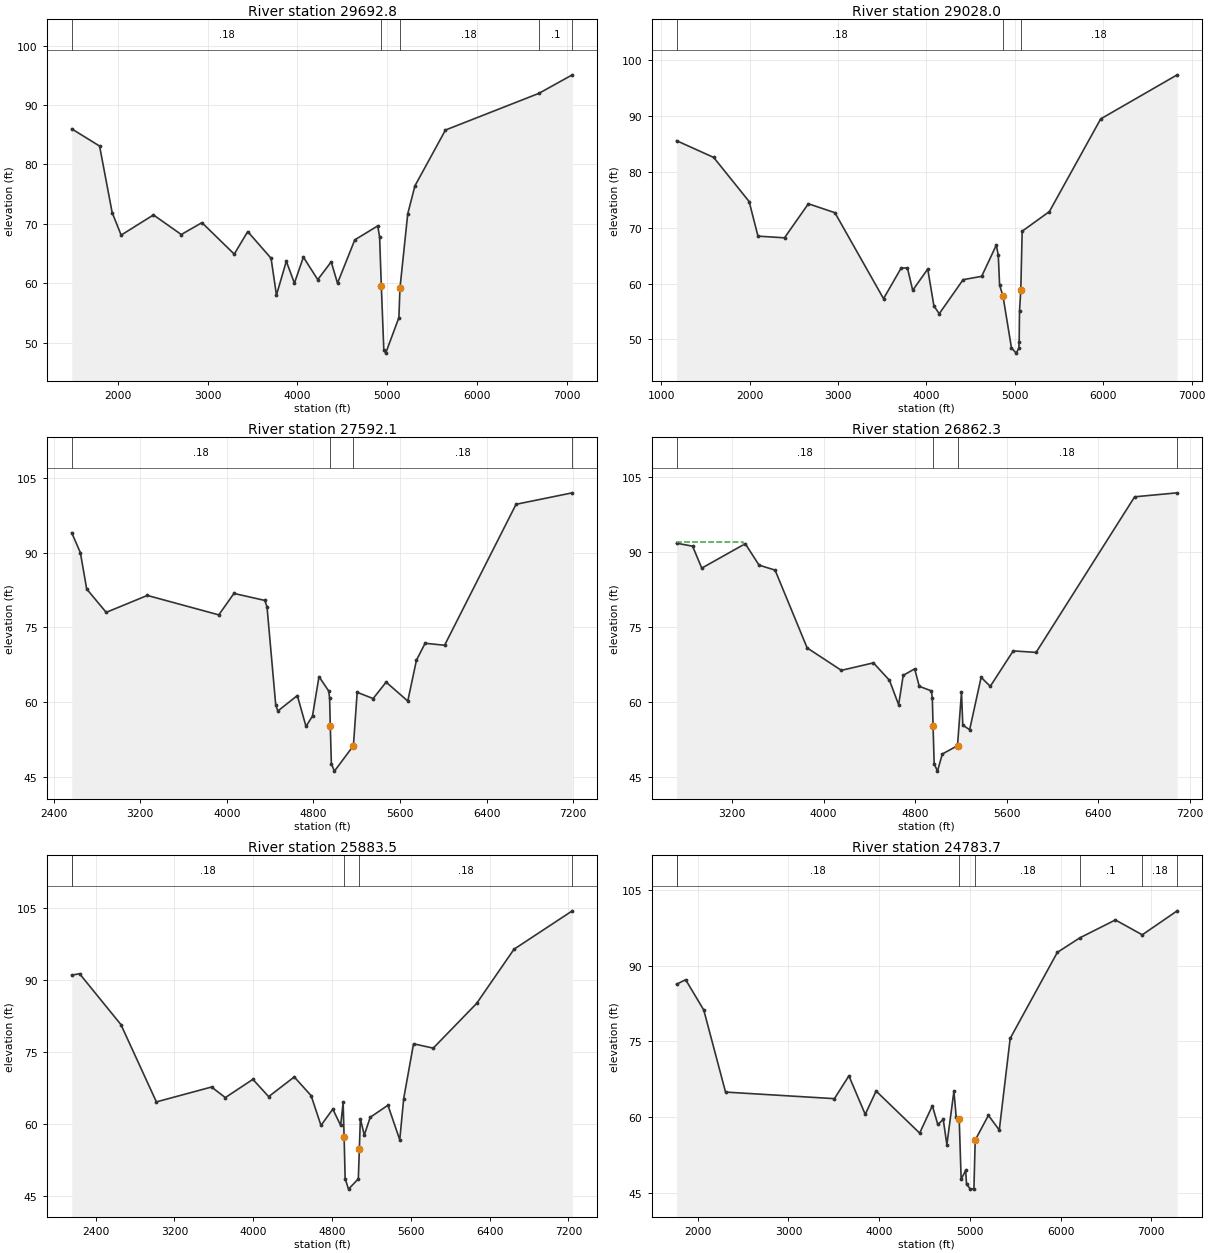
Type RM Length L Ch R = 1 ,29692.8 ,394.77,664.8,830.6
BEGIN DESCRIPTION:
Cross Section XS23
END DESCRIPTION:
XS GIS Cut Line= 4
    3133152.7267    13952108.787    3133130.8309   13951818.8754
    3131979.1868   13949198.2976    3130474.9068   13947298.8253
#Sta/Elev= 30
    1485      86  1795.7    83.1  1935.7    71.9  2035.7    68.1  2395.7    71.5
  2705.7    68.2  2935.7    70.2  3295.7    64.9  3445.7    68.7  3705.7    64.2
  3765.7      58  3875.7    63.7  3965.7      60  4065.7    64.4  4225.7    60.6
  4375.7    63.6  4445.7      60  4638.2    67.3  4893.7   69.65  4914.8   67.78
  4933.9   59.46  4961.6   48.79  4982.5   48.22  5129.5    54.2  5141.3   59.13
  5228.2    71.7  5308.2    76.4  5648.2    85.8  6687.7   91.97  7061.2    95.1
#Mann= 5 ,-1 , 0
    1485     .18       0  4933.9     .06       0  5141.3     .18       0
  6687.7      .1       0  7061.2      .2       0
Bank Sta=4933.9,5141.3
XS Rating Curve= 0
Exp/Cntr=.3,.1

Type RM Length L Ch R = 1 ,29028.0 ,984.49,1435.9,1216.74
BEGIN DESCRIPTION:
Cross Section XS22
END DESCRIPTION:
XS GIS Cut Line= 4
    3133283.6804   13952225.1903    3133302.6945   13951594.8089
    3132348.8827   13948892.3423    3132030.1794   13946750.6555
#Sta/Elev= 30
  1174.5    85.6  1594.6    82.6  1995.3    74.7  2095.3    68.5  2395.3    68.2
  2665.3    74.3  2965.3    72.7  3515.3    57.3  3715.3    62.8  3785.3    62.8
  3845.3    58.8  4015.3    62.6  4085.3      56  4145.3    54.6  4415.3    60.7
  4625.3    61.3  4791.1    66.9  4813.1   65.04  4828.2   59.73  4866.8   57.72
    4962   48.49    5015   47.54  5045.8   48.41  5049.4   49.54  5053.2   55.06
  5067.8   58.86  5083.2   69.38  5391.1    72.9  5971.1    89.5  6836.4    97.4
#Mann= 3 ,-1 , 0
  1174.5     .18       0  4866.8     .06       0  5067.8     .18       0
Bank Sta=4866.8,5067.8
XS Rating Curve= 0
Exp/Cntr=.3,.1

Type RM Length L Ch R = 1 ,27592.1 ,787.96,729.8,524.79
BEGIN DESCRIPTION:
Cross Section XS21
END DESCRIPTION:
XS GIS Cut Line= 3
    3134734.0258   13951274.3019    3133725.6814   13949975.9338
    3132833.3119   13947133.0996
#Sta/Elev= 30
  2567.5      94  2647.5      90    2706    82.7    2886      78    3266    81.4
    3926    77.5    4066    81.8  4351.5    80.4  4371.5    79.1  4451.5    59.5
  4471.5    58.2  4651.5    61.3  4731.5    55.1  4791.5    57.2  4851.5    65.1
  4941.1   62.22  4949.6   60.77  4955.8   55.24  4965.7   47.59  4994.3   46.13
  5169.3   51.24  5204.1   61.95  5351.5    60.7  5471.5      64  5671.5    60.2
  5751.5    68.4  5831.5    71.8  6011.5    71.4  6671.5    99.7  7191.1     102
#Mann= 4 ,-1 , 0
  2567.5     .18       0  4955.8     .06       0  5169.3     .18       0
  7191.1      .2       0
Bank Sta=4955.8,5169.3
XS Rating Curve= 0
Exp/Cntr=.3,.1

Type RM Length L Ch R = 1 ,26862.3 ,1096.48,978.8,850.67
BEGIN DESCRIPTION:
Cross Section XS20
END DESCRIPTION:
XS GIS Cut Line= 3
    3135408.4353   13950689.8294    3134605.3027   13949720.9711
    3132897.0526   13947120.3514
#Sta/Elev= 30
  2716.9    91.8  2856.9    91.2  2936.9    86.8  3316.9    91.7  3436.9    87.4
  3576.9    86.4  3856.9    70.8  4155.4    66.3  4435.4    67.8  4575.4    64.3
  4655.4    59.4  4695.4    65.3  4795.4    66.6  4835.4    63.1  4941.1   62.18
  4949.6   60.73  4955.8    55.2  4965.7   47.55  4994.3   46.09  5036.8   49.52
  5169.3    51.2  5204.1   61.91  5215.4    55.3  5275.4    54.4  5375.4    64.9
  5455.4    63.1  5655.4    70.2  5855.4    69.9  6715.4   101.1  7086.8   101.9
#Mann= 4 ,-1 , 0
  2716.9     .18       0  4955.8     .06       0  5169.3     .18       0
  7086.8      .2       0
#XS Ineff= 2 , 0
       0    3296      92               0
Permanent Ineff=
       F       F
Bank Sta=4955.8,5169.3
XS Rating Curve= 0
Exp/Cntr=.3,.1

Type RM Length L Ch R = 1 ,25883.5 ,1058.35,1099.8,982.23
BEGIN DESCRIPTION:
Cross Section XS19
END DESCRIPTION:
XS GIS Cut Line= 4
     3136504.775   13950230.8965    3134987.7468   13948382.4169
    3133024.5339   13946776.1518     3132935.297   13946648.6704
#Sta/Elev= 30
  2156.3      91  2236.3    91.3  2656.3    80.7  3016.3    64.6  3576.3    67.7
  3716.3    65.5  3996.3    69.3  4156.3    65.7  4416.3    69.8  4587.6    65.9
  4687.6    59.7  4807.6    63.1  4887.6    59.7  4912.6   64.49  4922.6   57.22
  4933.1   48.63  4967.2   46.43  5066.9   48.57  5077.1    54.7  5087.7   61.07
  5127.6    57.7  5187.6    61.4  5367.6    63.9  5487.6    56.7  5527.6    65.3
  5627.6    76.7  5827.6    75.8  6267.6    85.1  6647.6    96.4  7239.8   104.4
#Mann= 5 , 1 , 0
  2156.3      .2       0  2156.3     .18       0  4922.6     .06       0
  5077.1     .18       0  7239.8      .2       0
Bank Sta=4922.6,5077.1
XS Rating Curve= 0
Exp/Cntr=.3,.1

Type RM Length L Ch R = 1 ,24783.7 ,1986.7,1378.4,1051.7
BEGIN DESCRIPTION:
Cross Section XS18
END DESCRIPTION:
XS GIS Cut Line= 3
    3137295.1594   13949325.7789    3135166.2207   13947158.5959
    3132963.7541   13946016.2448
#Sta/Elev= 30
  1766.2    86.3  1866.2    87.2  2066.2    81.2  2306.2      65  3506.2    63.7
  3666.2    68.2  3846.2    60.6  3966.2    65.2  4446.2    56.9  4586.2    62.3
  4646.2    58.6  4706.2    59.6  4746.2    54.6  4824.1    65.2  4849.1   60.03
  4882.3   59.65  4903.6   47.78  4953.3   49.53  4963.1    46.8    5006   45.83
  5044.4   45.92  5058.6   55.52  5204.1    60.4  5324.1    57.5  5444.1    75.6
  5964.1    92.6  6212.8   95.47  6604.1      99  6900.4   96.06  7285.2   100.8
#Mann= 7 , 1 , 0
  1766.2      .2       0  1766.2     .18       0  4882.3     .06       0
  5058.6     .18       0  6212.8      .1       0  6900.4     .18       0
  7285.2      .2       0
Bank Sta=4882.3,5058.6
XS Rating Curve= 0
Exp/Cntr=.3,.1

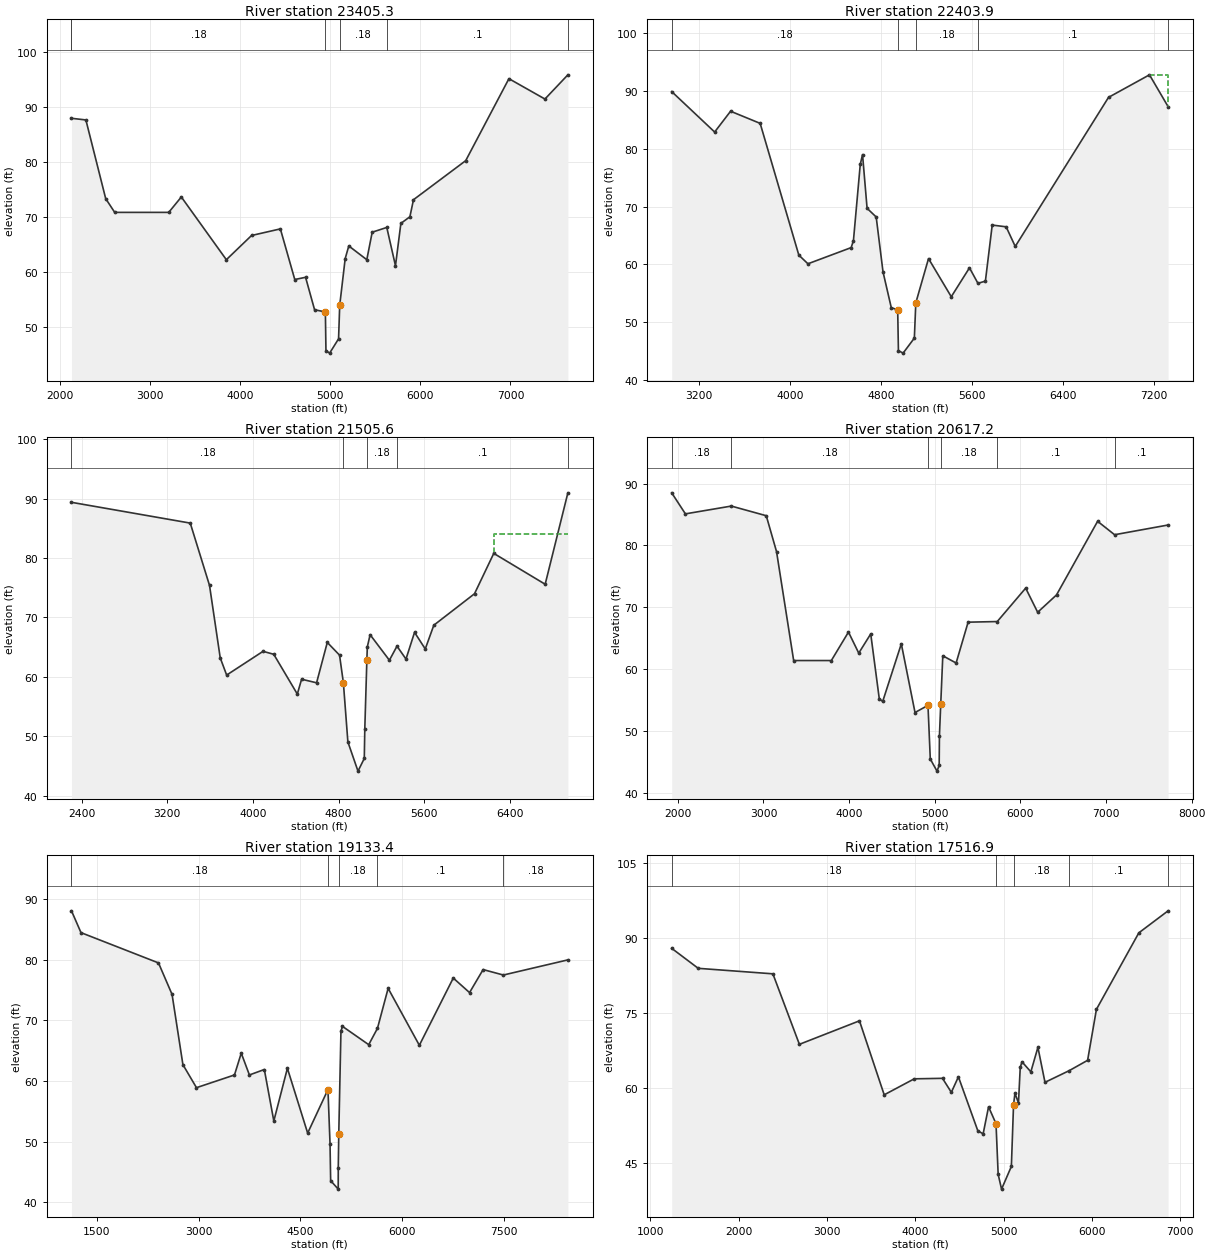
Type RM Length L Ch R = 1 ,23405.3 ,1180.71,1001.4,843.73
BEGIN DESCRIPTION:
Cross Section XS17
END DESCRIPTION:
XS GIS Cut Line= 3
    3138842.9077   13946460.4475    3135419.9339   13946133.8279
    3133355.6977   13945924.7913
#Sta/Elev= 30
  2124.7    87.9  2284.7    87.6  2504.7    73.3  2604.7    70.8  3204.7    70.8
  3344.7    73.6  3844.7    62.2  4124.7    66.6  4444.7    67.8  4604.7    58.6
  4724.7      59  4824.7    53.1  4944.6   52.71    4951   45.66  4992.1   45.22
  5091.1   47.82  5103.9   53.92  5164.7    62.4  5204.7    64.7  5404.7    62.2
  5464.7    67.2  5626.7   68.06  5723.2    61.1  5783.2    68.8  5883.2      70
  5923.2    73.1  6503.2    80.2  6983.2    95.1  7383.2    91.4    7638    95.8
#Mann= 6 , 1 , 0
  2124.7      .2       0  2124.7     .18       0  4944.6     .06       0
  5103.9     .18       0  5626.7      .1       0    7638      .2       0
Bank Sta=4944.6,5103.9
XS Rating Curve= 0
Exp/Cntr=.3,.1

Type RM Length L Ch R = 1 ,22403.9 ,764.03,898.3,923.8
BEGIN DESCRIPTION:
Cross Section XS16
END DESCRIPTION:
XS GIS Cut Line= 4
    3137902.1459   13944814.2722    3136552.2332   13945184.5681
    3135051.4875   13945424.8494     3133643.123   13945741.8843
#Sta/Elev= 30
    2958    89.9  3335.6    82.9  3475.6    86.5  3735.6    84.4  4075.6    61.6
  4155.6    60.1  4535.6    62.9  4555.6    64.1  4615.6    77.3  4635.6      79
  4675.6    69.7  4755.6    68.2  4815.6    58.7  4888.2   52.51  4944.6   52.13
    4951   45.08  4992.1   44.64  5091.1   47.24  5103.9   53.34  5215.6      61
  5415.6    54.4  5575.6    59.4  5650.1   56.72  5715.6    57.1  5775.6    66.8
    5898    66.5    5978    63.1    6798    88.9    7158    92.8  7321.6    87.3
#Mann= 5 ,-1 , 0
    2958     .18       0  4944.6     .06       0  5103.9     .18       0
  5650.1      .1       0  7321.6      .2       0
#XS Ineff= 2 , 0
       0                    7155       0    92.8
Permanent Ineff=
       F       F
Bank Sta=4944.6,5103.9
XS Rating Curve= 0
Exp/Cntr=.3,.1

Type RM Length L Ch R = 1 ,21505.6 ,855.77,888.4,937.65
BEGIN DESCRIPTION:
Cross Section XS15
Ineffective at Sta 6250 based on ineffective flow line
END DESCRIPTION:
XS GIS Cut Line= 4
    3137954.6013   13944702.3675    3136895.0826   13944665.1434
     3134911.258   13944698.2057    3133421.0216   13945258.4873
#Sta/Elev= 30
  2305.9    89.4  3415.2    85.9  3595.2    75.4  3695.2    63.2  3755.2    60.3
  4095.2    64.3  4195.2    63.8  4415.2    57.1  4455.2    59.6  4595.2      59
  4695.2    65.8  4809.5   63.66  4845.4   59.02  4887.5   49.04  4981.9   44.12
  5040.7   46.25  5045.6   51.28  5064.9   62.87    5069   65.04  5095.2    67.1
  5275.2    62.8  5346.2   65.17  5430.2      63  5510.2    67.5  5610.2    64.7
  5690.2    68.7  6070.2      74  6250.2    80.8  6730.2    75.6  6942.3      91
#Mann= 5 ,-1 , 0
  2305.9     .18       0  4845.4     .06       0  5064.9     .18       0
  5346.2      .1       0  6942.3      .2       0
#XS Ineff= 2 , 0
       0                    6250       0      84
Permanent Ineff=
       F       F
Bank Sta=4845.4,5064.9
XS Rating Curve= 0
Exp/Cntr=.3,.1

Type RM Length L Ch R = 1 ,20617.2 ,1174.69,1483.8,1497.5
BEGIN DESCRIPTION:
Cross Section XS14 - No topographic relief beyond limits of cross section
END DESCRIPTION:
XS GIS Cut Line= 5
    3138031.5358   13944614.9419    3137120.0079   13944105.5504
    3135535.9166   13943780.3399    3134269.6961   13943903.0858
    3132553.4494   13944627.9851
#Sta/Elev= 30
  1928.2    88.5  2088.2    85.1  2624.4   86.36  3032.4    84.8  3152.4      79
  3352.4    61.4  3792.4    61.4  3992.4      66  4112.4    62.6  4252.4    65.7
  4352.4    55.2  4392.4    54.8  4609.5    64.1  4769.5      53  4920.9   54.16
  4947.8   45.49  5026.3   43.53  5051.7   44.45  5054.6   49.23    5070   54.42
  5093.9   62.17  5249.5      61  5389.5    67.6  5729.8    67.7  6061.7    73.1
  6201.7    69.2  6421.7      72  6901.7    83.9  7099.9   81.73  7724.7    83.3
#Mann= 6 ,-1 , 0
  1928.2     .18       0  2624.4     .18       0  4920.9     .06       0
    5070     .18       0  5729.8      .1       0  7099.9      .1       0
Bank Sta=4920.9,5070
XS Rating Curve= 0
Exp/Cntr=.3,.1

Type RM Length L Ch R = 1 ,19133.4 ,851.17,1616.5,2451.95
BEGIN DESCRIPTION:
Just Upstream of Confluence with Cypress Creek
Cross Section XS13 - No topographic relief beyond limits of cross section
END DESCRIPTION:
XS GIS Cut Line= 5
    3138111.9673   13944579.9717    3137508.1446   13943998.6425
    3135637.9017   13942365.2969    3134312.0956   13942339.8006
      3132218.45      13943995.7
#Sta/Elev= 30
  1124.9    88.1  1264.9    84.5  2407.3    79.5  2607.3    74.3  2767.3    62.7
  2967.3    58.9  3527.3      61  3627.3    64.6  3747.3      61  3967.3    61.9
  4107.3    53.4  4307.3    62.1  4606.1    51.4  4905.3   58.59  4935.8   49.61
  4944.9   43.55  5056.4   42.15  5057.1   45.59  5064.6   51.29  5096.8   68.25
  5119.5   69.02  5506.1      66    5635    68.7  5792.2    75.3  6252.2    65.9
  6752.2      77  6992.2    74.6  7192.2    78.4  7490.9    77.5 8441.54      80
#Mann= 5 ,-1 , 0
  1124.9     .18       0  4905.3     .06       0  5064.6     .18       0
    5635      .1       0  7490.9     .18       0
Bank Sta=4905.3,5064.6
XS Rating Curve= 0
Exp/Cntr=.3,.1

Type RM Length L Ch R = 1 ,17516.9 ,882.76,1103.2,1045.46
BEGIN DESCRIPTION:
Just Downstream of confluence with Cypress Creeek
Cross Section XS12
END DESCRIPTION:
XS GIS Cut Line= 4
    3138178.4107   13944576.4747     3137599.126   13943760.9541
    3135969.3533   13940975.7501    3135357.4428   13939726.4328
#Sta/Elev= 30
  1242.1      88  1542.5      84  2387.5    82.9  2687.5    68.8  3367.5    73.5
  3647.5    58.7  3987.5    61.9  4307.5      62  4407.5    59.2  4487.5    62.3
  4707.5    51.5  4767.5    50.9  4828.8    56.3  4913.1   52.93  4937.5    42.8
  4975.9   39.84    5087   44.38  5111.6   56.69  5127.5      59  5167.5    57.1
  5187.5    64.2  5207.5    65.3  5307.5    63.3  5387.5    68.2  5467.5    61.2
    5742   63.54  5949.9    65.6  6049.9    75.8  6529.9    91.1    6861    95.5
#Mann= 5 ,-1 , 0
  1242.1     .18       0  4913.1     .06       0  5111.6     .18       0
    5742      .1       0    6861      .2       0
Bank Sta=4913.1,5111.6
XS Rating Curve= 0
Exp/Cntr=.3,.1

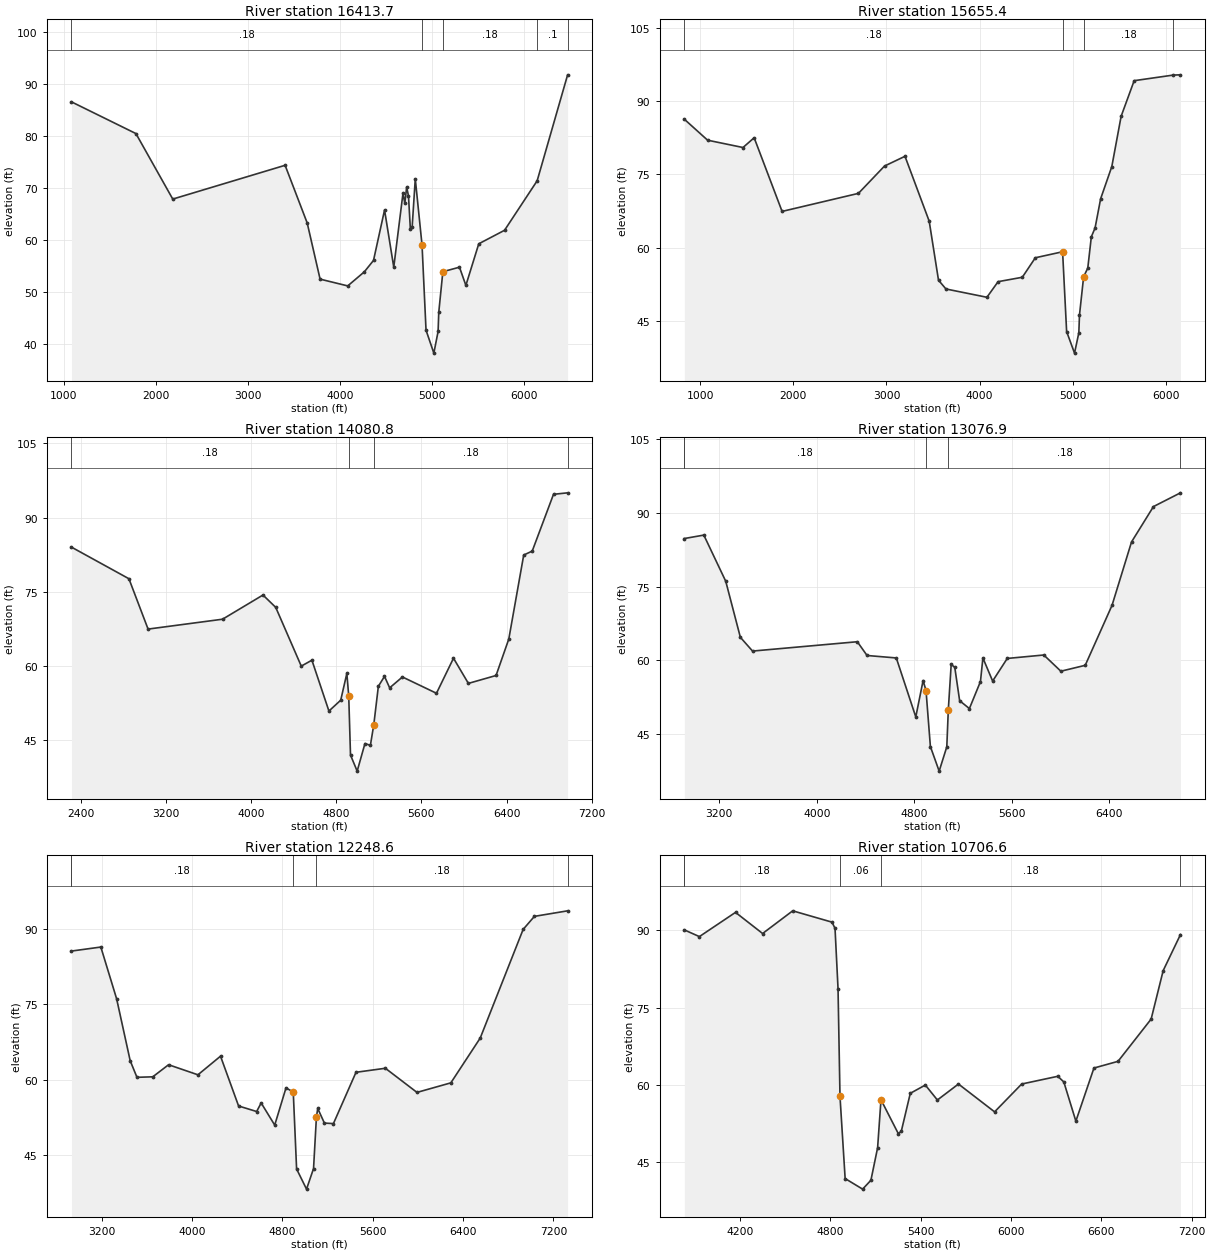
Type RM Length L Ch R = 1 ,16413.7 ,513.43,758.3,880.74
BEGIN DESCRIPTION:
Cross Section XS11
END DESCRIPTION:
XS GIS Cut Line= 4
    3138299.0968   13944461.3387    3137180.4261   13940899.2613
    3136912.7153   13940465.8247    3136211.5678    13939560.707
#Sta/Elev= 30
  1084.6    86.6  1784.6    80.5  2184.6    67.9  3404.6    74.4  3644.6    63.3
  3784.6    52.5  4084.6    51.2  4264.6    53.9  4364.6    56.1  4484.6    65.8
  4584.6    54.8  4684.6      69  4704.6    67.1  4724.6    70.2  4744.6    68.5
  4764.6    62.2  4784.6    62.6  4818.2    71.8  4891.7   59.05    4935   42.69
  5019.8   38.27  5066.1   42.44  5073.2    46.1  5117.7   53.93  5298.2    54.8
  5367.7    51.3  5507.7    59.3  5787.7    61.9  6141.8   71.42  6472.6    91.8
#Mann= 5 ,-1 , 0
  1084.6     .18       0  4891.7     .06       0  5117.7     .18       0
  6141.8      .1       0  6472.6      .2       0
Bank Sta=4891.7,5117.7
XS Rating Curve= 0
Exp/Cntr=.3,.1

Type RM Length L Ch R = 1 ,15655.4 ,610.12,1574.6,1020.4
BEGIN DESCRIPTION:
Cross Section XS10
END DESCRIPTION:
XS GIS Cut Line= 3
    3138382.2699   13944449.9433    3137715.8478   13940555.0616
    3137524.6258   13939191.0111
#Sta/Elev= 30
   828.9    86.3  1078.9      82  1458.9    80.5  1578.9    82.5  1878.9    67.4
  2698.9    71.1  2978.9    76.7  3198.9    78.7  3458.9    65.4  3558.9    53.3
  3638.9    51.5  4078.9    49.8  4198.9      53  4458.9    53.9  4598.9    57.9
  4891.7   59.13    4935   42.77  5019.8   38.35  5066.1   42.52  5073.2   46.18
  5117.7   54.01  5162.2   55.78  5200.4    62.2  5240.4      64  5300.4      70
  5420.4    76.6  5520.4    86.9  5660.4    94.2  6080.9   95.35  6157.8    95.4
#Mann= 4 ,-1 , 0
   828.9     .18       0  4891.7     .06       0  5117.7     .18       0
  6080.9      .1       0
Bank Sta=4891.7,5117.7
XS Rating Curve= 0
Exp/Cntr=.3,.1

Type RM Length L Ch R = 1 ,14080.8 ,1094.22,1003.9,808.22
BEGIN DESCRIPTION:
Cross Section XS09-No topographic relief left elev 84
END DESCRIPTION:
XS GIS Cut Line= 3
    3138587.5912   13944296.5405    3138442.4916   13941829.8752
    3138429.7434   13939637.1958
#Sta/Elev= 30
  2310.5      84  2850.5    77.6  3030.5    67.4  3730.5    69.4  4110.5    74.3
  4230.5    71.8  4470.5    59.9  4570.5    61.1  4730.5    50.8  4841.4      53
  4898.9   58.42  4916.6   53.87  4933.3   41.89    4996   38.63  5069.1   44.22
  5120.2   43.85  5152.3   48.05  5195.1   55.81  5252.8   57.82  5301.4    55.5
  5421.4    57.7  5741.4    54.4  5901.4    61.5  6041.4    56.4  6301.4      58
  6421.4    65.4  6561.4    82.4  6641.4    83.2  6841.4    94.7  6974.1      95
#Mann= 4 ,-1 , 0
  2310.5     .18       0  4916.6     .06       0  5152.3     .18       0
  6974.1      .2       0
Bank Sta=4916.6,5152.3
XS Rating Curve= 0
Exp/Cntr=.3,.1

Type RM Length L Ch R = 1 ,13076.9 ,1103.35,828.3,607.63
BEGIN DESCRIPTION:
Cross Section XS08-No topographic relief left elev 86
END DESCRIPTION:
XS GIS Cut Line= 3
    3139857.5346   13943423.3921    3139322.1129   13941052.2389
    3138582.7211   13939586.2033
#Sta/Elev= 30
  2912.8    84.8  3072.8    85.5  3252.8    76.1  3372.8    64.7  3472.8    61.9
  4332.8    63.8  4412.8      61  4652.8    60.5  4812.8    48.5  4872.8    55.9
  4896.8   53.87  4932.7   42.47  5004.7   37.47  5067.4   42.42  5079.8   49.95
  5103.4   59.18  5132.8    58.6  5172.8    51.8  5252.8    50.2  5343.7    55.7
  5363.7    60.5  5443.7    55.8  5563.7    60.4  5863.7    61.1  6003.7    57.8
  6203.7      59  6423.7    71.2  6583.7    84.1  6763.7    91.3  6985.6    94.1
#Mann= 5 , 1 , 0
  2912.8      .2       0  2912.8     .18       0  4896.8     .06       0
  5079.8     .18       0  6985.6      .2       0
Bank Sta=4896.8,5079.8
XS Rating Curve= 0
Exp/Cntr=.3,.1

Type RM Length L Ch R = 1 ,12248.6 ,1587.85,1542,1356.73
BEGIN DESCRIPTION:
Cross Section XS07-No topographic relief left elev 87
END DESCRIPTION:
XS GIS Cut Line= 2
    3141438.3034   13942709.4965    3138722.9506   13939254.7518
#Sta/Elev= 30
  2931.2    85.6  3191.2    86.4  3331.2    76.1  3451.2    63.8  3511.2    60.5
  3651.2    60.6  3791.2      63  4051.2      61  4251.2    64.7  4411.2    54.8
  4571.2    53.7  4611.2    55.4  4731.2      51  4831.2    58.4  4895.5   57.57
    4925   42.28    5013   38.27  5075.1   42.36  5100.7   52.65  5112.4    54.3
  5171.2    51.4  5251.2    51.3  5451.2    61.5  5711.2    62.3  5991.2    57.5
  6291.2    59.4  6551.2    68.3  6931.2    89.9  7031.2    92.5  7325.3    93.6
#Mann= 5 , 1 , 0
  2931.2      .2       0  2931.2     .18       0  4895.5     .06       0
  5100.7     .18       0  7325.3      .2       0
Bank Sta=4895.5,5100.7
XS Rating Curve= 0
Exp/Cntr=.3,.1

Type RM Length L Ch R = 1 ,10706.6 ,1016.61,1434.1,1881.95
BEGIN DESCRIPTION:
Cross Section XS06
END DESCRIPTION:
XS GIS Cut Line= 3
    3141909.9845   13941141.4758    3141527.5404   13940325.5952
    3139717.3051   13938757.5745
#Sta/Elev= 30
  3829.5    90.1  3929.5    88.8  4169.5    93.5  4349.5    89.4  4549.5    93.8
  4810.6    91.6  4830.6    90.4  4850.6    78.7  4863.6    57.8  4897.8   41.86
  5013.9   39.81    5069   41.53  5113.5   47.84  5135.9   57.15  5250.6    50.6
  5270.6      51  5330.6    58.4  5430.6      60  5510.6    57.1  5650.6    60.2
  5890.6    54.8  6070.6    60.2  6310.6    61.7  6350.6    60.6  6430.6      53
  6550.6    63.3  6710.6    64.6  6930.6    72.8  7010.6    82.2  7125.5    89.2
#Mann= 5 , 1 , 0
  3829.5      .2       0  3829.5     .18       0  4863.6     .06       0
  5135.9     .18       0  7125.5      .2       0
Bank Sta=4863.6,5135.9
XS Rating Curve= 0
Exp/Cntr=.3,.1

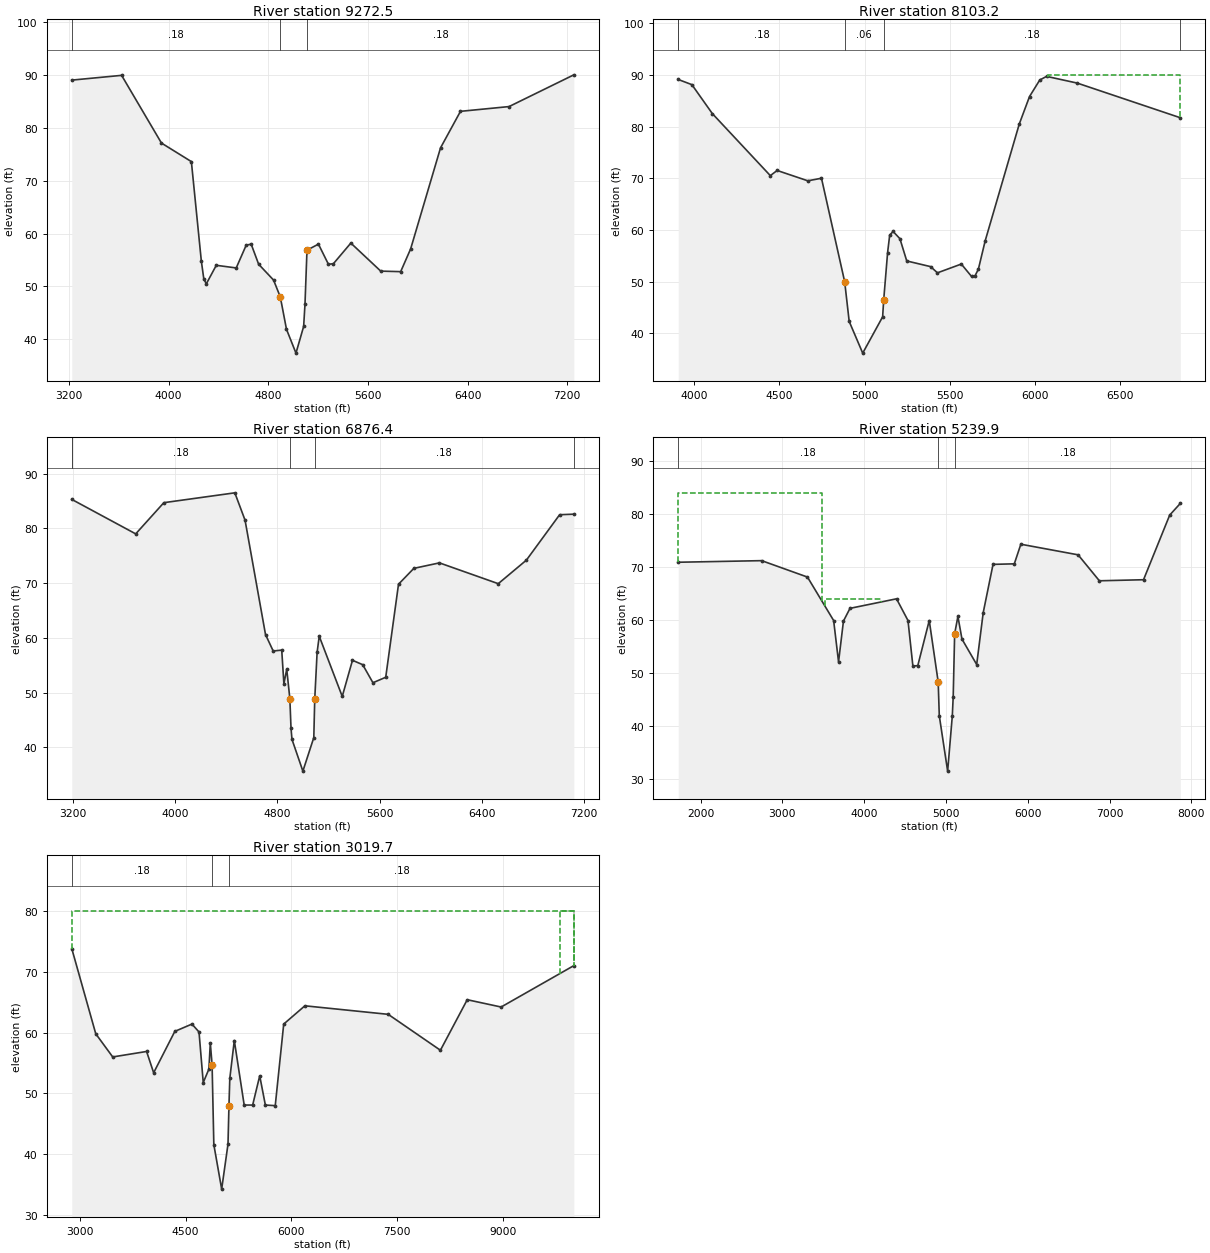
Type RM Length L Ch R = 1 ,9272.5  ,867,1169.3,1365.83
BEGIN DESCRIPTION:
Cross Section XS05
END DESCRIPTION:
XS GIS Cut Line= 3
     3142152.199   13941103.2314    3142389.8786   13938072.8172
    3142067.2447   13937136.4584
#Sta/Elev= 30
    3223      89    3623    89.9    3943    77.1    4183    73.6    4263    54.8
    4283    51.4    4303    50.5    4383      54    4543    53.5    4623    57.8
    4663      58    4723    54.2    4843    51.2    4897      48  4946.4   41.91
  5022.6    37.4  5084.2   42.44  5094.9    46.6    5111   56.86    5203      58
    5283    54.2    5323    54.3    5463    58.2    5703    52.9    5863    52.8
    5943    57.1    6183    76.2    6343    83.1    6733      84    7253      90
#Mann= 3 ,-1 , 0
    3223     .18       0    4897     .06       0    5111     .18       0
Bank Sta=4897,5111
XS Rating Curve= 0
Exp/Cntr=.3,.1

Type RM Length L Ch R = 1 ,8103.2  ,1314.67,1226.8,1073.93
BEGIN DESCRIPTION:
Cross Section XS04
END DESCRIPTION:
XS GIS Cut Line= 2
    3142445.4062   13941103.2314    3144029.6276   13938621.5761
#Sta/Elev= 30
  3907.7    89.1  3987.7    88.1  4107.7    82.5  4447.7    70.5  4487.7    71.5
  4667.7    69.5  4747.7      70  4883.7   49.98  4910.2    42.3  4989.5   36.17
  5106.3   43.19  5112.4   46.39  5135.4   55.61  5147.7      59  5167.7    59.7
  5207.7    58.3  5247.7      54  5387.7    52.9  5427.7    51.7  5567.7    53.4
  5627.7      51  5647.7    51.1  5667.7    52.4  5707.7    57.9  5907.7    80.5
  5967.7    85.8  6027.7      89  6067.7    89.7  6247.7    88.4  6851.9    81.7
#Mann= 5 , 1 , 0
  3907.7      .2       0  3907.7     .18       0  4883.7     .06       0
  5112.4     .18       0  6851.9      .2       0
#XS Ineff= 2 , 0
       0                    6075       0      90
Permanent Ineff=
       F       F
Bank Sta=4883.7,5112.4
XS Rating Curve= 0
Exp/Cntr=.3,.1

Type RM Length L Ch R = 1 ,6876.4  ,1939.6,1636.5,1399.49
BEGIN DESCRIPTION:
Cross Section XS03
No topographic relief beyond limits of cross section (elev 87 left and elev 83 right)
END DESCRIPTION:
XS GIS Cut Line= 3
    3142878.8428   13941957.3565    3143911.4418   13941396.4386
     3144689.078   13938757.5745
#Sta/Elev= 30
  3192.7    85.3  3692.7      79  3912.7    84.7  4467.8    86.5  4547.8    81.5
  4707.8    60.6  4767.8    57.6  4834.6   57.76  4851.5   51.61  4873.7   54.27
  4898.1   48.89  4907.2   43.47  4914.6   41.46    5000   35.65  5085.4   41.78
  5092.7   48.78  5111.2   57.34  5127.8    60.3  5307.8    49.3  5387.8    55.9
  5467.8    55.1  5547.8    51.8  5647.8    52.8  5747.8    69.8  5867.8    72.7
  6067.8    73.7  6527.8    69.9  6747.8    74.2  7007.8    82.5  7118.9    82.6
#Mann= 5 , 1 , 0
  3192.7      .2       0  3192.7     .18       0  4898.1     .06       0
  5092.7     .18       0  7118.9      .2       0
Bank Sta=4898.1,5092.7
XS Rating Curve= 0
Exp/Cntr=.3,.1

Type RM Length L Ch R = 1 ,5239.9  ,2052.58,2220.2,2189.25
BEGIN DESCRIPTION:
Cross Section XS02-No topographic relief beyond limits of cross section (elev 70 left and elev 66 right) Affected by Backwater from St Jacinto River
Ineffective at Sta 3484 based on floodplain confined upstream
END DESCRIPTION:
XS GIS Cut Line= 3
    3144434.1153   13944022.5545    3145670.6845   13941931.8603
    3145683.4326   13938222.1528
#Sta/Elev= 30
  1726.5    70.9  2746.6    71.2  3306.6    68.1  3626.6    59.9  3686.6    52.1
  3746.6    59.8  3826.6    62.2  4395.6      64  4535.6    59.9  4595.6    51.3
  4655.6    51.4  4795.6    59.9  4904.9   48.31  4918.3   41.94  5020.5   31.48
  5077.4   41.89  5088.5   45.52  5106.2    57.4    5146   60.68  5195.6    56.4
  5375.6    51.6  5455.6    61.4  5575.6    70.5  5835.6    70.6  5915.6    74.3
  6615.6    72.3  6875.6    67.4  7415.6    67.6  7735.6    79.8  7865.3      82
#Mann= 3 ,-1 , 0
  1726.5     .18       0  4904.9     .06       0  5106.2     .18       0
#XS Ineff= 2 ,-1
  1726.5    3484      84 3522.01    4200      64
Permanent Ineff=
       F       F
Bank Sta=4904.9,5106.2
XS Rating Curve= 0
Exp/Cntr=.3,.1

Type RM Length L Ch R = 1 ,3019.7  ,0,0,0
BEGIN DESCRIPTION:
Cross Section XS01- Limits of inffective area based on upstream effective flow area. No topographic relief beyond limits of cross section (elev 70 left and elev 66 right) Affected by Backwater from St Jacinto River
END DESCRIPTION:
XS GIS Cut Line= 4
     3146896.643   13943711.2798    3147735.8824   13942276.0599
    3147803.6056   13941097.6774    3147709.7814   13936828.7083
#Sta/Elev= 30
  2887.1    73.8  3227.1    59.8  3467.1      56  3947.1    56.9  4047.1    53.4
  4347.1    60.2  4589.7    61.4  4689.7    60.1  4749.7    51.8  4829.7      54
  4849.7    58.3  4875.1   54.69  4899.7    41.6  5010.8   34.29  5100.4   41.68
  5113.9   47.97    5126   52.47  5189.7    58.7  5329.7    48.1  5449.7    48.1
  5549.7    52.9  5629.7    48.1  5769.7      48  5889.7    61.4  6189.7    64.4
  7369.7      63  8109.7    57.1  8489.7    65.4  8969.7    64.2   10000      71
#Mann= 3 ,-1 , 0
  2887.1     .18       0  4875.1     .06       0  5113.9     .18       0
#XS Ineff= 2 , 0
       0  2887.1      80    9800       0      80
Permanent Ineff=
       F       F
Bank Sta=4875.1,5113.9
XS Rating Curve= 0
Exp/Cntr=.3,.1

Chan Stop Cuts=-1